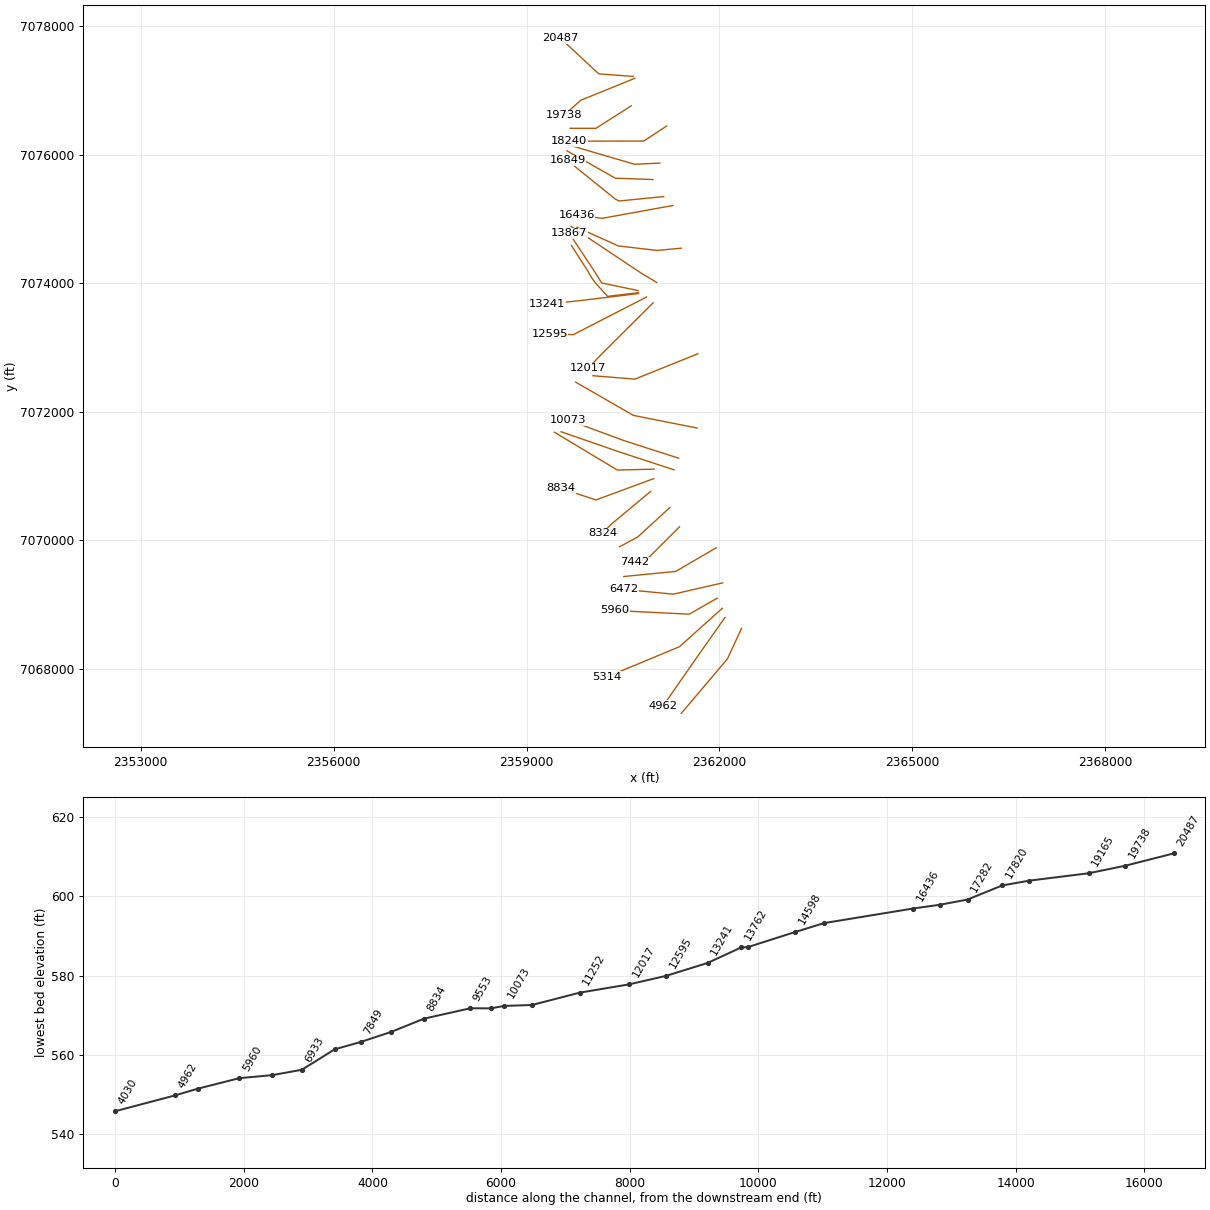
HEC-RAS study Graham Branch.prj: Graham Branch Base Level Engineering

--- Graham Branch.g01 (geometry) --- (continued)

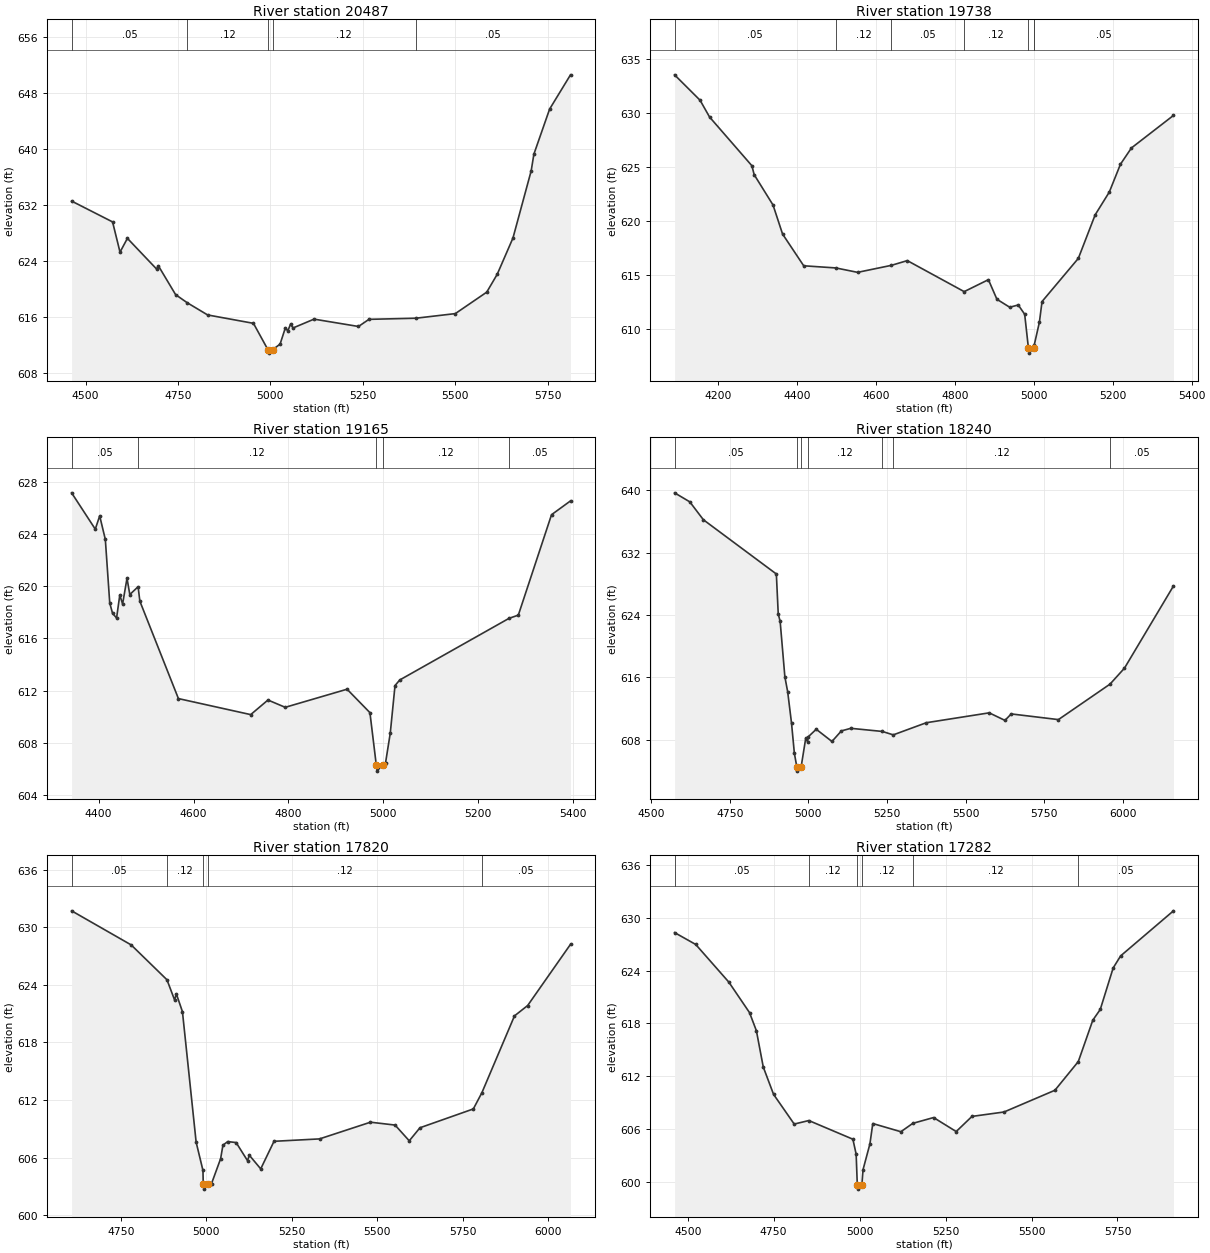
Type RM Length L Ch R = 1 ,20487   ,749,749,749
BEGIN DESCRIPTION:
Graham Branch 35.0
END DESCRIPTION:
XS GIS Cut Line= 3
       2360659.5      7077217.82      2360123.26      7077257.42
      2359528.98      7077810.02
#Sta/Elev= 30
  4462.3  632.56  4573.1  629.58  4593.2  625.26  4613.2  627.23    4692  622.85
    4697   623.3  4743.6  619.18  4774.8  618.03  4830.1  616.28  4954.1  615.08
  4993.1  611.32    4995  610.82  5006.1  611.32  5026.1  612.11  5040.2  614.41
  5047.1  614.01  5054.4  614.96  5061.2  614.42  5117.9  615.68  5238.1  614.63
  5266.4  615.65  5393.1  615.81    5500  616.47    5585  619.54  5613.3  622.09
  5655.9  627.28  5705.2  636.89  5712.5  639.27    5755  645.71  5811.5  650.61
#Mann= 5 ,-1 , 0
  4462.3     .05       0  4774.8     .12       0  4993.1     .07       0
  5006.1     .12       0  5393.1     .05       0
Bank Sta=4993.1,5006.1
XS Rating Curve= 0 ,0
Exp/Cntr=0.3,0.1

Type RM Length L Ch R = 1 ,19738   ,573,573,573
BEGIN DESCRIPTION:
Graham Branch 34.0
END DESCRIPTION:
XS GIS Cut Line= 3
      2360685.92      7077188.46      2359842.45      7076846.37
      2359579.04      7076610.03
#Sta/Elev= 30
  4089.8  633.56  4154.4   631.2  4178.5  629.64  4285.7  625.12  4291.5  624.29
  4339.3  621.47  4363.4  618.78    4417  615.83  4498.4  615.63  4553.6  615.22
  4639.1  615.87  4679.5  616.31  4823.6  613.43    4885  614.54  4906.6  612.72
    4939  611.98  4960.6  612.19  4976.9  611.33  4986.3  608.22  4988.2  607.72
  4999.6  608.22  5001.1  608.47  5014.2  610.59  5020.9  612.51  5112.9  616.52
  5155.5  620.56  5191.4  622.68  5219.6  625.26  5247.4  626.77  5353.9  629.79
#Mann= 7 ,-1 , 0
  4089.8     .05       0  4498.4     .12       0  4639.1     .05       0
  4823.6     .12       0  4986.3     .07       0  4999.6     .12       0
  5001.1     .05       0
Bank Sta=4986.3,4999.6
XS Rating Curve= 0 ,0
Exp/Cntr=0.3,0.1

Type RM Length L Ch R = 1 ,19165   ,925,925,925
BEGIN DESCRIPTION:
Graham Branch 33.0
END DESCRIPTION:
XS GIS Cut Line= 3
      2360628.98      7076759.99        2360079.        7076410.
        2359679.        7076410.
#Sta/Elev= 30
    4343  627.18  4392.9  624.39  4402.2  625.41  4414.1   623.6  4423.4  618.72
  4429.3  617.93  4437.8  617.57  4444.6  619.33  4450.5  618.64  4459.8  620.62
  4465.7  619.37  4483.2  619.97  4486.9  618.86  4568.2  611.38  4720.6  610.15
    4757  611.27  4793.4  610.71  4923.8   612.1    4972   610.3  4985.3  606.31
  4987.2  605.81  4998.6  606.31  5004.9  606.44  5014.9  608.73  5024.9  612.38
  5034.9  612.81  5265.2  617.54  5284.9  617.79  5354.9   625.5  5394.9  626.56
#Mann= 5 ,-1 , 0
    4343     .05       0  4483.2     .12       0  4985.3     .07       0
  4998.6     .12       0  5265.2     .05       0
Bank Sta=4985.3,4998.6
XS Rating Curve= 0 ,0
Exp/Cntr=0.3,0.1

Type RM Length L Ch R = 1 ,18240   ,420,420,420
BEGIN DESCRIPTION:
Graham Branch 32.0
END DESCRIPTION:
XS GIS Cut Line= 3
      2361179.45      7076446.09      2360823.94      7076212.29
      2359663.24        7076210.
#Sta/Elev= 30
  4574.5   639.7  4622.9  638.54  4666.1  636.24  4898.1  629.27  4904.1  624.14
  4910.2  623.17  4925.2  616.05  4934.1  614.14  4946.3  610.12  4955.4  606.23
  4963.4  604.44  4965.2  603.94  4976.7  604.44  4991.5  608.16  4997.5   607.7
    4999  608.33  5024.9  609.32  5074.9  607.75  5104.9  609.11  5134.9  609.44
  5234.9  609.04  5269.9   608.6  5374.9  610.16  5574.9  611.43  5624.9  610.46
  5644.9  611.29  5794.9  610.56    5959  615.12  6004.9  617.17  6160.7  627.73
#Mann= 7 ,-1 , 0
  4574.5     .05       0  4963.4     .07       0  4976.7     .05       0
    4999     .12       0  5234.9     .05       0  5269.9     .12       0
    5959     .05       0
Bank Sta=4963.4,4976.7
XS Rating Curve= 0 ,0
Exp/Cntr=0.3,0.1

Type RM Length L Ch R = 1 ,17820   ,538,538,538
BEGIN DESCRIPTION:
Graham Branch 31.0
END DESCRIPTION:
XS GIS Cut Line= 3
       2361073.2      7075868.86      2360679.11      7075850.86
      2359656.03      7076150.99
#Sta/Elev= 30
  4605.5  631.71  4779.9  628.16  4884.7  624.53  4907.1  622.42  4912.1  623.07
    4930  621.21  4970.1  607.62  4990.1  604.67  4990.9  603.23  4992.8  602.73
  5004.2  603.23  5015.2  603.31  5041.8   605.9  5048.6  607.31  5062.6  607.68
  5087.2  607.58  5120.6  605.69  5125.8  606.26  5159.2  604.84  5198.1  607.71
  5331.4  607.96  5480.6   609.7  5552.6   609.4  5594.1  607.76  5625.4  609.12
  5781.7  611.08  5806.9  612.78  5902.2  620.77  5940.8  621.85  6066.2  628.22
#Mann= 5 ,-1 , 0
  4605.5     .05       0  4884.7     .12       0  4990.9     .07       0
  5004.2     .12       0  5806.9     .05       0
Bank Sta=4990.9,5004.2
XS Rating Curve= 0 ,0
Exp/Cntr=0.3,0.1

Type RM Length L Ch R = 1 ,17282   ,433,433,433
BEGIN DESCRIPTION:
Graham Branch 30.0
END DESCRIPTION:
XS GIS Cut Line= 4
      2360966.81      7075612.78       2360452.9      7075631.77
      2360387.07      7075630.94      2359628.97      7076060.02
#Sta/Elev= 30
  4461.7  628.31  4523.2  626.96  4619.6  622.68  4679.7  619.22  4699.7  617.16
  4719.7  613.04  4749.7  609.93  4809.7  606.56  4852.2  606.96  4980.4  604.84
  4989.9  603.14  4993.2  599.67  4995.1  599.17  5006.6  599.67  5009.9  601.38
  5029.9   604.3  5038.3  606.62    5120  605.69  5154.6  606.64  5215.1   607.3
  5280.9  605.71  5326.8  607.43    5420  607.93  5568.1   610.4  5636.1  613.66
  5678.3  618.36    5700  619.58  5737.5  624.29  5759.2  625.66  5912.9  630.78
#Mann= 6 ,-1 , 0
  4461.7     .05       0  4852.2     .12       0  4993.2     .07       0
  5006.6     .12       0  5154.6     .12       0  5636.1     .05       0
Bank Sta=4993.2,5006.6
XS Rating Curve= 0 ,0
Exp/Cntr=0.3,0.1

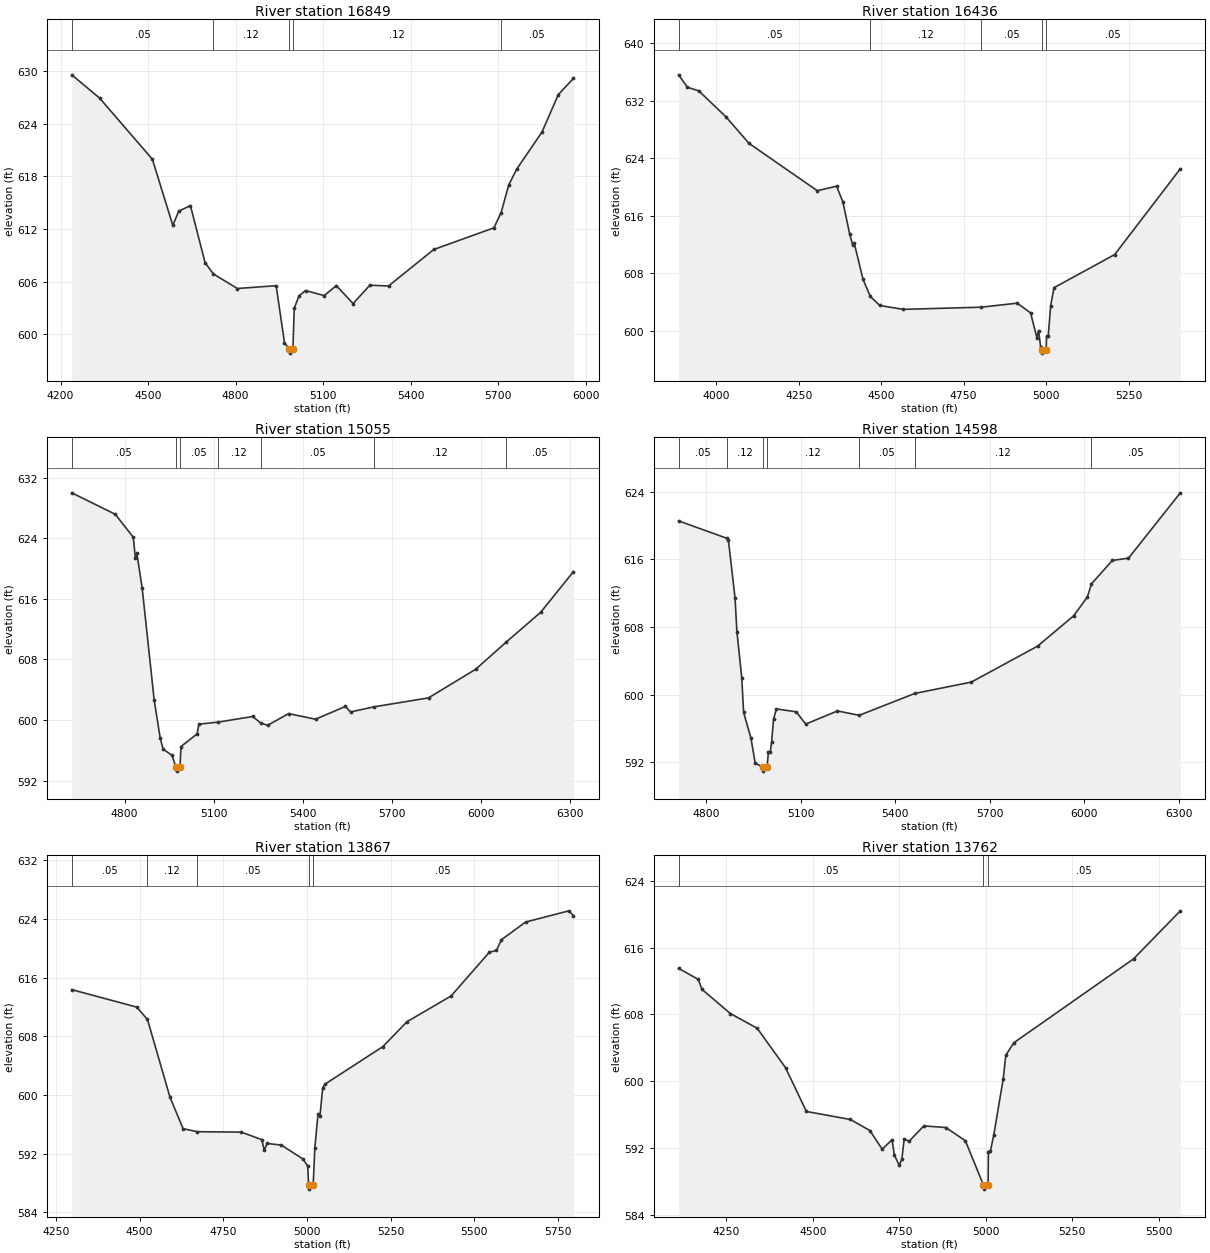
Type RM Length L Ch R = 1 ,16849   ,413,413,413
BEGIN DESCRIPTION:
Graham Branch 29.0
END DESCRIPTION:
XS GIS Cut Line= 4
      2361133.94      7075348.03      2360439.53      7075279.38
        2360379.        7075310.      2359636.51      7075910.09
#Sta/Elev= 30
  4238.2  629.59  4333.6  626.94  4514.5  619.97  4584.8  612.42  4604.9  614.04
  4645.1  614.68  4695.4  608.16    4724  606.88  4805.9  605.22  4939.1  605.54
  4967.6  599.05  4983.2  598.35  4985.1  597.85  4996.6  598.35    5001  602.96
  5017.4  604.38  5039.8  604.99  5103.7  604.41  5145.4  605.55  5202.9   603.5
  5260.4   605.6  5324.4  605.51  5479.6  609.67  5685.8  612.14  5710.4  613.87
  5736.7  617.05  5764.2  618.85  5850.5  623.06  5906.5  627.33  5958.5  629.19
#Mann= 5 ,-1 , 0
  4238.2     .05       0    4724     .12       0  4983.2     .07       0
  4996.6     .12       0  5710.4     .05       0
Bank Sta=4983.2,4996.6
XS Rating Curve= 0 ,0
Exp/Cntr=0.3,0.1

Type RM Length L Ch R = 1 ,16436   ,1381,1381,1381
BEGIN DESCRIPTION:
Graham Branch 28.0
END DESCRIPTION:
XS GIS Cut Line= 3
        2361279.        7075210.        2360179.        7075010.
      2359778.95      7075060.01
#Sta/Elev= 30
  3885.9  635.57  3912.6  633.84  3946.9  633.35  4029.5  629.73  4099.3  626.05
  4306.4  619.47  4364.9   620.1  4383.9  617.92  4404.3  613.52  4413.2  611.98
  4418.2  612.23  4444.9  607.17  4467.1  604.79  4495.7  603.53  4566.9  602.99
  4802.7  603.29  4912.5  603.85  4953.1   602.5  4972.2  599.05  4977.3  600.04
  4983.6  597.73    4987  597.41  4988.9  596.91  5000.5  597.41  5001.4  599.24
  5006.5  599.24    5014   603.5  5024.1     606    5208   610.6  5407.1  622.52
#Mann= 5 ,-1 , 0
  3885.9     .05       0  4467.1     .12       0  4802.7     .05       0
    4987    .033       0  5000.5     .05       0
Bank Sta=4987,5000.5
XS Rating Curve= 0 ,0
Exp/Cntr=0.3,0.1

Type RM Length L Ch R = 1 ,15055   ,457,457,457
BEGIN DESCRIPTION:
Graham Branch 27.0
END DESCRIPTION:
XS GIS Cut Line= 4
      2361405.18      7074545.07        2361029.        7074510.
      2360428.62      7074579.79      2359784.12      7074870.58
#Sta/Elev= 30
  4622.2  630.02    4769  627.18  4829.3  624.15  4836.4  621.42  4841.4  622.03
  4859.4   617.4  4899.6  602.68  4919.7  597.68  4929.7  596.15  4959.8  595.33
  4973.1  593.74  4975.1  593.24  4986.7  593.74    4990  596.49  5044.3  598.16
  5050.3  599.45  5113.8  599.71  5231.6  600.46  5258.4  599.59  5281.9   599.3
  5352.4  600.84    5443   600.1  5543.6  601.79  5560.8  601.06  5640.3  601.74
  5823.4  602.92  5982.2   606.7  6084.4  610.27  6201.3  614.24  6311.5  619.61
#Mann= 7 ,-1 , 0
  4622.2     .05       0  4973.1    .033       0  4986.7     .05       0
  5113.8     .12       0  5258.4     .05       0  5640.3     .12       0
  6084.4     .05       0
Bank Sta=4973.1,4986.7
XS Rating Curve= 0 ,0
Exp/Cntr=0.3,0.1

Type RM Length L Ch R = 1 ,14598   ,731,731,731
BEGIN DESCRIPTION:
Graham Branch 26.0
END DESCRIPTION:
XS GIS Cut Line= 3
       2361025.4      7074011.23        2360779.        7074160.
      2359693.28      7074883.81
#Sta/Elev= 30
  4712.4  620.55  4865.9  618.49  4870.2  618.35  4891.5  611.44  4897.4  607.46
  4912.9  601.97  4918.7   597.9  4941.8  594.89  4955.6  591.88  4979.8  591.46
  4981.8  590.96  4993.4  591.46  4997.3  593.19  5003.2  593.19  5007.7  594.38
  5013.7   597.1  5022.8  598.32  5085.9  597.97  5115.9  596.52  5216.6  598.08
  5285.7  597.56  5462.4  600.15  5641.7  601.49    5852  605.74  5966.2  609.32
  6009.8  611.53  6023.1  613.11  6089.4  615.88  6140.5  616.14  6305.1  623.87
#Mann= 7 ,-1 , 0
  4712.4     .05       0  4865.9     .12       0  4979.8     .07       0
  4993.4     .12       0  5285.7     .05       0  5462.4     .12       0
  6023.1     .05       0
Bank Sta=4979.8,4993.4
XS Rating Curve= 0 ,0
Exp/Cntr=0.3,0.1

Type RM Length L Ch R = 1 ,13867   ,105,105,105
BEGIN DESCRIPTION:
Graham Branch 25.0
END DESCRIPTION:
XS GIS Cut Line= 4
      2360734.63      7073885.35       2360169.2      7074003.98
      2360071.97      7074160.59      2359665.66      7074775.02
#Sta/Elev= 30
  4297.2  614.36  4491.2  611.98  4523.3   610.3  4590.9  599.66  4629.9  595.41
  4671.6     595  4803.6  594.94  4864.9  593.91  4872.5  592.45  4880.5  593.39
    4923  593.18    4988  591.27  5002.1  590.31  5004.7  587.67  5006.7  587.17
  5018.3  587.67  5023.3  592.76  5032.8  597.37  5038.7  597.16  5046.8  600.98
  5054.1  601.49  5226.4  606.59  5298.4  609.98  5430.2  613.49  5544.6  619.45
  5565.7   619.7  5580.7  621.16  5652.9  623.57  5782.3   625.1  5795.9  624.44
#Mann= 5 ,-1 , 0
  4297.2     .05       0  4523.3     .12       0  4671.6     .05       0
  5004.7    .033       0  5018.3     .05       0
Bank Sta=5004.7,5018.3
XS Rating Curve= 0 ,0
Exp/Cntr=0.3,0.1

Type RM Length L Ch R = 1 ,13762   ,521,521,521
BEGIN DESCRIPTION:
Mapping XS cf04cb73
END DESCRIPTION:
XS GIS Cut Line= 6
      2360735.92      7073852.27       2360261.8      7073795.85
      2360074.08      7074000.93      2360013.32      7074085.56
      2359946.04      7074199.49      2359699.58      7074586.48
#Sta/Elev= 30
  4111.9  613.51  4168.8  612.19  4179.3     611  4261.5   608.1    4339  606.34
    4421  601.62  4481.4  596.37  4608.6  595.41  4664.9  594.09  4700.6  591.85
    4729  592.98  4735.8  591.15    4750  589.91  4757.4  590.66  4764.1  593.07
  4778.3   592.8  4820.9  594.64  4884.7  594.45  4941.2  592.86  4993.2  587.57
  4995.1  587.07  5006.8  587.57  5007.7  591.57  5013.5  591.64  5023.2  593.55
  5050.6  600.29    5058  603.11  5081.3   604.6  5427.3  614.64  5562.7   620.4
#Mann= 3 ,-1 , 0
  4111.9     .05       0  4993.2    .033       0  5006.8     .05       0
Bank Sta=4993.2,5006.8
XS Rating Curve= 0 ,0
Exp/Cntr=0.3,0.1

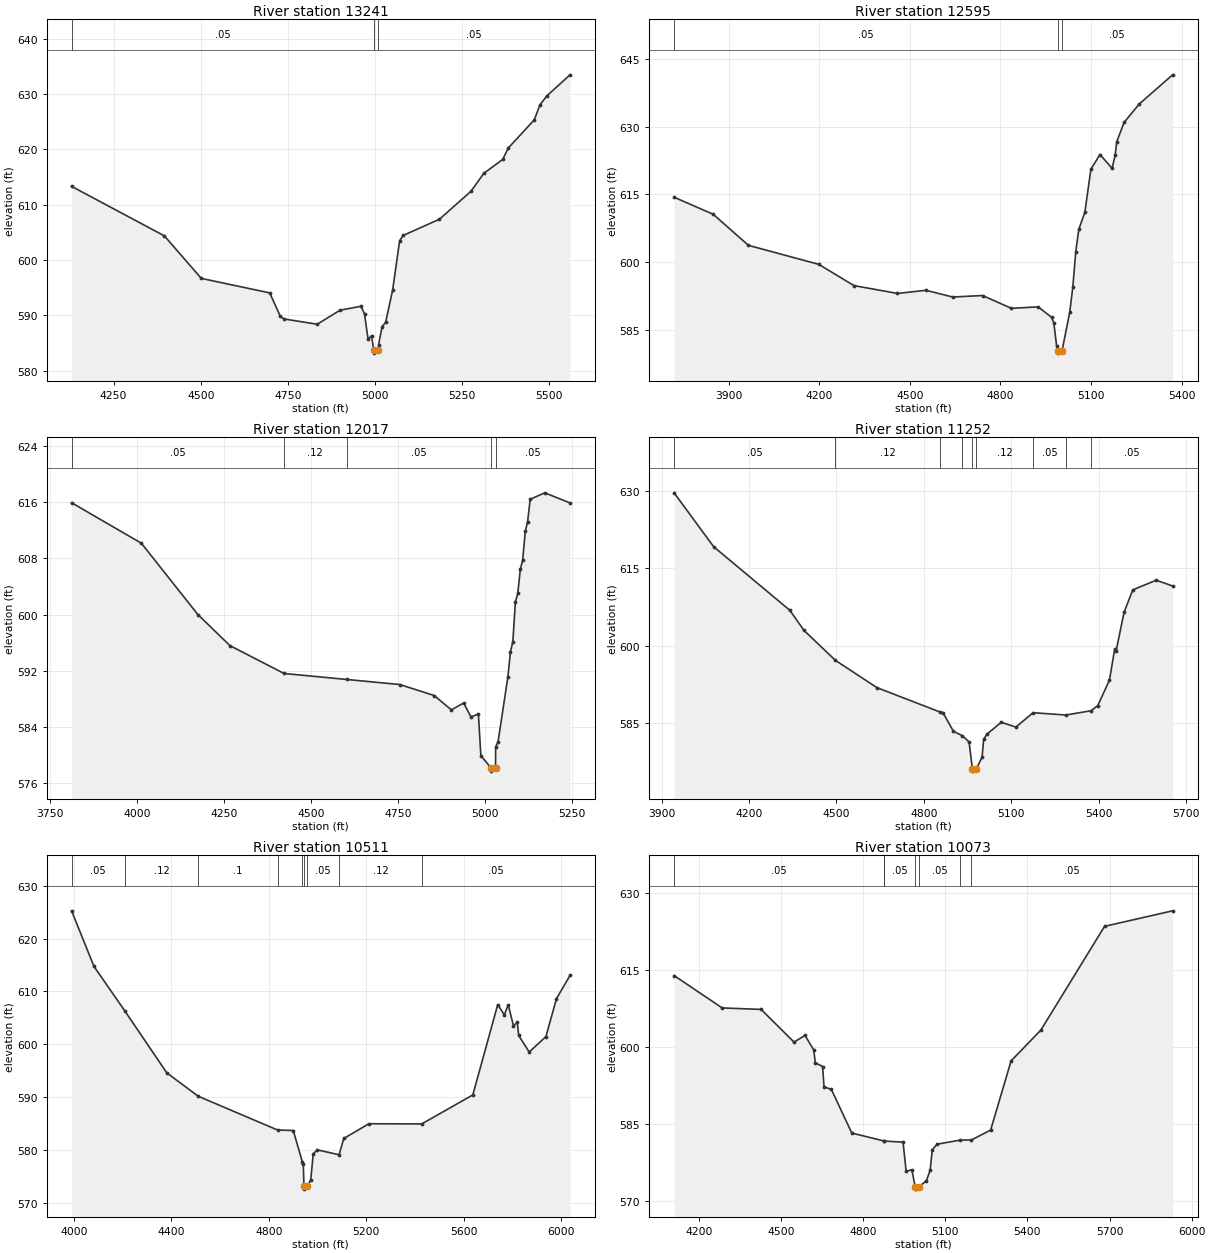
Type RM Length L Ch R = 1 ,13241   ,646,646,646
BEGIN DESCRIPTION:
Graham Branch 24.0
END DESCRIPTION:
XS GIS Cut Line= 3
      2360743.25      7073839.77      2359879.27      7073735.11
      2359323.15      7073673.63
#Sta/Elev= 30
  4129.7   613.3  4395.9  604.35  4501.8  596.67  4698.1  594.05  4728.3  589.83
  4738.4  589.35  4834.3  588.39  4899.5  590.92    4960  591.64    4970  590.22
  4980.1  585.68  4990.2  586.33  4996.3  583.67  4998.3  583.17    5010  583.67
  5010.3  584.72  5020.4  587.96  5030.5  588.73  5050.6  594.58  5070.7  603.49
  5080.8  604.43  5184.7  607.36  5275.5  612.42  5312.2  615.66  5366.3  618.16
  5382.6  620.25    5457  625.33  5473.1  628.03  5493.3  629.67  5559.5  633.45
#Mann= 3 ,-1 , 0
  4129.7     .05       0  4996.3    .033       0    5010     .05       0
Bank Sta=4996.3,5010
XS Rating Curve= 0 ,0
Exp/Cntr=0.3,0.1

Type RM Length L Ch R = 1 ,12595   ,578,578,578
BEGIN DESCRIPTION:
Graham Branch 23.0
END DESCRIPTION:
XS GIS Cut Line= 3
      2360866.63      7073785.52       2359728.2      7073199.95
      2359358.84        7073210.
#Sta/Elev= 30
  3719.8  614.39  3849.3  610.62  3965.8  603.75  4198.5  599.55    4315  594.85
    4459  593.11  4553.3  593.81    4642  592.32  4740.5  592.65    4836  589.82
  4924.7  590.14    4969  587.83  4976.6  586.54  4985.6  581.57  4989.9  580.41
  4991.8  579.91  5003.6  580.41  5029.2  588.98  5039.2  594.44  5049.2  602.39
  5059.2  607.31  5079.2  611.06  5099.2   620.6  5129.2  623.84  5169.3  620.79
  5179.3  623.65  5184.9  626.71  5209.3  630.96  5259.3  635.02  5369.5  641.47
#Mann= 3 ,-1 , 0
  3719.8     .05       0  4989.9    .033       0  5003.6     .05       0
Bank Sta=4989.9,5003.6
XS Rating Curve= 0 ,0
Exp/Cntr=0.3,0.1

Type RM Length L Ch R = 1 ,12017   ,765,765,765
BEGIN DESCRIPTION:
Graham Branch 22.0
END DESCRIPTION:
XS GIS Cut Line= 3
      2360968.19      7073694.36      2360127.25      7072855.78
      2359960.84      7072675.83
#Sta/Elev= 30
  3812.4   615.9  4012.9  610.15  4175.5     600  4267.5  595.59  4423.1  591.63
  4602.8  590.78  4755.4  590.06  4854.4   588.5  4903.9  586.46  4939.2  587.43
  4960.4  585.45  4981.6  585.87  4988.7  579.95  5017.1  578.25    5019  577.75
  5030.8  578.25  5031.3  581.21  5038.1  581.91  5066.4  591.15  5073.8  594.71
  5080.6  596.16    5088  601.79  5094.8  603.01  5102.1  606.42    5109  607.78
  5116.3  611.82  5123.1  613.23  5130.5   616.4  5172.5  617.31  5245.1  615.87
#Mann= 5 ,-1 , 0
  3812.4     .05       0  4423.1     .12       0  4602.8     .05       0
  5017.1    .033       0  5030.8     .05       0
Bank Sta=5017.1,5030.8
XS Rating Curve= 0 ,0
Exp/Cntr=0.3,0.1

Type RM Length L Ch R = 1 ,11252   ,741,741,741
BEGIN DESCRIPTION:
Graham Branch 21.0
END DESCRIPTION:
XS GIS Cut Line= 3
       2361664.9      7072902.43      2360684.52      7072507.57
      2360033.01      7072560.96
#Sta/Elev= 30
  3943.1  629.59  4078.8  619.15  4340.3  606.83  4388.7  602.94  4496.9  597.12
  4639.4  591.84  4854.4  587.15  4865.8     587  4901.7  583.38  4931.7  582.55
  4955.4  581.33  4966.6  576.17  4968.6  575.67  4980.7  576.17    5000  578.39
  5005.5  581.83  5015.6  582.77  5065.7  585.14  5115.9   584.2  5174.9  586.99
  5287.6  586.54  5373.9  587.37  5396.8  588.36    5437  593.28  5455.2  599.35
  5460.2  599.03  5487.2  606.45  5517.3  610.79  5597.5  612.66  5653.7  611.54
#Mann= 9 ,-1 , 0
  3943.1     .05       0  4496.9     .12       0  4854.4     .05       0
  4931.7     .12       0  4966.6     .07       0  4980.7     .12       0
  5174.9     .05       0  5287.6     .12       0  5373.9     .05       0
Bank Sta=4966.6,4980.7
XS Rating Curve= 0 ,0
Exp/Cntr=0.3,0.1

Type RM Length L Ch R = 1 ,10511   ,438,438,438
BEGIN DESCRIPTION:
Graham Branch 20.0
END DESCRIPTION:
XS GIS Cut Line= 3
      2361652.42       7071746.7      2360661.98      7071943.48
      2359762.96      7072461.33
#Sta/Elev= 30
  3990.2  625.27  4082.2  614.74  4209.5  606.27  4381.1  594.59    4510  590.16
    4836  583.76  4900.6  583.66  4937.5  577.79  4941.9  577.23  4944.6  573.06
  4946.6  572.56  4958.8  573.06  4972.5  574.35  4982.6  579.21    4999     580
  5088.8  579.07  5108.1  582.15  5211.2  584.94  5428.3  584.91  5638.2  590.41
  5740.3   607.5  5767.6  605.57  5783.4  607.47    5805  603.52  5820.8  604.13
  5826.5  601.66  5869.6  598.53  5938.2  601.44  5981.7  608.64  6037.5  613.05
#Mann= 9 ,-1 , 0
  3990.2     .05       0  4209.5     .12       0    4510      .1       0
    4836     .12       0  4937.5     .05       0  4944.6    .033       0
  4958.8     .05       0  5088.8     .12       0  5428.3     .05       0
Bank Sta=4944.6,4958.8
XS Rating Curve= 0 ,0
Exp/Cntr=0.3,0.1

Type RM Length L Ch R = 1 ,10073   ,200,200,200
BEGIN DESCRIPTION:
Graham Branch 19.0
END DESCRIPTION:
XS GIS Cut Line= 3
      2361366.03      7071277.34       2360518.2      7071550.33
      2359645.58      7071872.81
#Sta/Elev= 30
  4109.3  613.91  4284.8  607.61  4427.3  607.32  4547.4  600.95  4587.6  602.26
  4619.7  599.39    4625  596.94  4651.8   596.2    4657  592.25  4683.9  591.73
  4758.5  583.24  4877.5  581.68  4877.6  581.68  4945.7  581.47  4957.1  575.77
  4977.8   576.1  4989.8  572.82  4991.8  572.32  5004.1  572.82  5031.1  573.95
  5044.7  576.02  5052.5  579.98  5069.8  581.07  5155.1  581.87  5195.5  581.89
  5265.7  583.83  5340.3  597.29  5449.2   603.3  5681.9   623.5  5930.3  626.52
#Mann= 7 ,-1 , 0
  4109.3     .05       0  4877.5     .12       0  4877.6     .05       0
  4989.8    .033       0  5004.1     .05       0  5155.1     .12       0
  5195.5     .05       0
Bank Sta=4989.8,5004.1
XS Rating Curve= 0 ,0
Exp/Cntr=0.3,0.1

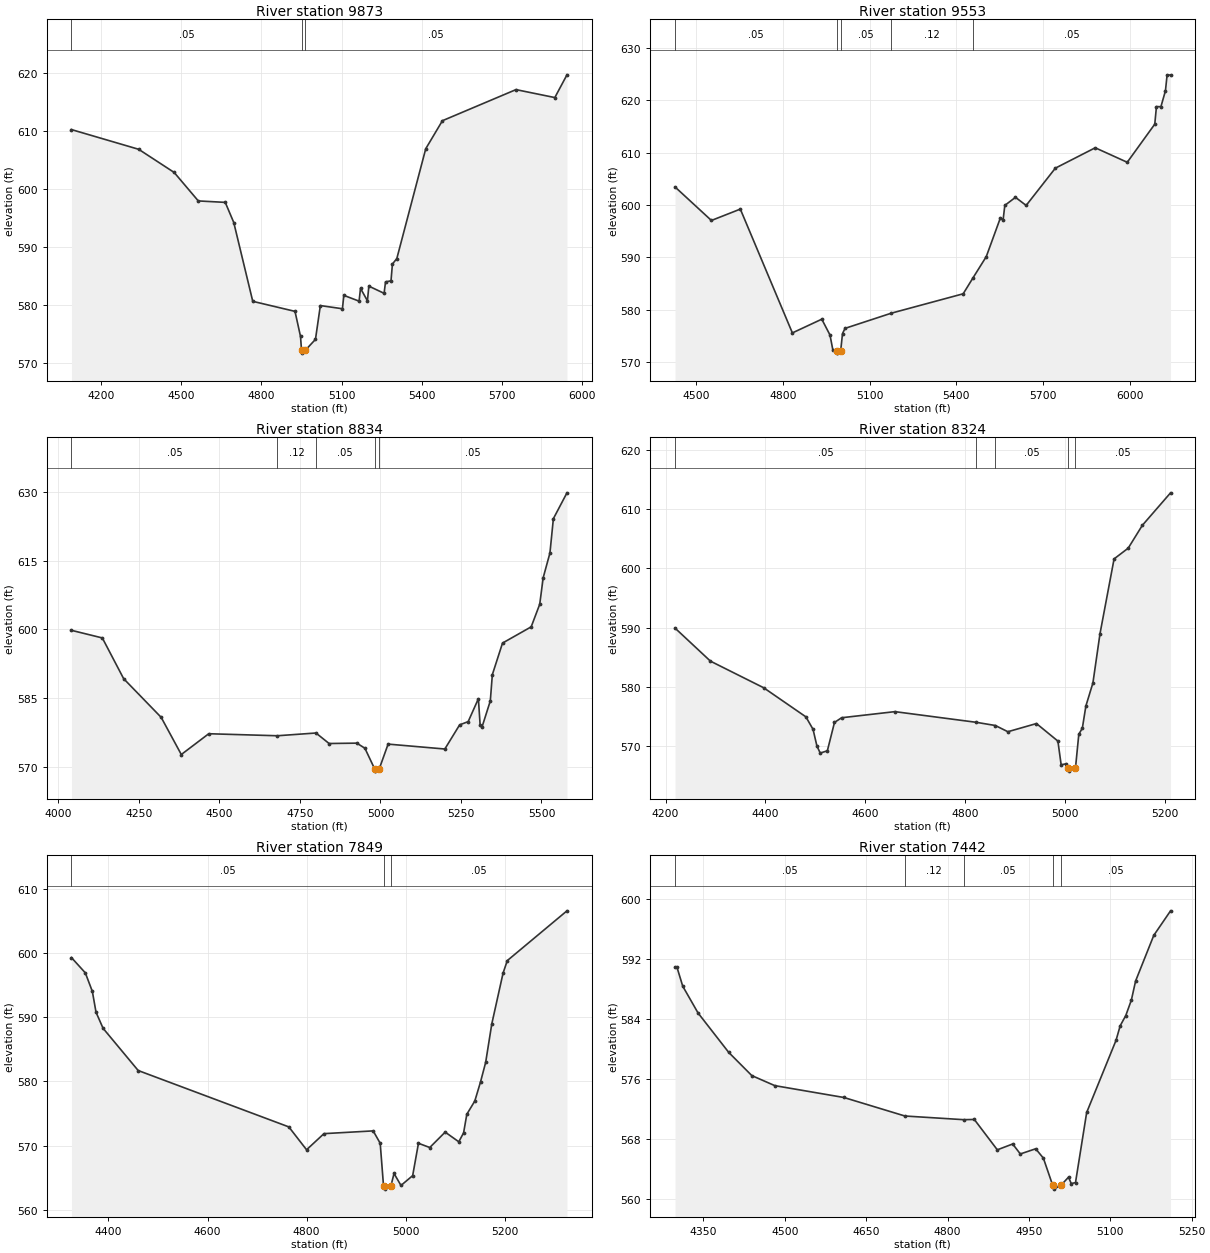
Type RM Length L Ch R = 1 ,9873    ,320,320,320
BEGIN DESCRIPTION:
Mapping XS 90c40a29
END DESCRIPTION:
XS GIS Cut Line= 3
      2361293.11      7071096.78      2360428.67      7071380.14
      2359537.93      7071688.79
#Sta/Elev= 30
  4090.3  610.25  4341.7  606.85  4474.3  602.86  4564.5  597.95  4665.3   597.7
  4697.1  594.23  4768.1  580.64    4926  578.91  4946.6  574.59  4950.4  572.21
  4952.4  571.71  4964.7  572.21  5002.5  574.08  5020.8  579.91  5103.3  579.36
  5108.6  581.67  5165.6  580.67  5170.9  582.88  5196.8  580.73  5202.1  583.26
  5259.1  582.02  5264.4  583.99  5284.9  584.18  5290.2  587.07  5306.6  588.01
  5414.8  606.95  5477.1  611.78  5752.1  617.14  5897.3  615.77  5942.7  619.69
#Mann= 3 ,-1 , 0
  4090.3     .05       0  4950.4    .033       0  4964.7     .05       0
Bank Sta=4950.4,4964.7
XS Rating Curve= 0 ,0
Exp/Cntr=0.3,0.1

Type RM Length L Ch R = 1 ,9553    ,719,719,719
BEGIN DESCRIPTION:
Graham Branch 18.0
END DESCRIPTION:
XS GIS Cut Line= 3
      2360984.71      7071107.15      2360411.88      7071093.34
      2359434.56       7071681.6
#Sta/Elev= 30
    4427  603.46  4552.8  597.06  4652.8  599.23  4832.8  575.59  4934.5  578.21
  4962.9  575.19  4972.9  572.31  4985.7  572.23  4987.7  571.73    5000  572.23
  5006.2  575.47    5015  576.46  5175.1  579.36  5423.5  583.06  5457.8  586.13
  5503.4  590.16    5552  597.52  5561.7  597.21  5567.5  599.94  5604.4  601.48
  5641.3  599.93  5742.3  607.05  5880.2  610.94  5990.9  608.17  6086.1  615.45
  6091.9   618.8  6107.4  618.79    6123  621.82  6128.8  624.87  6140.7  624.82
#Mann= 5 ,-1 , 0
    4427     .05       0  4985.7    .033       0    5000     .05       0
  5175.1     .12       0  5457.8     .05       0
Bank Sta=4985.7,5000
XS Rating Curve= 0 ,0
Exp/Cntr=0.3,0.1

Type RM Length L Ch R = 1 ,8834    ,510,510,510
BEGIN DESCRIPTION:
Graham Branch 17.0
END DESCRIPTION:
XS GIS Cut Line= 3
      2360979.01        7070960.       2360078.8      7070628.23
      2359528.97      7070810.01
#Sta/Elev= 30
  4040.6  599.81  4136.5  598.15  4202.7  589.27  4319.2  580.84  4381.7  572.74
  4466.9  577.27  4679.9  576.83  4799.8  577.43  4840.5  575.14  4926.6  575.22
  4951.7  574.11  4981.9  569.62  4983.9  569.12  4996.3  569.62  5023.8  575.01
  5199.9  573.94  5245.9  579.21  5272.4  579.91  5304.1  584.91  5309.4  579.26
  5315.8  578.83  5341.1  584.43  5347.4  590.15    5379  597.03    5468  600.57
  5494.5  605.49  5505.3  611.29  5526.2  616.66  5536.9  624.15  5579.1  629.78
#Mann= 5 ,-1 , 0
  4040.6     .05       0  4679.9     .12       0  4799.8     .05       0
  4981.9    .033       0  4996.3     .05       0
Bank Sta=4981.9,4996.3
XS Rating Curve= 0 ,0
Exp/Cntr=0.3,0.1

Type RM Length L Ch R = 1 ,8324    ,475,475,475
BEGIN DESCRIPTION:
Graham Branch 16.0
END DESCRIPTION:
XS GIS Cut Line= 3
      2360929.02      7070760.02        2360329.        7070260.
      2360178.99      7070109.99
#Sta/Elev= 30
  4218.9  589.92  4289.9  584.34  4396.6  579.85  4481.2  574.94  4495.5  572.84
  4503.3  570.02  4509.9  568.83  4524.2  569.21  4538.5     574  4552.8  574.79
  4659.6  575.82  4822.6  574.02  4860.9  573.48    4886  572.43  4943.3  573.81
  4986.3  570.85  4992.8  566.85  5003.5  567.03  5006.6  566.28  5008.6  565.78
  5021.5  566.28  5028.2     572  5035.3  573.03  5042.4  576.78  5056.5  580.67
  5070.7  588.99  5098.9   601.6  5127.2  603.41  5155.5  607.26  5212.1  612.75
#Mann= 5 ,-1 , 0
  4218.9     .05       0  4822.6     .12       0  4860.9     .05       0
  5006.6    .033       0  5021.5     .05       0
Bank Sta=5006.6,5021.5
XS Rating Curve= 0 ,0
Exp/Cntr=0.3,0.1

Type RM Length L Ch R = 1 ,7849    ,407,407,407
BEGIN DESCRIPTION:
Graham Branch 15.0
END DESCRIPTION:
XS GIS Cut Line= 3
      2361228.98      7070509.98      2360731.58      7070054.26
      2360445.69      7069898.84
#Sta/Elev= 30
  4325.4  599.29  4353.4  596.91  4367.6  594.02    4375  590.78  4389.2  588.28
  4460.1   581.7  4764.1  572.92  4799.9  569.36    4835  571.87  4934.3   572.3
  4948.5  570.37  4955.2  563.73  4957.2  563.23  4970.1  563.73  4976.4  565.67
  4990.4   563.8    5014  565.33  5025.7  570.37  5048.5  569.71  5079.6  572.11
  5107.1   570.6  5116.8     572  5123.3  574.89  5139.4  576.95  5150.9  579.91
  5161.3  582.96  5173.7  588.97  5196.4  596.86    5205  598.82  5325.4  606.57
#Mann= 3 ,-1 , 0
  4325.4     .05       0  4955.2    .033       0  4970.1     .05       0
Bank Sta=4955.2,4970.1
XS Rating Curve= 0 ,0
Exp/Cntr=0.3,0.1

Type RM Length L Ch R = 1 ,7442    ,509,509,509
BEGIN DESCRIPTION:
Graham Branch 14.0
END DESCRIPTION:
XS GIS Cut Line= 3
      2361379.03      7070210.03        2360879.        7069710.
        2360679.        7069660.
#Sta/Elev= 30
  4297.7  590.94  4301.3  590.94  4311.9  588.42  4340.2  584.84  4396.7  579.59
  4439.2   576.5  4481.6  575.16  4608.9  573.58  4721.4  571.11  4829.8  570.62
  4849.3  570.65  4891.7   566.6    4920  567.38  4934.1  566.05  4962.4  566.74
  4976.6  565.49  4993.8  561.86  4995.8  561.36  5008.8  561.86  5022.9  562.95
    5028   562.1  5035.8  562.23  5056.4  571.58  5110.5   581.2  5118.2  583.15
  5128.5  584.51  5138.8  586.58  5146.6  589.12  5180.1   595.2    5211  598.47
#Mann= 5 ,-1 , 0
  4297.7     .05       0  4721.4     .12       0  4829.8     .05       0
  4993.8    .033       0  5008.8     .05       0
Bank Sta=4993.8,5008.8
XS Rating Curve= 0 ,0
Exp/Cntr=0.3,0.1

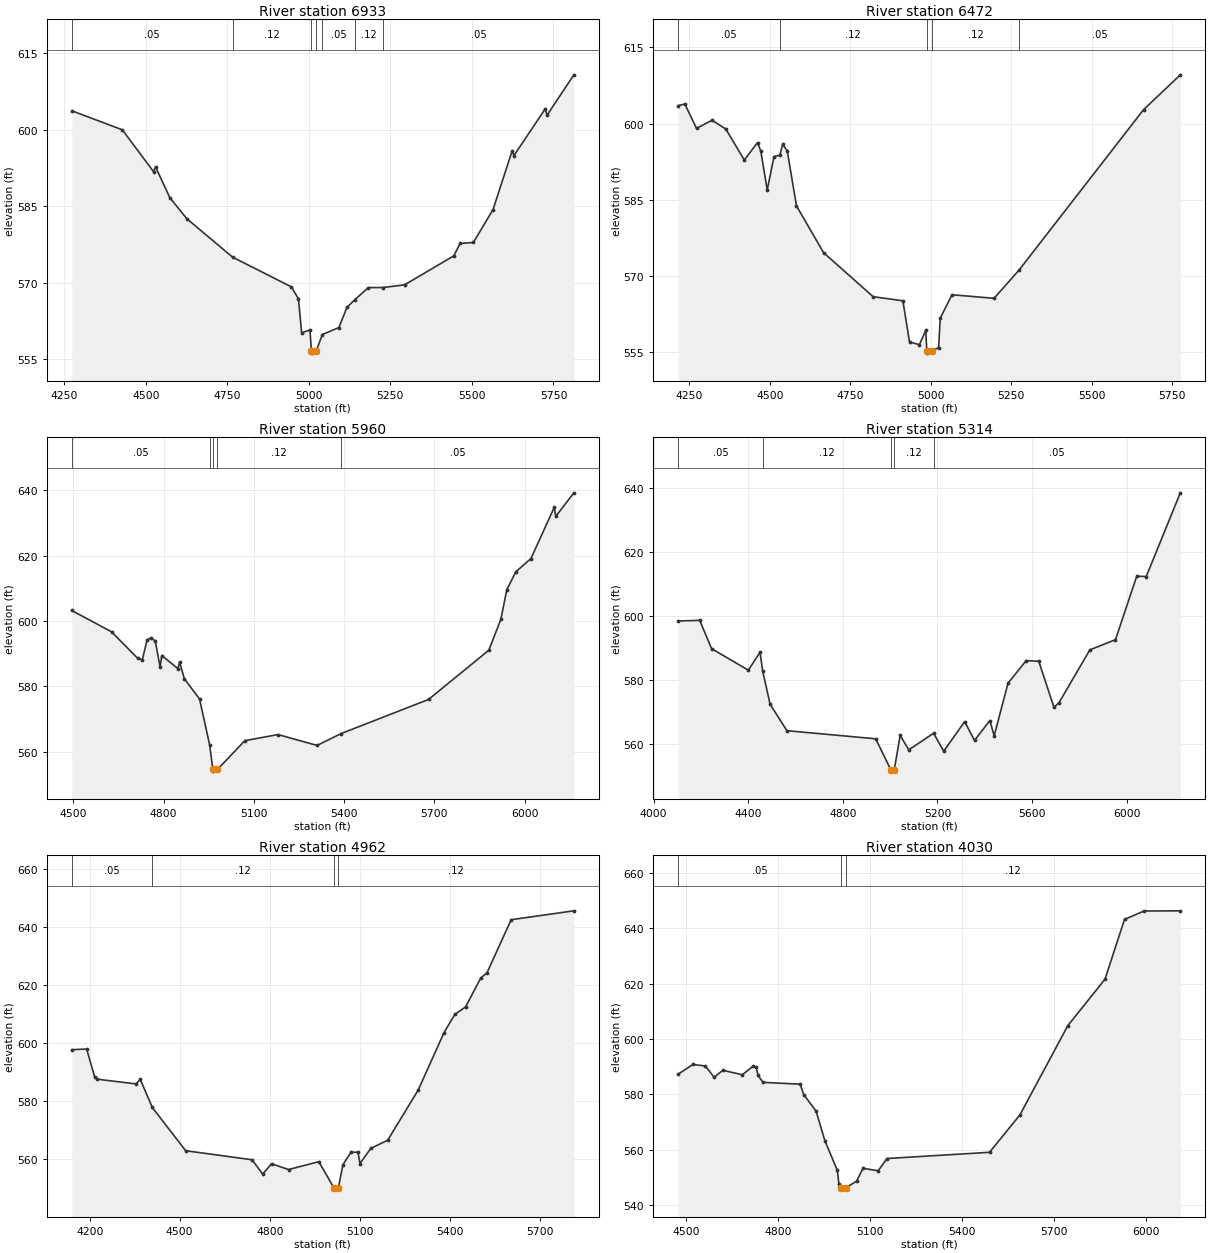
Type RM Length L Ch R = 1 ,6933    ,461,461,461
BEGIN DESCRIPTION:
Graham Branch 13.0
END DESCRIPTION:
XS GIS Cut Line= 3
      2361948.37      7069882.92      2361320.99      7069516.38
      2360512.39      7069436.88
#Sta/Elev= 30
  4273.4  603.74  4428.4  600.01  4524.3  591.78  4530.1  592.76  4573.8  586.71
    4626  582.58  4766.4  575.03  4946.7  569.21  4968.2  566.85  4978.1  560.18
  5003.5  560.76    5008  556.71    5010  556.21  5023.2  556.71  5041.7  559.86
  5092.4  561.23  5116.9  565.19    5141  566.68  5182.9  569.06  5227.8  569.08
  5293.4   569.6  5444.1  575.27  5464.2  577.73  5504.4  577.91  5564.7  584.35
  5623.6  595.93  5628.7  594.94    5725  604.14    5730  602.84  5812.5  610.79
#Mann= 7 ,-1 , 0
  4273.4     .05       0  4766.4     .12       0    5008     .07       0
  5023.2     .12       0  5041.7     .05       0    5141     .12       0
  5227.8     .05       0
Bank Sta=5008,5023.2
XS Rating Curve= 0 ,0
Exp/Cntr=0.3,0.1

Type RM Length L Ch R = 1 ,6472    ,512,512,512
BEGIN DESCRIPTION:
Graham Branch 12.0
END DESCRIPTION:
XS GIS Cut Line= 3
      2362049.01      7069337.76      2361284.37      7069162.36
      2360513.19      7069236.13
#Sta/Elev= 30
  4215.5  603.53    4236  603.83  4272.3  599.06  4320.3  600.64  4363.2  598.93
  4420.7  592.82  4461.7  596.25    4472  594.57  4491.8  586.93    4513  593.51
  4531.1  593.77  4539.8  595.92  4554.1  594.63  4582.7  583.81  4666.9   574.6
  4820.8  565.95  4913.2  565.14  4933.7  557.05  4964.5  556.51    4984  559.31
  4987.5  555.35  4989.5  554.85  5002.7  555.35  5024.1  555.92  5029.1  561.71
  5065.7  566.33  5196.3  565.63    5274  571.19  5660.6  602.73  5774.7  609.58
#Mann= 5 ,-1 , 0
  4215.5     .05       0  4531.1     .12       0  4987.5     .07       0
  5002.7     .12       0    5274     .05       0
Bank Sta=4987.5,5002.7
XS Rating Curve= 0 ,0
Exp/Cntr=0.3,0.1

Type RM Length L Ch R = 1 ,5960    ,646,646,646
BEGIN DESCRIPTION:
Graham Branch 11.0
END DESCRIPTION:
XS GIS Cut Line= 3
      2361968.16       7069100.8      2361529.12      7068850.87
      2360366.52      7068908.08
#Sta/Elev= 30
  4494.8  603.26    4627  596.74  4713.4  588.67  4729.3  588.16  4745.2  594.28
  4758.5  594.88  4772.5  593.92  4788.4  585.92  4794.1  589.48  4847.5  585.48
  4853.2  587.47  4869.1  582.36  4919.6  576.17  4953.3  562.06  4963.8  554.59
  4965.8  554.09    4979  554.59  5070.2  563.41  5180.3  565.28  5310.5  561.96
  5390.4  565.59  5680.9  576.03  5881.2  591.09  5921.2  600.51  5941.3  609.67
  5971.3  615.12  6021.4  619.17  6098.9  634.84  6103.9  632.06    6164  639.28
#Mann= 5 ,-1 , 0
  4494.8     .05       0  4953.3     .12       0  4963.8     .07       0
    4979     .12       0  5390.4     .05       0
Bank Sta=4963.8,4979
XS Rating Curve= 0 ,0
Exp/Cntr=0.3,0.1

Type RM Length L Ch R = 1 ,5314    ,352,352,352
BEGIN DESCRIPTION:
Graham Branch 10.0
END DESCRIPTION:
XS GIS Cut Line= 3
       2362044.7      7068942.81      2361378.04       7068344.6
      2360246.02      7067873.32
#Sta/Elev= 30
  4104.3  598.43  4195.1  598.63  4245.2  589.77  4400.7  583.03    4450  588.66
    4461  582.83  4492.6  572.36  4563.6  564.09  4938.9  561.55  5002.1  551.93
  5004.1  551.43  5017.5  551.93  5042.3  562.62  5078.6  558.08  5183.3  563.29
  5226.4  557.67  5314.8  566.94  5356.4  561.04  5421.4  567.27  5439.5  562.48
    5498  578.94  5574.9  586.03    5628  585.82  5692.2   571.4  5713.9  572.91
  5843.9  589.39  5952.2  592.58    6042  612.45  6082.2  612.35  6226.2  638.55
#Mann= 5 ,-1 , 0
  4104.3     .05       0    4461     .12       0  5002.1     .07       0
  5017.5     .12       0  5183.3     .05       0
Bank Sta=5002.1,5017.5
XS Rating Curve= 0 ,0
Exp/Cntr=0.3,0.1

Type RM Length L Ch R = 1 ,4962    ,932,932,932
BEGIN DESCRIPTION:
Graham Branch 9.0
END DESCRIPTION:
XS GIS Cut Line= 3
      2362086.37      7068800.46      2361591.65       7068097.5
      2361128.03      7067428.92
#Sta/Elev= 30
  4140.4  597.71  4189.9  597.96  4217.2  588.19  4225.9  587.56    4354  585.95
  4368.8  587.47  4408.7  577.85    4520  562.96  4740.8  559.85  4776.8  554.94
  4806.1  558.48  4862.7  556.48  4963.8  559.19  5013.6  550.24  5015.6  549.74
    5029  550.24    5044  558.13  5071.1   562.5  5094.3   562.4  5100.8  558.53
  5136.6  563.73  5193.3  566.59  5294.7  583.79  5381.1  603.63  5416.9  609.85
  5452.7  612.44  5503.4  622.39  5524.3  624.21  5604.7  642.45  5813.6   645.5
#Mann= 4 ,-1 , 0
  4140.4     .05       0  4408.7     .12       0  5013.6     .07       0
    5029     .12       0
Bank Sta=5013.6,5029
XS Rating Curve= 0 ,0
Exp/Cntr=0.3,0.1

Type RM Length L Ch R = 1 ,4030    ,649,649,649
BEGIN DESCRIPTION:
Graham Branch 8.0
END DESCRIPTION:
XS GIS Cut Line= 3
      2362343.31      7068630.33      2362123.39      7068154.38
       2361405.8      7067307.39
#Sta/Elev= 30
  4475.7  587.31  4523.7  590.79    4564  590.24  4592.5  586.17  4620.9  588.68
  4684.2  587.08  4718.4  590.08  4729.4  589.92  4735.6  586.84  4751.5  584.33
  4872.6  583.67  4884.2   579.9  4924.6   573.9  4953.1  563.22  4993.4  552.58
  4998.9   547.5  5005.7  546.24  5007.7  545.74  5021.2  546.24  5056.3  548.61
  5077.1  553.28  5126.5  552.36  5155.1   556.8  5489.1  559.05  5587.9  572.56
  5743.9  604.82  5864.8  621.59  5928.5  643.22  5992.2  646.26  6110.1  646.32
#Mann= 3 ,-1 , 0
  4475.7     .05       0  5005.7    .033       0  5021.2     .12       0
Bank Sta=5005.7,5021.2
XS Rating Curve= 0 ,0
Exp/Cntr=0.3,0.1