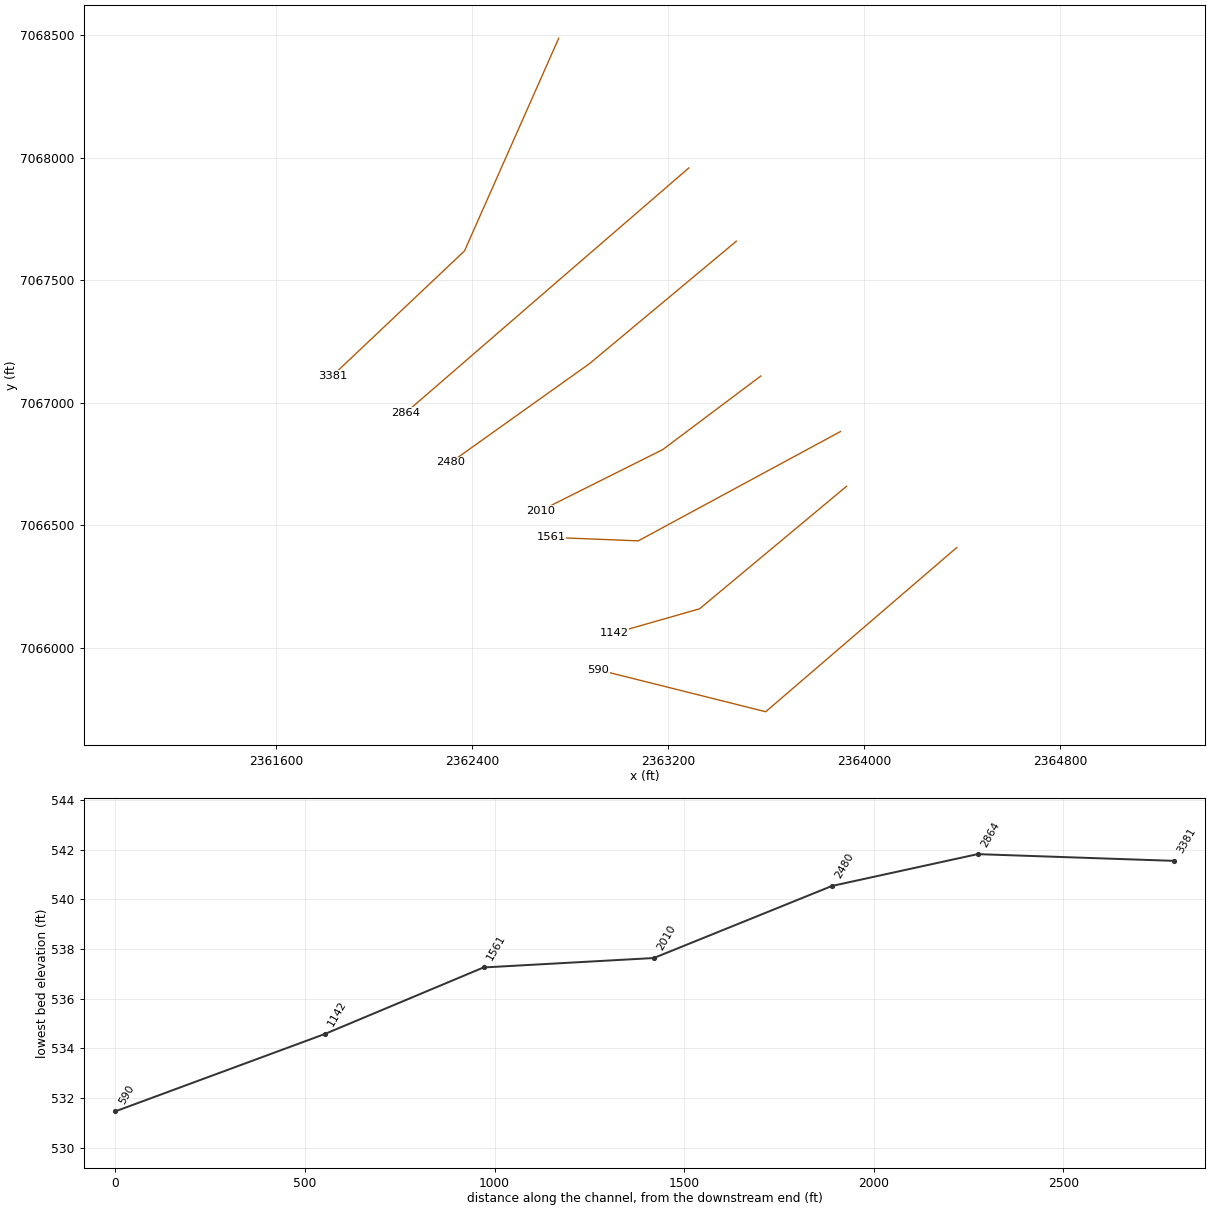
HEC-RAS study Graham Branch.prj: Graham Branch Base Level Engineering

--- Graham Branch.g01 (geometry) --- (continued)

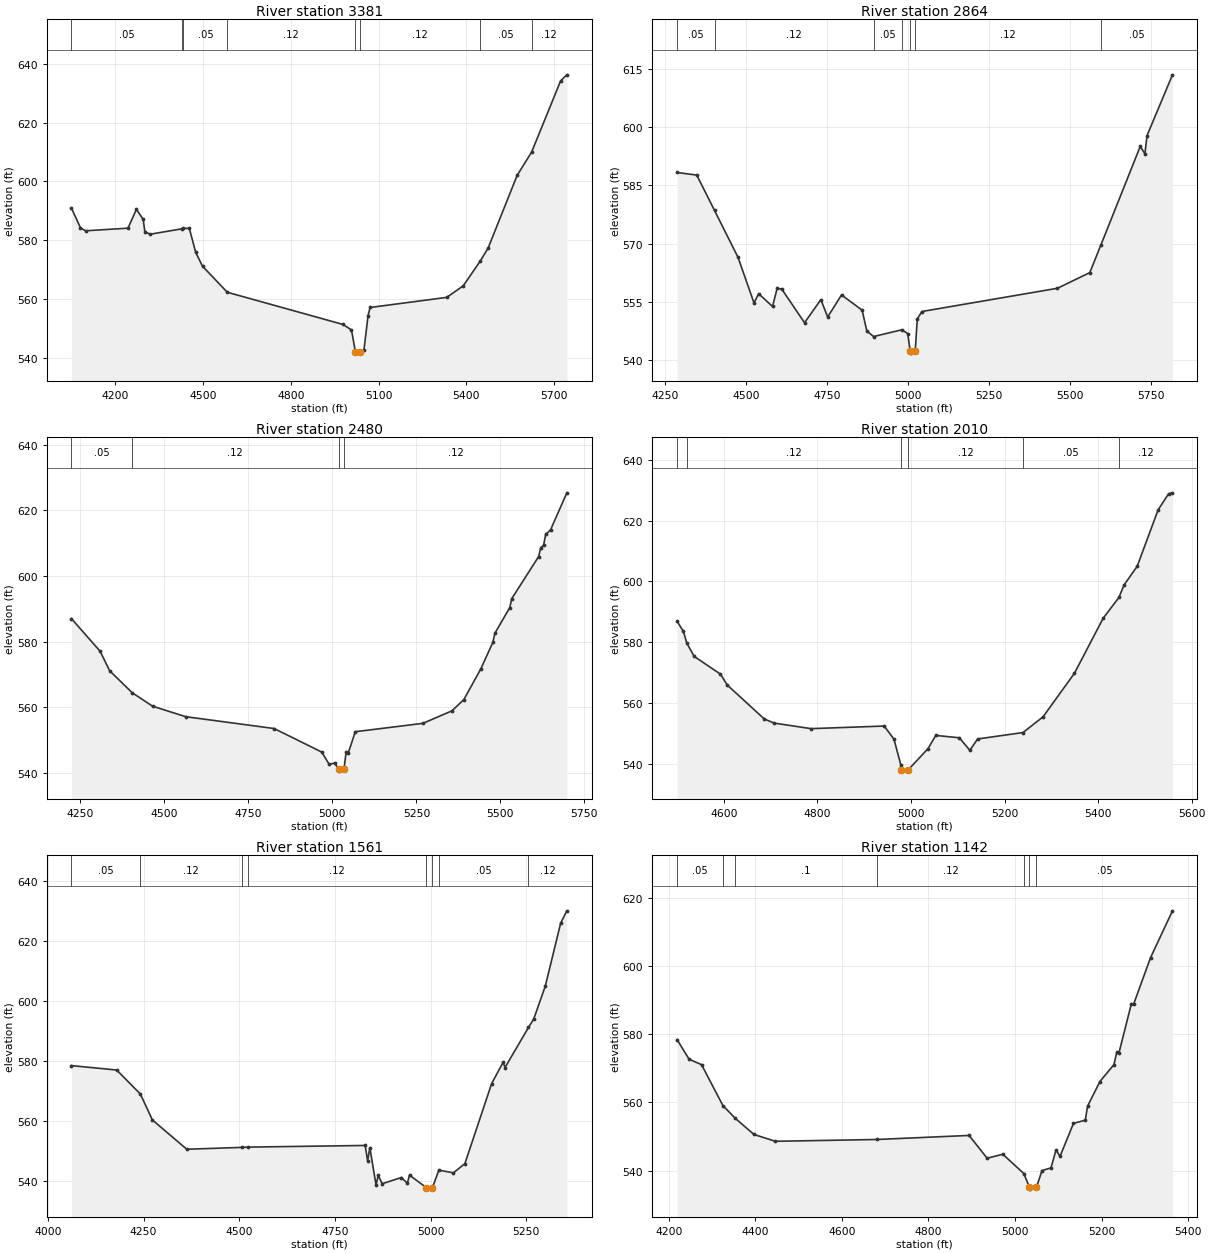
Type RM Length L Ch R = 1 ,3381    ,517,517,517
BEGIN DESCRIPTION:
Graham Branch 7.0
END DESCRIPTION:
XS GIS Cut Line= 3
       2362753.8      7068488.21      2362369.19      7067620.42
        2361829.        7067110.
#Sta/Elev= 30
  4050.8  590.93  4081.7  584.23  4098.9   583.2    4244   584.1  4272.8  590.51
    4296  587.07  4301.5  582.93  4319.3  582.03  4427.1  583.86  4433.4  584.05
  4453.6     584  4475.4  575.82  4498.7  571.13  4583.3  562.27  4978.6  551.31
  5007.5  549.43  5020.8  542.05  5022.8  541.55  5036.4  542.05    5050  542.56
  5064.2  554.31    5071  557.09  5332.8  560.53  5389.4  564.47  5448.2  573.02
  5474.4  577.36  5573.5  602.09  5622.9  610.01    5722  634.26  5743.2  636.31
#Mann= 8 ,-1 , 0
  4050.8     .05       0  4427.1     .12       0  4433.4     .05       0
  4583.3     .12       0  5020.8     .07       0  5036.4     .12       0
  5448.2     .05       0  5622.9     .12       0
Bank Sta=5020.8,5036.4
XS Rating Curve= 0 ,0
Exp/Cntr=0.3,0.1

Type RM Length L Ch R = 1 ,2864    ,384,384,384
BEGIN DESCRIPTION:
Graham Branch 6.0
END DESCRIPTION:
XS GIS Cut Line= 3
      2363284.96      7067958.95      2362745.46      7067493.25
      2362128.99      7066959.99
#Sta/Elev= 30
  4287.3  588.34    4348  587.67  4402.8  578.57  4475.3  566.49  4524.6  554.74
  4538.9  557.13  4581.7  553.83  4595.9   558.5  4610.2   558.3  4680.4  549.65
  4730.8   555.6  4751.7  551.12  4794.5  556.81  4858.1  552.87  4872.4  547.54
  4893.4  546.09  4980.8  547.84  4998.7  546.84  5006.1  542.32  5008.1  541.82
  5021.7  542.32  5028.1  550.62  5042.4  552.54  5460.3  558.52  5560.1  562.55
  5593.9  569.57  5715.8  595.07  5730.1  593.14  5736.7  597.85  5815.1  613.49
#Mann= 7 ,-1 , 0
  4287.3     .05       0  4402.8     .12       0  4893.4     .05       0
  4980.8     .12       0  5006.1     .07       0  5021.7     .12       0
  5593.9     .05       0
Bank Sta=5006.1,5021.7
XS Rating Curve= 0 ,0
Exp/Cntr=0.3,0.1

Type RM Length L Ch R = 1 ,2480    ,470,470,470
BEGIN DESCRIPTION:
Graham Branch 5.0
END DESCRIPTION:
XS GIS Cut Line= 3
      2363478.98      7067659.98        2362879.        7067160.
      2362313.76      7066757.67
#Sta/Elev= 30
  4223.1  587.02  4308.3   577.1    4337  571.12  4403.9  564.45  4464.5  560.34
  4563.5  557.13  4826.4  553.53  4968.3  546.35  4990.4  542.61  5007.2  543.02
  5018.2  541.04  5020.2  540.54  5034.3  541.04  5040.9  546.37  5047.1  546.01
    5068  552.55  5269.7  555.11  5355.8  558.92  5391.4  562.36  5441.8  571.71
  5477.5  579.76  5483.6  582.54  5527.9  590.37    5534  593.13    5614  605.96
  5620.1  608.59  5628.7  609.38  5634.9  612.67  5649.6  614.13  5697.9  625.37
#Mann= 4 ,-1 , 0
  4223.1     .05       0  4403.9     .12       0  5018.2     .07       0
  5034.3     .12       0
Bank Sta=5018.2,5034.3
XS Rating Curve= 0 ,0
Exp/Cntr=0.3,0.1

Type RM Length L Ch R = 1 ,2010    ,449,449,449
BEGIN DESCRIPTION:
Graham Branch 4.0
END DESCRIPTION:
XS GIS Cut Line= 3
      2363579.02      7067110.02        2363179.        7066810.
      2362679.04      7066560.02
#Sta/Elev= 30
    4500  586.93  4513.6  583.56  4520.8  579.73  4536.5  575.38  4592.7  569.54
  4607.3  565.95  4686.5  554.79  4707.3  553.44  4786.5  551.61  4942.7  552.47
  4963.6  548.17  4978.2  539.78  4978.4  538.14  4980.4  537.64  4994.5  538.14
  5036.4  545.03  5053.1  549.38  5103.4  548.61  5125.8   544.5  5142.6  548.22
  5239.4  550.32  5282.3  555.49  5349.4  569.81  5410.9  587.93  5444.5  594.74
  5455.6  598.88  5483.6     605  5528.3  623.55  5550.7  628.84    5559  629.16
#Mann= 6 ,-1 , 0
    4500     .05       0  4520.8     .12       0  4978.4     .07       0
  4994.5     .12       0  5239.4     .05       0  5444.5     .12       0
Bank Sta=4978.4,4994.5
XS Rating Curve= 0 ,0
Exp/Cntr=0.3,0.1

Type RM Length L Ch R = 1 ,1561    ,419,419,419
BEGIN DESCRIPTION:
Graham Branch 3.0
END DESCRIPTION:
XS GIS Cut Line= 3
      2363904.21      7066883.35      2363078.52      7066437.24
       2362722.8      7066451.46
#Sta/Elev= 30
  4061.5  578.41  4179.8  576.94  4241.6  568.94    4273  560.31  4362.9  550.55
  4506.4  551.16  4523.1  551.26    4829  551.81  4835.5  546.66  4841.2  551.08
  4857.4  538.64  4863.1  541.81  4873.6  539.05  4923.1  541.11  4939.3  539.27
  4944.9  541.92  4988.8  537.76  4990.8  537.26  5004.9  537.76  5021.5  543.57
  5059.6   542.7  5089.6  545.75  5159.6  572.45  5189.5  579.52  5194.5  577.78
  5255.8  591.14  5269.7  594.01  5299.8  604.93  5339.8  625.85    5356  629.98
#Mann= 8 ,-1 , 0
  4061.5     .05       0  4241.6     .12       0  4506.4      .1       0
  4523.1     .12       0  4988.8     .07       0  5004.9     .12       0
  5021.5     .05       0  5255.8     .12       0
Bank Sta=4988.8,5004.9
XS Rating Curve= 0 ,0
Exp/Cntr=0.3,0.1

Type RM Length L Ch R = 1 ,1142    ,552,552,552
BEGIN DESCRIPTION:
Graham Branch 2.0
END DESCRIPTION:
XS GIS Cut Line= 3
      2363928.98      7066659.98        2363329.        7066160.
        2362979.        7066060.
#Sta/Elev= 30
    4219  578.43    4247  572.65  4275.6  571.09  4324.9   559.1  4353.9  555.31
  4396.7  550.62  4446.1  548.61  4680.9  549.14  4893.9  550.33  4935.6  543.65
    4972  544.81  5020.6  539.13  5033.5  535.08  5035.5  534.58  5049.6  535.08
  5062.4  540.02  5083.2  540.81  5094.9  546.09    5104  544.17  5135.2  553.86
  5162.5  554.81  5167.7  558.89  5196.3  566.14  5228.8  571.11  5235.3  574.79
  5240.5  574.63  5269.1     589  5274.3  588.85  5313.3  602.47    5364  616.21
#Mann= 7 ,-1 , 0
    4219     .05       0  4324.9     .12       0  4353.9      .1       0
  4680.9     .12       0  5020.6     .05       0  5033.5     .07       0
  5049.6     .05       0
Bank Sta=5033.5,5049.6
XS Rating Curve= 0 ,0
Exp/Cntr=0.3,0.1

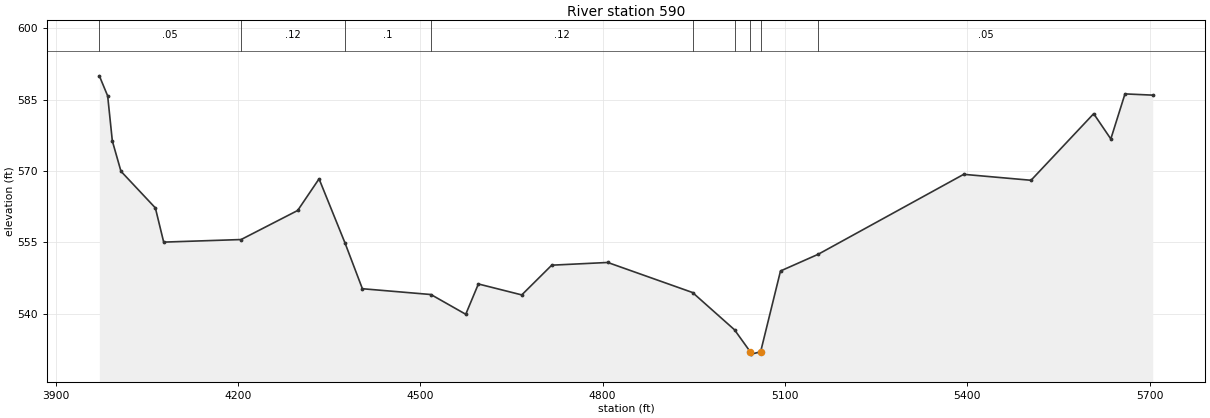
Type RM Length L Ch R = 1 ,590     ,0,0,0
BEGIN DESCRIPTION:
Graham Branch 1.0
END DESCRIPTION:
XS GIS Cut Line= 3
      2364378.97      7066409.98      2363598.92      7065739.97
       2362914.7      7065911.13
#Sta/Elev= 30
  3971.7  589.98  3985.4  585.76  3993.1  576.28  4007.3  569.91  4063.9  562.21
  4077.6  555.02    4205  555.56  4298.1  561.67  4333.3  568.32    4376  554.84
  4404.6  545.22  4517.4     544  4574.7  539.85  4595.5  546.22  4666.9  543.92
  4716.2  550.17  4808.4  550.74    4948  544.42    5017  536.59  5042.9  531.97
  5044.9  531.47    5060  531.97  5092.7  548.95  5154.7  552.46  5394.2  569.27
    5505  568.02  5608.1  582.02  5636.3  576.71  5659.6  586.18  5705.3  585.92
#Mann= 9 ,-1 , 0
  3971.7     .05       0    4205     .12       0    4376      .1       0
  4517.4     .12       0    4948      .1       0    5017     .12       0
  5042.9     .07       0    5060     .12       0  5154.7     .05       0
Bank Sta=5042.9,5060
XS Rating Curve= 0 ,0
Exp/Cntr=0.3,0.1

Chan Stop Cuts=-1
Use User Specified Reach Order=0
Composite Channel Slope=5