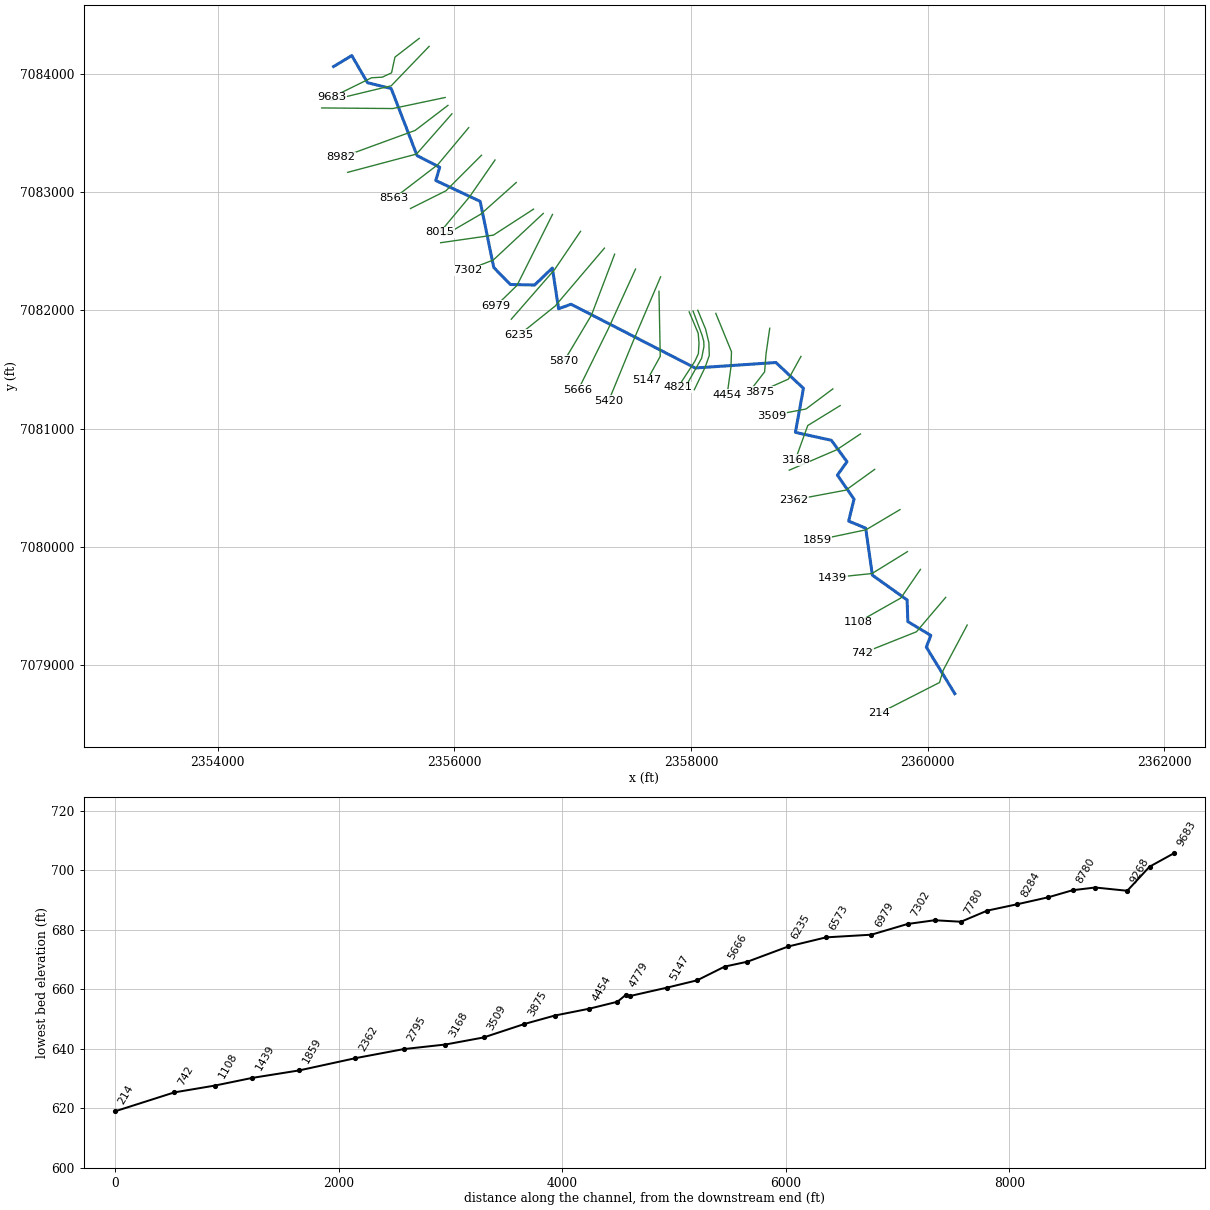
--- Graham Branch Tr 10.prj (project) ---

Proj Title=Graham Branch Tr 10 Base Level Engineering
Current Plan=p01
Default Exp/Contr=0.3,0.1
English Units
Geom File=g01
Flow File=f01
Plan File=p01
BEGIN DESCRIPTION:
Graham Branch Tr 10
END DESCRIPTION:

--- Graham Branch Tr 10.p01 (plan) ---

Plan Title=Multiple Run
Short Identifier=Multiple
Geom File=g01
Flow File=f01
Subcritical Flow
K Sum by GR= 0
Std Step Tol= 0.01
Critical Tol= 0.01
Num of Std Step Trials= 20
Max Error Tol= 0.3
Flow Tol Ratio= 0.001
Split Flow NTrial= 30
Split Flow Tol= 0.02
Split Flow Ratio= 0.02
Log Output Level= 0
Friction Slope Method= 1
Unsteady Friction Slope Method= 2
Unsteady Bridges Friction Slope Method= 1
Parabolic Critical Depth
Global Vel Dist=  1 , 1 , 1
Global Log Level= 0
CheckData=True
Encroach Param= -1, 0, 0, 0
BEGIN DESCRIPTION:
Multiple Run
END DESCRIPTION:

--- Graham Branch Tr 10.f01 (steady flow) ---

Flow Title=Multiple
Number of Profiles=7
Profile Names=10-year,25-year,50-year,1pct_min,100-year,1pct_plu,500-year
River Rch & RM= Graham Branch Tr,Reach-1,9683
     216     275     320     186     371     740     498
River Rch & RM= Graham Branch Tr,Reach-1,8284
     361     476     568     337     673    1343     945
River Rch & RM= Graham Branch Tr,Reach-1,4146
     568     772     939     568    1133    2260    1648
Boundary for River Rch & Prof#=Graham Branch Tr,Reach-1,1
Up Type=0
Dn Type=3
Dn Slope=0.005
Boundary for River Rch & Prof#=Graham Branch Tr,Reach-1,2
Up Type=0
Dn Type=3
Dn Slope=0.005
Boundary for River Rch & Prof#=Graham Branch Tr,Reach-1,3
Up Type=0
Dn Type=3
Dn Slope=0.005
Boundary for River Rch & Prof#=Graham Branch Tr,Reach-1,4
Up Type=0
Dn Type=3
Dn Slope=0.005
Boundary for River Rch & Prof#=Graham Branch Tr,Reach-1,5
Up Type=0
Dn Type=3
Dn Slope=0.005
Boundary for River Rch & Prof#=Graham Branch Tr,Reach-1,6
Up Type=0
Dn Type=3
Dn Slope=0.005
Boundary for River Rch & Prof#=Graham Branch Tr,Reach-1,7
Up Type=0
Dn Type=3
Dn Slope=0.005

--- Graham Branch Tr 10.g01 (geometry) ---

Geom Title=Existing Conditions

River Reach=Graham Branch Tr,Reach-1
Reach XY= 30
      2354979.00      7084060.00      2355132.62      7084152.54
      2355265.65      7083923.36      2355465.80      7083873.74
      2355684.34      7083307.26      2355875.94      7083208.60
      2355842.54      7083096.62      2356217.89      7082920.32
      2356332.61      7082361.50      2356472.81      7082217.81
      2356677.75      7082213.45      2356827.80      7082356.92
      2356880.40      7082013.06      2356985.72      7082050.83
      2358034.86      7081512.06      2358717.17      7081558.38
      2358949.97      7081340.09      2358881.84      7080968.01
      2359186.01      7080900.97      2359318.02      7080719.99
      2359236.85      7080606.77      2359377.47      7080403.60
      2359331.92      7080217.99      2359475.94      7080158.59
      2359532.45      7079761.25      2359825.93      7079551.70
      2359832.40      7079368.44      2360026.46      7079251.83
      2359988.18      7079153.30      2360229.00      7078760.00

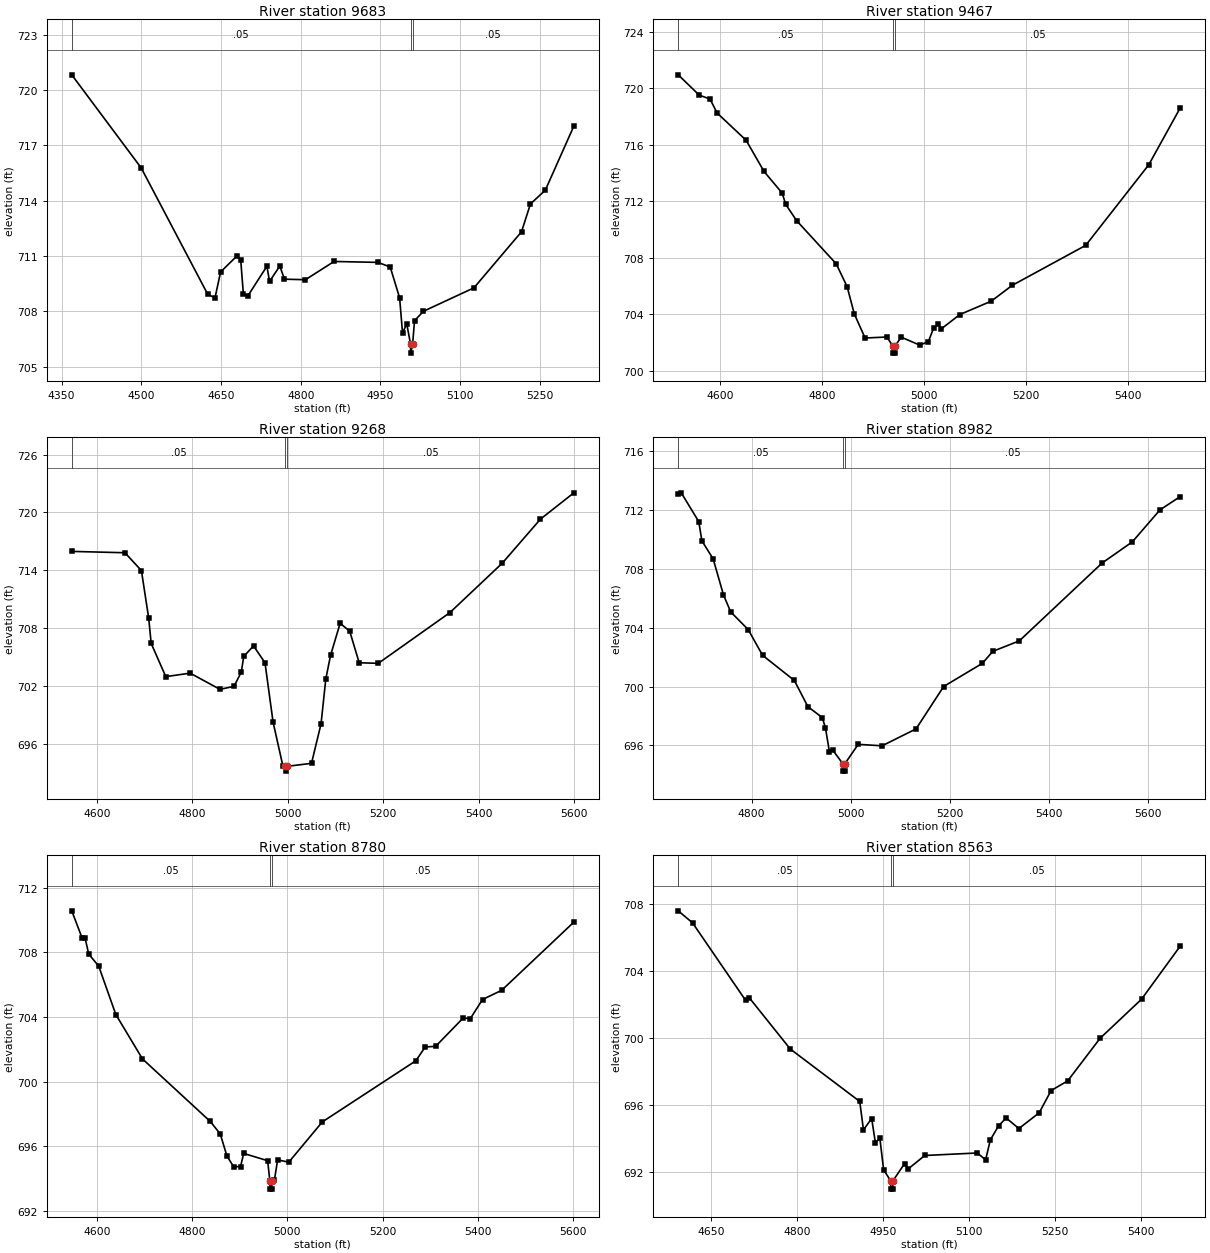
Type RM Length L Ch R = 1,9683,216,216,216
BEGIN DESCRIPTION:
Mapping XS e9731fae
END DESCRIPTION:
XS GIS Cut Line= 6
      2355703.13      7084298.21      2355497.43      7084139.38
      2355468.78      7084006.56      2355390.66      7083970.11
      2355299.51      7083964.90      2354966.13      7083800.81
#Sta/Elev= 30
  4369.1  720.82  4499.8  715.77  4624.8  708.93  4638.6  708.72  4649.2  710.13
  4679.6  710.99  4687.0  710.80  4692.1  708.92  4700.2  708.82  4736.3  710.44
  4741.3  709.62  4760.6  710.45  4769.4  709.74  4808.8  709.71  4862.8  710.70
  4945.4  710.65  4968.4  710.40  4986.1  708.73  4991.6  706.82  4999.5  707.32
  5006.6  706.23  5006.9  705.73  5010.6  706.23  5014.2  707.49  5031.0  708.00
  5126.0  709.27  5215.5  712.31  5232.3  713.82  5260.2  714.56  5314.0  718.04
#Mann=3,-1,0
  4369.1    0.05       0  5006.6   0.033       0  5010.6    0.05       0
Bank Sta=5006.6,5010.6
Exp/Cntr=0.3,0.1

Type RM Length L Ch R = 1,9467,199,199,199
BEGIN DESCRIPTION:
Mapping XS 09ec12ad
END DESCRIPTION:
XS GIS Cut Line= 3
      2355786.50      7084230.53      2355466.18      7083897.19
      2354958.81      7083774.90
#Sta/Elev= 30
  4518.4  720.95  4559.6  719.51  4580.6  719.24  4594.8  718.24  4651.4  716.32
  4686.6  714.11  4722.1  712.58  4729.1  711.78  4750.4  710.63  4828.1  707.57
  4849.5  705.95  4863.6  704.02  4884.7  702.32  4927.2  702.39  4939.3  701.75
  4939.6  701.25  4943.1  701.25  4943.3  701.75  4955.5  702.38  4991.6  701.82
  5008.7  702.06  5018.9  703.01  5028.4  703.30  5033.5  702.95  5070.3  703.98
  5132.1  704.93  5173.2  706.05  5317.2  708.88  5440.7  714.58  5502.6  718.62
#Mann=3,-1,0
  4518.4    0.05       0  4939.3   0.033       0  4943.3    0.05       0
Bank Sta=4939.3,4943.3
Exp/Cntr=0.3,0.1

Type RM Length L Ch R = 1,9268,286,286,286
BEGIN DESCRIPTION:
Graham Branch Tr 10 29.0
END DESCRIPTION:
XS GIS Cut Line= 3
      2355921.89      7083798.23      2355478.53      7083704.80
      2354879.05      7083710.00
#Sta/Elev= 30
  4546.9  715.96  4658.4  715.82  4692.9  713.97  4708.2  709.02  4713.4  706.40
  4744.0  702.96  4795.1  703.32  4857.6  701.64  4887.1  701.95  4902.2  703.43
  4907.5  705.06  4928.0  706.15  4952.0  704.40  4968.9  698.25  4989.3  693.73
  4994.7  693.65  4995.0  693.15  4998.7  693.65  5049.5  693.96  5069.5  698.06
  5079.5  702.72  5089.5  705.18  5109.5  708.49  5129.5  707.69  5149.5  704.40
  5189.5  704.34  5339.5  709.60  5449.5  714.74  5529.5  719.31  5599.5  722.04
#Mann=3,-1,0
  4546.9    0.05       0  4994.7   0.033       0  4998.7    0.05       0
Bank Sta=4994.7,4998.7
Exp/Cntr=0.3,0.1

Type RM Length L Ch R = 1,8982,202,202,202
BEGIN DESCRIPTION:
Graham Branch Tr 10 28.0
END DESCRIPTION:
XS GIS Cut Line= 3
      2355945.28      7083731.44      2355668.66      7083520.12
      2355043.53      7083291.57
#Sta/Elev= 30
  4651.9  713.09  4658.0  713.16  4693.4  711.20  4699.6  709.90  4722.4  708.67
  4743.2  706.23  4757.8  705.07  4793.1  703.87  4822.2  702.12  4886.3  700.41
  4913.7  698.63  4942.7  697.89  4949.2  697.18  4957.3  695.53  4963.6  695.69
  4984.3  694.75  4984.6  694.25  4988.1  694.25  4988.3  694.75  5015.3  696.07
  5063.5  695.97  5132.1  697.12  5187.8  700.00  5265.8  701.57  5287.1  702.39
  5340.5  703.10  5507.7  708.39  5568.8  709.83  5624.5  712.00  5665.6  712.91
#Mann=3,-1,0
  4651.9    0.05       0  4984.3   0.033       0  4988.3    0.05       0
Bank Sta=4984.3,4988.3
Exp/Cntr=0.3,0.1

Type RM Length L Ch R = 1,8780,217,217,217
BEGIN DESCRIPTION:
Graham Branch Tr 10 27.0
END DESCRIPTION:
XS GIS Cut Line= 3
      2355979.01      7083660.01      2355679.98      7083320.27
      2355098.54      7083165.84
#Sta/Elev= 30
  4547.4  710.58  4568.8  708.92  4575.4  708.89  4583.0  707.90  4603.9  707.16
  4639.9  704.16  4695.9  701.41  4838.2  697.54  4859.1  696.77  4873.3  695.39
  4887.5  694.73  4901.8  694.75  4908.4  695.56  4958.7  695.11  4963.3  693.85
  4963.6  693.35  4967.1  693.35  4967.3  693.85  4972.9  693.91  4979.6  695.16
  5003.1  695.02  5073.4  697.51  5270.0  701.30  5289.4  702.15  5311.4  702.19
  5369.7  703.96  5383.8  703.89  5409.9  705.09  5450.1  705.66  5601.6  709.88
#Mann=3,-1,0
  4547.4    0.05       0  4963.3   0.033       0  4967.3    0.05       0
Bank Sta=4963.3,4967.3
Exp/Cntr=0.3,0.1

Type RM Length L Ch R = 1,8563,279,279,279
BEGIN DESCRIPTION:
Graham Branch Tr 10 26.0
END DESCRIPTION:
XS GIS Cut Line= 3
      2356120.67      7083543.46      2355859.77      7083230.57
      2355487.87      7082945.80
#Sta/Elev= 30
  4592.6  707.61  4617.6  706.89  4710.1  702.26  4716.6  702.41  4788.1  699.35
  4909.2  696.22  4915.7  694.52  4930.0  695.20  4936.5  693.75  4944.3  694.02
  4950.9  692.13  4963.2  691.48  4963.4  690.98  4966.9  690.98  4967.2  691.48
  4987.3  692.50  4993.8  692.19  5022.7  692.99  5114.3  693.14  5128.8  692.73
  5137.0  693.92  5151.5  694.77  5164.7  695.23  5186.8  694.60  5222.2  695.54
  5243.0  696.87  5272.0  697.45  5328.4  699.99  5400.8  702.33  5468.4  705.51
#Mann=3,-1,0
  4592.6    0.05       0  4963.2   0.033       0  4967.2    0.05       0
Bank Sta=4963.2,4967.2
Exp/Cntr=0.3,0.1

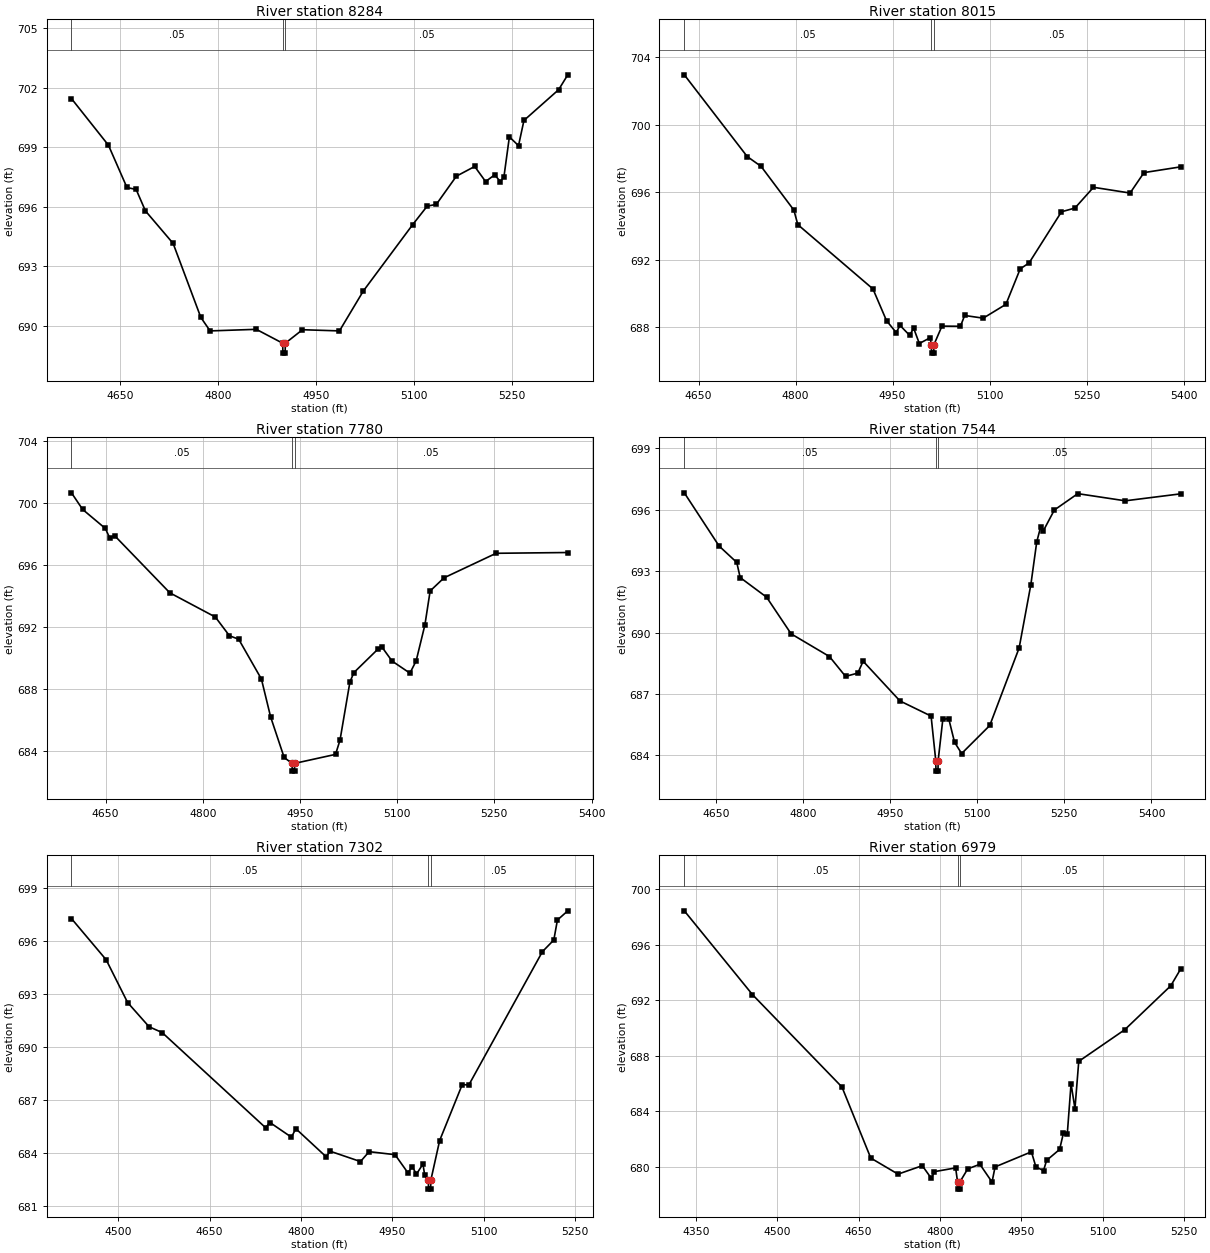
Type RM Length L Ch R = 1,8284,269,269,269
BEGIN DESCRIPTION:
Graham Branch Tr 10 25.0
END DESCRIPTION:
XS GIS Cut Line= 3
      2356229.03      7083310.03      2355929.00      7083010.00
      2355629.02      7082860.01
#Sta/Elev= 30
  4575.4  701.45  4632.0  699.10  4660.3  696.97  4674.4  696.87  4688.6  695.79
  4731.0  694.15  4773.4  690.42  4787.6  689.74  4858.3  689.82  4898.7  689.12
  4899.0  688.62  4902.5  688.62  4902.7  689.12  4929.0  689.80  4985.6  689.74
  5022.1  691.75  5097.5  695.09  5119.9  696.03  5133.9  696.12  5164.6  697.54
  5192.6  698.03  5209.3  697.27  5223.3  697.61  5231.7  697.27  5237.3  697.49
  5245.7  699.52  5259.7  699.08  5268.0  700.35  5321.1  701.90  5335.1  702.65
#Mann=3,-1,0
  4575.4    0.05       0  4898.7   0.033       0  4902.7    0.05       0
Bank Sta=4898.7,4902.7
Exp/Cntr=0.3,0.1

Type RM Length L Ch R = 1,8015,235,235,235
BEGIN DESCRIPTION:
Graham Branch Tr 10 24.0
END DESCRIPTION:
XS GIS Cut Line= 3
      2356343.32      7083270.02      2356129.00      7082960.00
      2355879.00      7082660.00
#Sta/Elev= 30
  4627.9  702.95  4725.2  698.11  4746.6  697.53  4797.3  694.94  4803.4  694.08
  4919.6  690.27  4940.6  688.39  4955.5  687.69  4961.5  688.11  4976.4  687.52
  4982.5  687.95  4991.3  687.04  5008.0  687.38  5009.9  686.97  5010.2  686.47
  5013.7  686.47  5013.9  686.97  5026.3  688.07  5054.9  688.06  5061.4  688.70
  5090.1  688.54  5125.2  689.36  5147.3  691.46  5161.0  691.81  5211.1  694.84
  5231.9  695.06  5260.6  696.29  5317.2  695.95  5338.7  697.16  5395.3  697.50
#Mann=3,-1,0
  4627.9    0.05       0  5009.9   0.033       0  5013.9    0.05       0
Bank Sta=5009.9,5013.9
Exp/Cntr=0.3,0.1

Type RM Length L Ch R = 1,7780,236,236,236
BEGIN DESCRIPTION:
Graham Branch Tr 10 23.0
END DESCRIPTION:
XS GIS Cut Line= 3
      2356522.97      7083079.88      2356222.47      7082811.96
      2355908.39      7082629.36
#Sta/Elev= 30
  4597.4  700.68  4614.6  699.61  4649.7  698.38  4656.4  697.77  4663.9  697.92
  4749.2  694.23  4819.4  692.67  4841.2  691.46  4855.4  691.24  4890.5  688.67
  4904.7  686.23  4925.6  683.61  4937.8  683.23  4938.1  682.73  4941.6  682.73
  4941.8  683.23  5004.9  683.81  5011.8  684.73  5027.1  688.48  5033.3  689.09
  5070.6  690.61  5076.4  690.74  5092.1  689.83  5119.7  689.05  5129.3  689.84
  5142.8  692.16  5150.9  694.35  5172.4  695.20  5252.7  696.78  5363.3  696.83
#Mann=3,-1,0
  4597.4    0.05       0  4937.8   0.033       0  4941.8    0.05       0
Bank Sta=4937.8,4941.8
Exp/Cntr=0.3,0.1

Type RM Length L Ch R = 1,7544,242,242,242
BEGIN DESCRIPTION:
Graham Branch Tr 10 22.0
END DESCRIPTION:
XS GIS Cut Line= 3
      2356668.84      7082854.65      2356329.41      7082635.01
      2355883.81      7082570.81
#Sta/Elev= 30
  4595.7  696.83  4655.6  694.23  4686.0  693.43  4691.9  692.69  4737.4  691.73
  4779.6  689.94  4845.6  688.83  4873.3  687.86  4894.4  688.02  4903.6  688.60
  4967.0  686.66  5020.6  685.92  5028.7  683.73  5029.0  683.23  5032.5  683.23
  5032.7  683.73  5040.8  685.76  5050.9  685.80  5061.0  684.64  5073.2  684.09
  5121.6  685.46  5172.2  689.25  5192.4  692.35  5202.5  694.43  5209.0  695.14
  5214.0  694.98  5232.8  695.99  5273.2  696.79  5354.9  696.44  5450.2  696.78
#Mann=3,-1,0
  4595.7    0.05       0  5028.7   0.033       0  5032.7    0.05       0
Bank Sta=5028.7,5032.7
Exp/Cntr=0.3,0.1

Type RM Length L Ch R = 1,7302,323,323,323
BEGIN DESCRIPTION:
Graham Branch Tr 10 21.0
END DESCRIPTION:
XS GIS Cut Line= 3
      2356750.90      7082818.22      2356329.13      7082425.06
      2356107.65      7082339.02
#Sta/Elev= 30
  4423.4  697.28  4480.3  694.95  4515.5  692.53  4550.7  691.16  4572.2  690.83
  4741.7  685.45  4749.0  685.74  4784.2  684.91  4791.5  685.39  4840.9  683.81
  4848.2  684.11  4897.5  683.53  4911.7  684.09  4954.2  683.92  4975.2  682.90
  4982.5  683.23  4989.4  682.82  5000.0  683.39  5002.8  682.78  5008.9  682.47
  5009.1  681.97  5012.6  681.97  5012.9  682.47  5027.4  684.72  5064.5  687.89
  5075.2  687.86  5196.0  695.41  5214.7  696.07  5220.6  697.20  5237.6  697.72
#Mann=3,-1,0
  4423.4    0.05       0  5008.9   0.033       0  5012.9    0.05       0
Bank Sta=5008.9,5012.9
Exp/Cntr=0.3,0.1

Type RM Length L Ch R = 1,6979,406,406,406
BEGIN DESCRIPTION:
Graham Branch Tr 10 20.0
END DESCRIPTION:
XS GIS Cut Line= 3
      2356828.98      7082809.97      2356529.00      7082210.00
      2356353.86      7082039.66
#Sta/Elev= 30
  4328.6  698.43  4454.3  692.39  4619.3  685.73  4672.4  680.61  4722.7  679.45
  4767.4  680.06  4784.2  679.14  4789.8  679.63  4828.9  679.90  4832.5  678.87
  4832.7  678.37  4836.2  678.37  4836.5  678.87  4851.2  679.83  4873.6  680.16
  4896.0  678.88  4901.6  679.97  4968.6  681.06  4977.0  679.96  4991.0  679.71
  4996.6  680.44  5020.6  681.23  5027.6  682.40  5034.7  682.31  5041.7  685.97
  5048.9  684.17  5055.9  687.58  5140.7  689.86  5225.6  693.03  5243.7  694.23
#Mann=3,-1,0
  4328.6    0.05       0  4832.5   0.033       0  4836.5    0.05       0
Bank Sta=4832.5,4836.5
Exp/Cntr=0.3,0.1

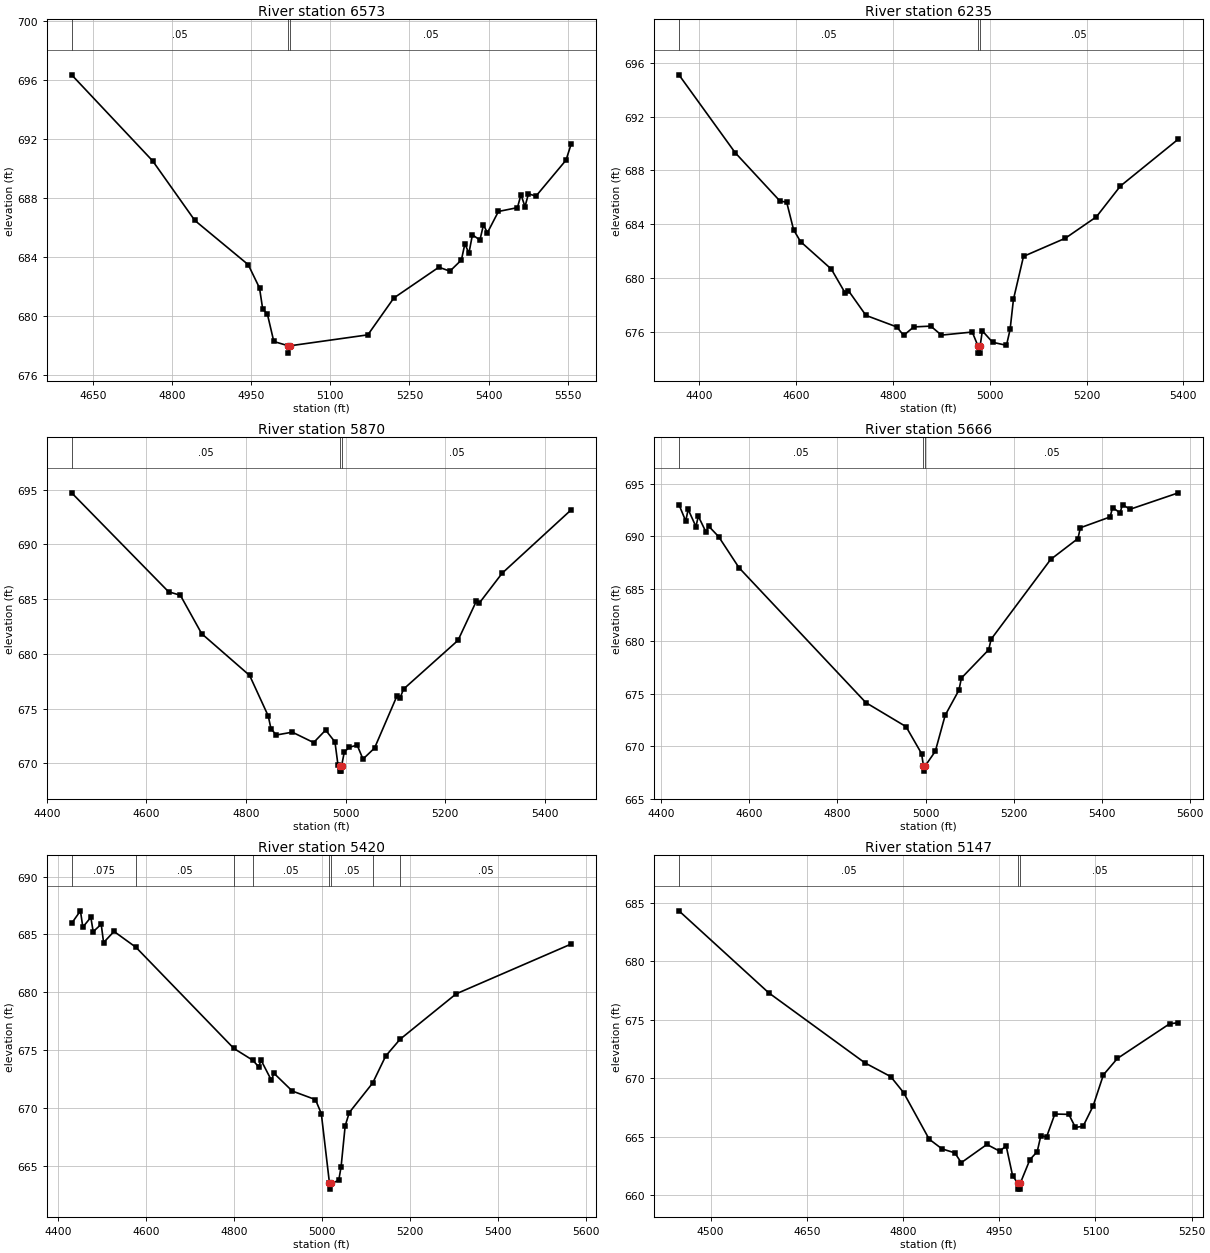
Type RM Length L Ch R = 1,6573,338,338,338
BEGIN DESCRIPTION:
Graham Branch Tr 10 19.0
END DESCRIPTION:
XS GIS Cut Line= 3
      2357066.00      7082667.18      2356846.55      7082343.81
      2356480.60      7081924.30
#Sta/Elev= 30
  4609.2  696.35  4762.9  690.51  4842.9  686.47  4944.2  683.47  4965.6  681.89
  4971.7  680.45  4980.4  680.14  4992.7  678.26  5020.0  677.97  5020.3  677.47
  5024.0  677.97  5171.1  678.71  5220.4  681.21  5305.9  683.30  5326.8  683.03
  5348.6  683.79  5355.2  684.89  5362.8  684.24  5369.5  685.50  5383.7  685.14
  5390.4  686.16  5398.0  685.64  5418.8  687.08  5454.9  687.34  5461.6  688.22
  5469.2  687.41  5475.8  688.28  5490.0  688.12  5547.0  690.56  5556.7  691.64
#Mann=3,-1,0
  4609.2    0.05       0  5020.0   0.033       0  5024.0    0.05       0
Bank Sta=5020,5024
Exp/Cntr=0.3,0.1

Type RM Length L Ch R = 1,6235,365,365,365
BEGIN DESCRIPTION:
Graham Branch Tr 10 18.0
END DESCRIPTION:
XS GIS Cut Line= 3
      2357267.76      7082525.18      2356851.70      7082035.85
      2356547.74      7081792.14
#Sta/Elev= 30
  4357.7  695.11  4473.8  689.32  4566.1  685.73  4580.4  685.62  4594.6  683.58
  4608.9  682.70  4672.6  680.65  4701.2  678.87  4707.7  679.06  4744.0  677.21
  4807.7  676.35  4822.0  675.72  4842.8  676.35  4878.0  676.41  4900.0  675.74
  4963.7  675.97  4975.9  674.90  4976.2  674.40  4979.7  674.40  4979.9  674.90
  4984.5  676.06  5005.6  675.21  5034.4  674.98  5041.9  676.16  5048.8  678.40
  5069.6  681.60  5156.0  682.95  5220.1  684.54  5269.7  686.83  5389.6  690.33
#Mann=3,-1,0
  4357.7    0.05       0  4975.9   0.033       0  4979.9    0.05       0
Bank Sta=4975.9,4979.9
Exp/Cntr=0.3,0.1

Type RM Length L Ch R = 1,5870,204,204,204
BEGIN DESCRIPTION:
Graham Branch Tr 10 17.0
END DESCRIPTION:
XS GIS Cut Line= 3
      2357354.16      7082473.99      2357158.73      7081959.77
      2356927.06      7081571.19
#Sta/Elev= 30
  4449.9  694.71  4644.4  685.67  4668.1  685.35  4710.9  681.84  4807.2  678.02
  4844.5  674.32  4850.0  673.15  4860.7  672.58  4892.8  672.84  4935.6  671.89
  4959.7  673.03  4978.4  671.95  4984.4  669.87  4987.8  669.78  4988.0  669.28
  4991.5  669.28  4991.8  669.78  4997.2  671.03  5007.4  671.47  5023.0  671.65
  5034.7  670.38  5057.9  671.39  5102.8  676.14  5108.6  675.92  5116.2  676.78
  5225.4  681.23  5262.4  684.83  5268.2  684.64  5314.1  687.37  5452.4  693.15
#Mann=3,-1,0
  4449.9    0.05       0  4987.8   0.033       0  4991.8    0.05       0
Bank Sta=4987.8,4991.8
Exp/Cntr=0.3,0.1

Type RM Length L Ch R = 1,5666,246,246,246
BEGIN DESCRIPTION:
Graham Branch Tr 10 16.0
END DESCRIPTION:
XS GIS Cut Line= 3
      2357530.81      7082348.12      2357298.92      7081839.82
      2357045.78      7081325.99
#Sta/Elev= 30
  4441.3  693.04  4456.7  691.47  4462.2  692.58  4479.8  690.94  4485.2  691.93
  4502.8  690.40  4508.3  691.00  4531.3  689.98  4577.4  687.02  4864.8  674.16
  4955.8  671.87  4991.0  669.30  4995.2  668.13  4995.4  667.63  4999.2  668.13
  5022.1  669.52  5044.4  672.95  5075.6  675.35  5081.2  676.50  5143.0  679.20
  5148.6  680.21  5283.4  687.81  5345.2  689.80  5350.7  690.83  5418.1  691.86
  5423.7  692.76  5440.6  692.25  5446.2  693.04  5463.1  692.59  5572.8  694.16
#Mann=3,-1,0
  4441.3    0.05       0  4995.2   0.033       0  4999.2    0.05       0
Bank Sta=4995.2,4999.2
Exp/Cntr=0.3,0.1

Type RM Length L Ch R = 1,5420,273,273,273
BEGIN DESCRIPTION:
Graham Branch Tr 10 15.0
END DESCRIPTION:
XS GIS Cut Line= 3
      2357742.42      7082281.99      2357510.21      7081737.25
      2357304.08      7081234.97
#Sta/Elev= 30
  4431.1  685.96  4451.1  687.04  4456.5  685.63  4474.7  686.48  4480.1  685.24
  4498.3  685.88  4503.7  684.30  4527.4  685.26  4577.3  683.89  4799.7  675.16
  4842.7  674.14  4856.2  673.57  4861.6  674.14  4885.2  672.40  4890.7  673.02
  4932.5  671.48  4985.2  670.74  4998.5  669.53  5017.1  663.51  5017.3  663.01
  5021.1  663.51  5038.1  663.76  5043.5  664.95  5052.7  668.46  5062.0  669.62
  5115.2  672.17  5144.8  674.50  5177.5  675.95  5304.9  679.87  5566.2  684.17
#Mann=8,-1,0
  4431.1   0.075       0  4577.3    0.05       0  4799.7   0.075       0
  4842.7    0.05       0  5017.1   0.033       0  5021.1    0.05       0
  5115.2   0.075       0  5177.5    0.05       0
Bank Sta=5017.1,5021.1
Exp/Cntr=0.3,0.1

Type RM Length L Ch R = 1,5147,326,326,326
BEGIN DESCRIPTION:
Graham Branch Tr 10 14.0
END DESCRIPTION:
XS GIS Cut Line= 3
      2357729.00      7082159.99      2357739.70      7081610.80
      2357629.00      7081409.99
#Sta/Elev= 30
  4450.7  684.31  4590.7  677.30  4740.7  671.31  4780.8  670.14  4800.8  668.78
  4840.8  664.79  4860.8  663.96  4880.8  663.62  4890.8  662.78  4930.8  664.34
  4950.8  663.76  4960.8  664.22  4970.8  661.68  4978.8  661.02  4979.0  660.52
  4982.5  660.52  4982.8  661.02  4997.9  663.05  5009.2  663.72  5014.9  665.10
  5023.7  664.97  5036.7  666.94  5058.5  666.91  5068.8  665.79  5080.8  665.90
  5096.3  667.62  5112.4  670.29  5134.2  671.69  5215.5  674.65  5229.3  674.75
#Mann=3,-1,0
  4450.7    0.05       0  4978.8   0.033       0  4982.8    0.05       0
Bank Sta=4978.8,4982.8
Exp/Cntr=0.3,0.1

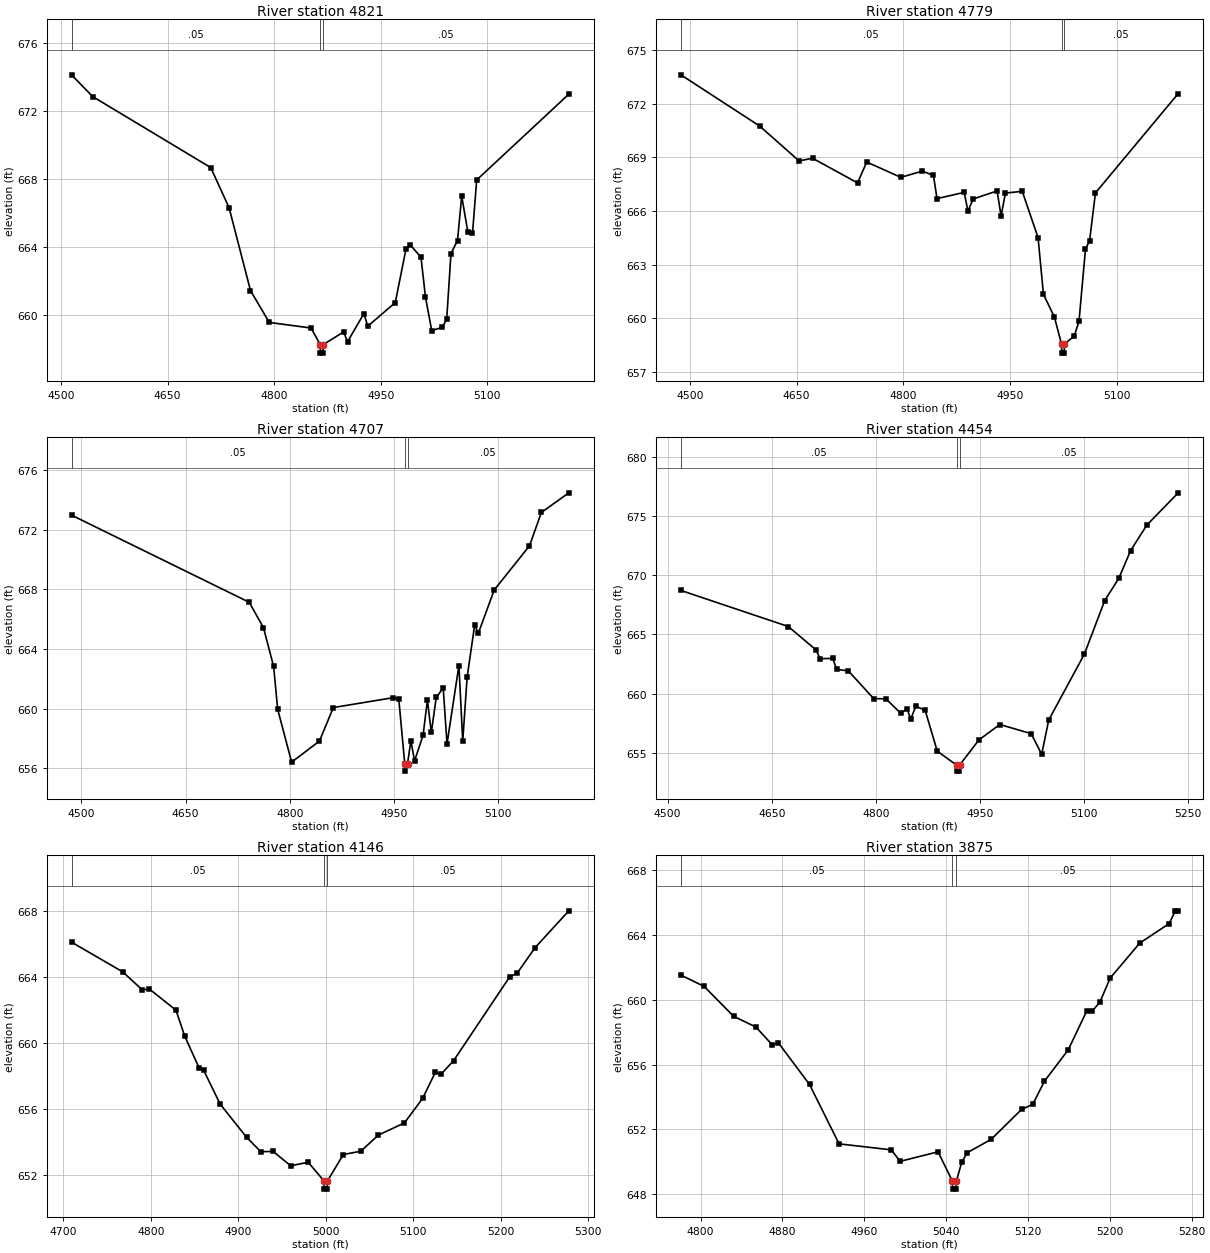
Type RM Length L Ch R = 1,4821,42,42,42
BEGIN DESCRIPTION:
Mapping XS b6e8cc8b
END DESCRIPTION:
XS GIS Cut Line= 6
      2357984.08      7081986.21      2358060.45      7081805.70
      2358067.39      7081722.36      2358062.18      7081633.82
      2358032.67      7081569.59      2357890.31      7081350.84
#Sta/Elev= 30
  4514.9  674.15  4544.6  672.87  4710.9  668.68  4736.7  666.31  4766.8  661.43
  4793.2  659.55  4852.1  659.22  4865.0  658.24  4865.3  657.74  4868.8  657.74
  4869.0  658.24  4897.9  658.99  4903.4  658.41  4926.4  660.07  4931.9  659.33
  4970.6  660.72  4985.7  663.88  4991.7  664.13  5006.8  663.39  5013.1  661.05
  5021.9  659.07  5036.9  659.26  5043.0  659.75  5049.0  663.61  5058.2  664.38
  5064.1  667.00  5072.7  664.90  5079.3  664.80  5085.2  667.95  5214.9  673.01
#Mann=3,-1,0
  4514.9    0.05       0  4865.0   0.033       0  4869.0    0.05       0
Bank Sta=4865,4869
Exp/Cntr=0.3,0.1

Type RM Length L Ch R = 1,4779,72,72,72
BEGIN DESCRIPTION:
Mapping XS 4e3570ad
END DESCRIPTION:
XS GIS Cut Line= 6
      2358017.03      7081993.24      2358093.43      7081788.34
      2358107.32      7081737.99      2358109.06      7081694.59
      2358089.96      7081595.63      2357951.07      7081349.09
#Sta/Elev= 30
  4487.5  673.62  4598.2  670.75  4653.5  668.80  4672.4  668.95  4735.6  667.57
  4748.5  668.74  4796.4  667.88  4826.6  668.23  4842.2  667.99  4847.2  666.69
  4885.4  667.04  4890.6  665.99  4898.0  666.67  4931.6  667.12  4937.2  665.72
  4943.3  667.00  4966.9  667.10  4989.1  664.51  4996.7  661.33  5012.1  660.06
  5022.1  658.54  5022.3  658.04  5025.8  658.04  5026.1  658.54  5039.9  659.00
  5046.6  659.82  5055.7  663.86  5061.5  664.34  5069.7  667.01  5185.9  672.57
#Mann=3,-1,0
  4487.5    0.05       0  5022.1   0.033       0  5026.1    0.05       0
Bank Sta=5022.1,5026.1
Exp/Cntr=0.3,0.1

Type RM Length L Ch R = 1,4707,253,253,253
BEGIN DESCRIPTION:
Mapping XS 37b2535d
END DESCRIPTION:
XS GIS Cut Line= 6
      2358056.98      7082000.13      2358122.95      7081840.42
      2358150.73      7081725.84      2358154.20      7081618.20
      2358119.48      7081519.24      2358027.44      7081328.23
#Sta/Elev= 30
  4486.0  672.99  4741.6  667.14  4762.1  665.43  4776.7  662.83  4782.5  659.96
  4802.6  656.40  4842.6  657.82  4862.6  660.07  4948.4  660.73  4956.7  660.64
  4965.3  656.30  4965.5  655.80  4969.3  656.30  4974.1  657.85  4979.4  656.49
  4991.6  658.20  4997.9  660.56  5003.5  658.40  5010.6  660.75  5020.6  661.39
  5026.1  657.63  5043.2  662.89  5048.7  657.81  5055.0  662.10  5065.8  665.59
  5071.3  665.08  5094.0  667.97  5144.7  670.93  5161.8  673.17  5201.3  674.49
#Mann=3,-1,0
  4486.0    0.05       0  4965.3   0.033       0  4969.3    0.05       0
Bank Sta=4965.3,4969.3
Exp/Cntr=0.3,0.1

Type RM Length L Ch R = 1,4454,308,308,308
BEGIN DESCRIPTION:
Mapping XS ae073879
END DESCRIPTION:
XS GIS Cut Line= 4
      2358209.30      7081973.27      2358341.70      7081649.88
      2358337.36      7081519.40      2358304.80      7081285.25
#Sta/Elev= 30
  4519.1  668.72  4673.9  665.67  4714.0  663.68  4719.4  662.95  4738.0  662.98
  4743.4  662.05  4760.4  661.92  4796.8  659.58  4814.4  659.56  4836.0  658.33
  4844.8  658.74  4850.2  657.84  4857.6  658.94  4871.0  658.59  4888.4  655.14
  4916.5  653.95  4916.7  653.45  4920.2  653.45  4920.5  653.95  4948.5  656.09
  4978.5  657.39  5023.6  656.62  5038.9  654.88  5049.0  657.77  5100.3  663.33
  5129.7  667.87  5149.9  669.74  5166.9  672.08  5190.3  674.24  5235.5  676.97
#Mann=3,-1,0
  4519.1    0.05       0  4916.5   0.033       0  4920.5    0.05       0
Bank Sta=4916.5,4920.5
Exp/Cntr=0.3,0.1

Type RM Length L Ch R = 1,4146,271,271,271
BEGIN DESCRIPTION:
Mapping XS 1c15135b
END DESCRIPTION:
XS GIS Cut Line= 4
      2358665.04      7081848.14      2358633.58      7081630.08
      2358621.65      7081479.25      2358501.29      7081323.44
#Sta/Elev= 30
  4709.5  666.14  4768.2  664.33  4790.2  663.25  4798.6  663.29  4828.9  662.01
  4839.0  660.42  4855.5  658.49  4860.5  658.37  4879.4  656.31  4909.7  654.29
  4925.9  653.42  4939.9  653.44  4960.0  652.57  4980.1  652.78  4998.1  651.65
  4998.4  651.15  5001.9  651.15  5002.1  651.65  5020.2  653.25  5040.2  653.45
  5060.3  654.43  5090.1  655.17  5110.9  656.66  5125.4  658.24  5131.7  658.11
  5146.2  658.94  5210.5  664.04  5218.7  664.24  5239.5  665.81  5278.0  668.04
#Mann=3,-1,0
  4709.5    0.05       0  4998.1   0.033       0  5002.1    0.05       0
Bank Sta=4998.1,5002.1
Exp/Cntr=0.3,0.1

Type RM Length L Ch R = 1,3875,366,366,366
BEGIN DESCRIPTION:
Graham Branch Tr 10 10.0
END DESCRIPTION:
XS GIS Cut Line= 3
      2358928.99      7081609.99      2358822.94      7081418.15
      2358579.03      7081310.02
#Sta/Elev= 30
  4780.8  661.51  4803.6  660.81  4832.3  658.97  4854.1  658.31  4870.1  657.21
  4875.9  657.35  4906.5  654.77  4935.4  651.11  4986.5  650.74  4995.0  650.03
  5032.1  650.62  5046.1  648.82  5046.3  648.32  5049.8  648.32  5050.1  648.82
  5055.3  649.99  5060.8  650.57  5084.1  651.39  5113.7  653.23  5124.6  653.54
  5136.1  654.97  5159.4  656.91  5177.2  659.27  5182.6  659.27  5190.3  659.85
  5200.4  661.33  5229.2  663.48  5257.9  664.68  5264.1  665.47  5266.8  665.47
#Mann=3,-1,0
  4780.8    0.05       0  5046.1   0.033       0  5050.1    0.05       0
Bank Sta=5046.1,5050.1
Exp/Cntr=0.3,0.1

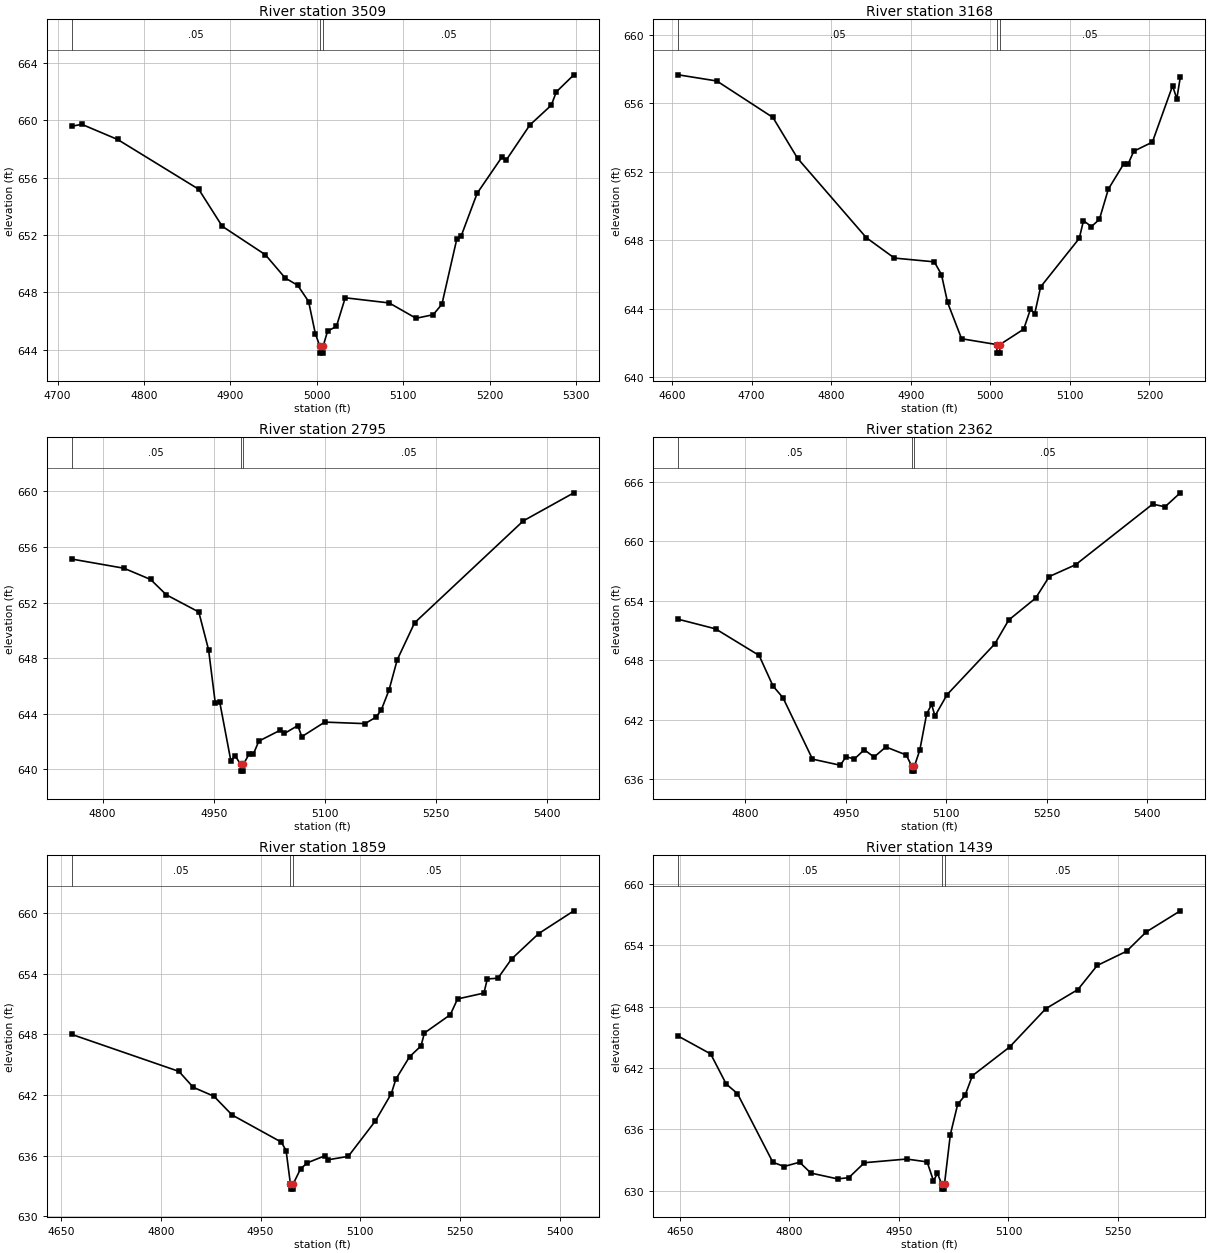
Type RM Length L Ch R = 1,3509,341,341,341
BEGIN DESCRIPTION:
Graham Branch Tr 10 9.0
END DESCRIPTION:
XS GIS Cut Line= 3
      2359198.48      7081335.38      2358971.28      7081165.63
      2358679.03      7081110.01
#Sta/Elev= 30
  4716.4  659.59  4727.9  659.73  4769.5  658.67  4863.3  655.20  4890.5  652.62
  4940.5  650.63  4963.4  649.01  4977.9  648.50  4990.5  647.37  4998.3  645.13
  5003.4  644.27  5003.7  643.77  5007.2  643.77  5007.4  644.27  5012.5  645.31
  5022.7  645.63  5032.9  647.63  5083.8  647.27  5114.9  646.20  5134.7  646.45
  5144.8  647.18  5162.0  651.72  5167.1  651.94  5185.6  654.92  5214.2  657.44
  5219.2  657.23  5246.6  659.68  5271.4  661.06  5277.2  661.99  5297.5  663.18
#Mann=3,-1,0
  4716.4    0.05       0  5003.4   0.033       0  5007.4    0.05       0
Bank Sta=5003.4,5007.4
Exp/Cntr=0.3,0.1

Type RM Length L Ch R = 1,3168,373,373,373
BEGIN DESCRIPTION:
Graham Branch Tr 10 8.0
END DESCRIPTION:
XS GIS Cut Line= 3
      2359260.33      7081194.32      2358986.23      7081025.69
      2358881.00      7080734.97
#Sta/Elev= 30
  4607.8  657.65  4656.3  657.29  4726.8  655.16  4757.7  652.78  4844.2  648.14
  4879.5  646.95  4929.6  646.73  4938.6  645.99  4946.3  644.36  4963.9  642.24
  5008.1  641.90  5008.4  641.40  5011.9  641.40  5012.1  641.90  5042.0  642.80
  5050.5  643.97  5055.8  643.70  5063.3  645.27  5111.8  648.10  5117.1  649.13
  5127.1  648.79  5137.1  649.21  5148.4  650.98  5167.8  652.46  5173.1  652.43
  5180.3  653.19  5203.7  653.72  5229.1  657.01  5234.4  656.25  5238.8  657.52
#Mann=3,-1,0
  4607.8    0.05       0  5008.1   0.033       0  5012.1    0.05       0
Bank Sta=5008.1,5012.1
Exp/Cntr=0.3,0.1

Type RM Length L Ch R = 1,2795,433,433,433
BEGIN DESCRIPTION:
Graham Branch Tr 10 7.0
END DESCRIPTION:
XS GIS Cut Line= 3
      2359431.75      7080954.51      2359230.56      7080820.74
      2358830.11      7080648.56
#Sta/Elev= 30
  4758.4  655.13  4828.8  654.47  4864.8  653.66  4885.9  652.56  4929.8  651.32
  4943.0  648.60  4952.0  644.78  4958.0  644.85  4973.0  640.62  4979.1  640.95
  4986.1  640.36  4986.3  639.86  4989.8  639.86  4990.1  640.36  4997.9  641.11
  5003.6  641.11  5010.8  642.02  5039.8  642.81  5045.3  642.57  5063.4  643.14
  5068.8  642.34  5099.7  643.39  5154.1  643.28  5168.4  643.73  5175.9  644.24
  5186.5  645.70  5197.6  647.88  5221.0  650.54  5367.7  657.88  5435.9  659.90
#Mann=3,-1,0
  4758.4    0.05       0  4986.1   0.033       0  4990.1    0.05       0
Bank Sta=4986.1,4990.1
Exp/Cntr=0.3,0.1

Type RM Length L Ch R = 1,2362,503,503,503
BEGIN DESCRIPTION:
Graham Branch Tr 10 6.0
END DESCRIPTION:
XS GIS Cut Line= 3
      2359552.30      7080655.48      2359308.70      7080479.86
      2358866.53      7080396.81
#Sta/Elev= 30
  4699.7  652.13  4755.5  651.16  4820.5  648.48  4841.4  645.38  4856.1  644.22
  4900.3  638.01  4942.0  637.39  4950.3  638.26  4962.9  638.02  4977.6  638.96
  4992.3  638.22  5009.9  639.24  5040.4  638.43  5048.6  637.30  5048.8  636.80
  5052.3  636.80  5052.6  637.30  5060.7  638.94  5070.9  642.58  5078.3  643.53
  5083.3  642.36  5101.4  644.52  5172.7  649.64  5193.5  652.05  5233.7  654.26
  5254.1  656.44  5293.4  657.63  5408.6  663.75  5427.0  663.48  5449.9  664.89
#Mann=3,-1,0
  4699.7    0.05       0  5048.6   0.033       0  5052.6    0.05       0
Bank Sta=5048.6,5052.6
Exp/Cntr=0.3,0.1

Type RM Length L Ch R = 1,1859,420,420,420
BEGIN DESCRIPTION:
Graham Branch Tr 10 5.0
END DESCRIPTION:
XS GIS Cut Line= 3
      2359765.83      7080315.20      2359479.04      7080144.78
      2359067.37      7080058.09
#Sta/Elev= 30
  4666.4  647.99  4827.4  644.33  4848.8  642.76  4880.0  641.87  4907.2  640.02
  4981.3  637.33  4988.4  636.49  4994.9  633.18  4995.1  632.68  4998.6  632.68
  4998.9  633.18  5010.3  634.70  5020.5  635.29  5046.7  635.98  5051.9  635.59
  5081.8  635.92  5122.7  639.44  5146.4  642.12  5153.3  643.56  5173.8  645.77
  5191.1  646.85  5196.2  648.13  5235.1  649.94  5246.0  651.50  5285.6  652.08
  5290.7  653.48  5306.6  653.55  5327.1  655.45  5367.9  657.97  5420.7  660.22
#Mann=3,-1,0
  4666.4    0.05       0  4994.9   0.033       0  4998.9    0.05       0
Bank Sta=4994.9,4998.9
Exp/Cntr=0.3,0.1

Type RM Length L Ch R = 1,1439,331,331,331
BEGIN DESCRIPTION:
Graham Branch Tr 10 4.0
END DESCRIPTION:
XS GIS Cut Line= 3
      2359829.04      7079960.02      2359529.33      7079775.03
      2359195.83      7079740.38
#Sta/Elev= 30
  4647.8  645.11  4692.2  643.37  4713.5  640.43  4728.9  639.49  4777.3  632.79
  4792.7  632.37  4814.0  632.79  4829.4  631.73  4866.0  631.16  4881.4  631.28
  4902.7  632.74  4960.6  633.10  4988.6  632.82  4997.3  630.98  5002.8  631.70
  5008.4  630.66  5008.6  630.16  5012.1  630.16  5012.4  630.66  5020.4  635.49
  5030.5  638.46  5040.5  639.31  5050.6  641.24  5101.5  644.04  5151.1  647.79
  5195.1  649.66  5221.5  652.01  5261.7  653.40  5288.7  655.29  5335.3  657.35
#Mann=3,-1,0
  4647.8    0.05       0  5008.4   0.033       0  5012.4    0.05       0
Bank Sta=5008.4,5012.4
Exp/Cntr=0.3,0.1

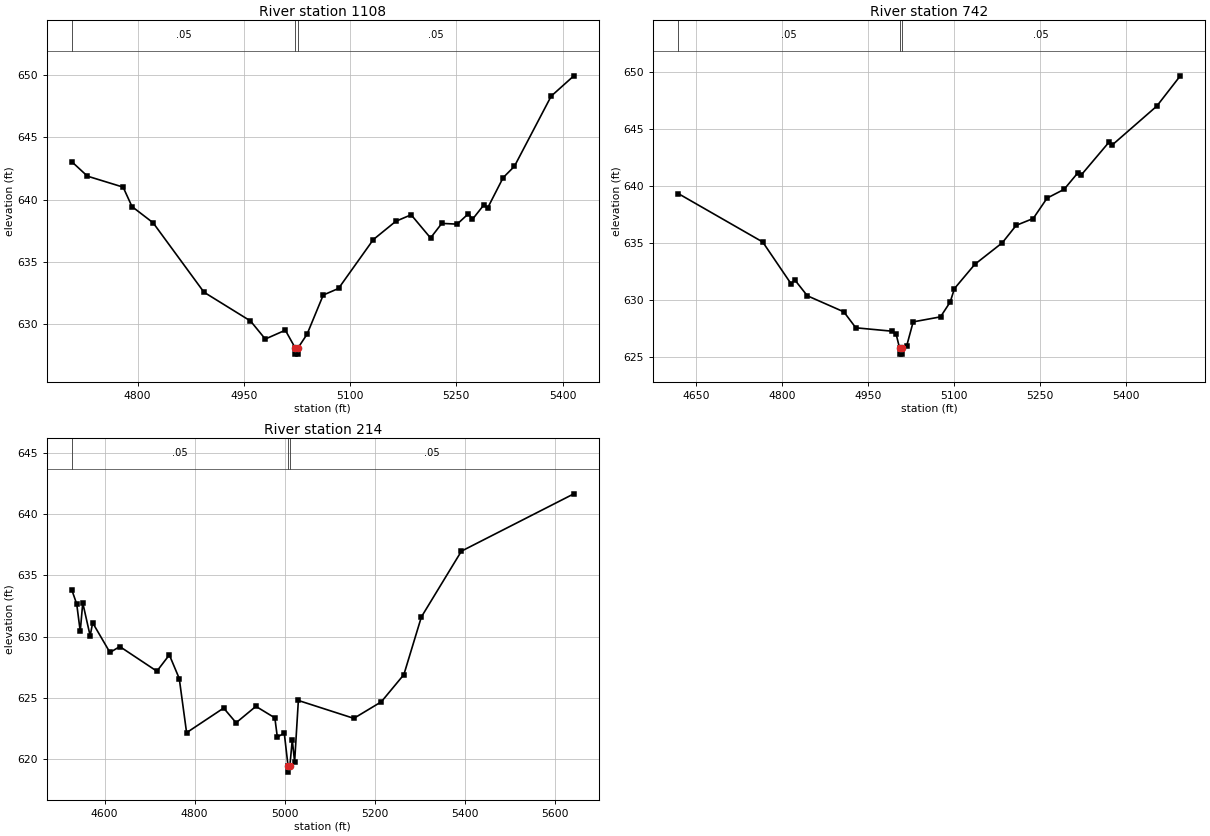
Type RM Length L Ch R = 1,1108,366,366,366
BEGIN DESCRIPTION:
Graham Branch Tr 10 3.0
END DESCRIPTION:
XS GIS Cut Line= 3
      2359938.88      7079809.79      2359773.30      7079568.31
      2359411.13      7079363.65
#Sta/Elev= 30
  4707.2  643.04  4729.3  641.88  4779.7  641.00  4792.2  639.44  4822.0  638.14
  4893.8  632.57  4959.5  630.26  4980.4  628.81  5008.7  629.52  5022.6  628.10
  5022.9  627.60  5026.4  627.60  5026.6  628.10  5039.4  629.20  5062.2  632.34
  5083.8  632.87  5132.9  636.79  5164.7  638.26  5186.3  638.78  5213.7  636.92
  5229.6  638.09  5251.3  638.03  5267.2  638.87  5272.9  638.42  5288.8  639.56
  5294.6  639.36  5316.2  641.76  5332.1  642.67  5384.0  648.30  5416.0  649.93
#Mann=3,-1,0
  4707.2    0.05       0  5022.6   0.033       0  5026.6    0.05       0
Bank Sta=5022.6,5026.6
Exp/Cntr=0.3,0.1

Type RM Length L Ch R = 1,742,528,528,528
BEGIN DESCRIPTION:
Graham Branch Tr 10 2.0
END DESCRIPTION:
XS GIS Cut Line= 3
      2360152.46      7079573.73      2359905.16      7079282.84
      2359445.90      7079099.78
#Sta/Elev= 30
  4618.2  639.37  4765.6  635.12  4815.0  631.46  4821.5  631.80  4843.5  630.40
  4907.2  628.99  4928.1  627.59  4991.8  627.29  4998.6  627.01  5004.6  625.78
  5004.9  625.28  5008.4  625.28  5008.6  625.78  5016.6  625.95  5028.2  628.11
  5075.9  628.55  5092.8  629.85  5100.2  631.03  5135.8  633.16  5183.7  635.05
  5208.0  636.58  5237.7  637.18  5261.9  638.97  5291.6  639.74  5315.8  641.20
  5321.2  640.98  5369.8  643.87  5375.1  643.61  5453.3  647.04  5494.4  649.70
#Mann=3,-1,0
  4618.2    0.05       0  5004.6   0.033       0  5008.6    0.05       0
Bank Sta=5004.6,5008.6
Exp/Cntr=0.3,0.1

Type RM Length L Ch R = 1,214,0,0,0
BEGIN DESCRIPTION:
Graham Branch Tr 10 1.0
END DESCRIPTION:
XS GIS Cut Line= 4
      2360333.79      7079339.74      2360130.65      7078956.90
      2360100.05      7078853.96      2359588.52      7078593.09
#Sta/Elev= 30
  4527.3  633.83  4538.3  632.66  4546.1  630.43  4551.7  632.76  4568.1  630.07
  4573.7  631.13  4612.1  628.71  4634.0  629.19  4716.3  627.18  4744.0  628.51
  4766.0  626.58  4782.3  622.16  4864.6  624.17  4892.2  622.97  4936.2  624.31
  4978.3  623.37  4983.8  621.80  4999.2  622.13  5007.6  619.44  5007.9  618.94
  5011.6  619.44  5017.0  621.57  5022.2  619.77  5030.5  624.79  5153.7  623.33
  5214.7  624.68  5264.8  626.90  5303.7  631.61  5392.6  636.98  5642.3  641.66
#Mann=3,-1,0
  4527.3    0.05       0  5007.6   0.033       0  5011.6    0.05       0
Bank Sta=5007.6,5011.6
Exp/Cntr=0.3,0.1

Chan Stop Cuts=-1