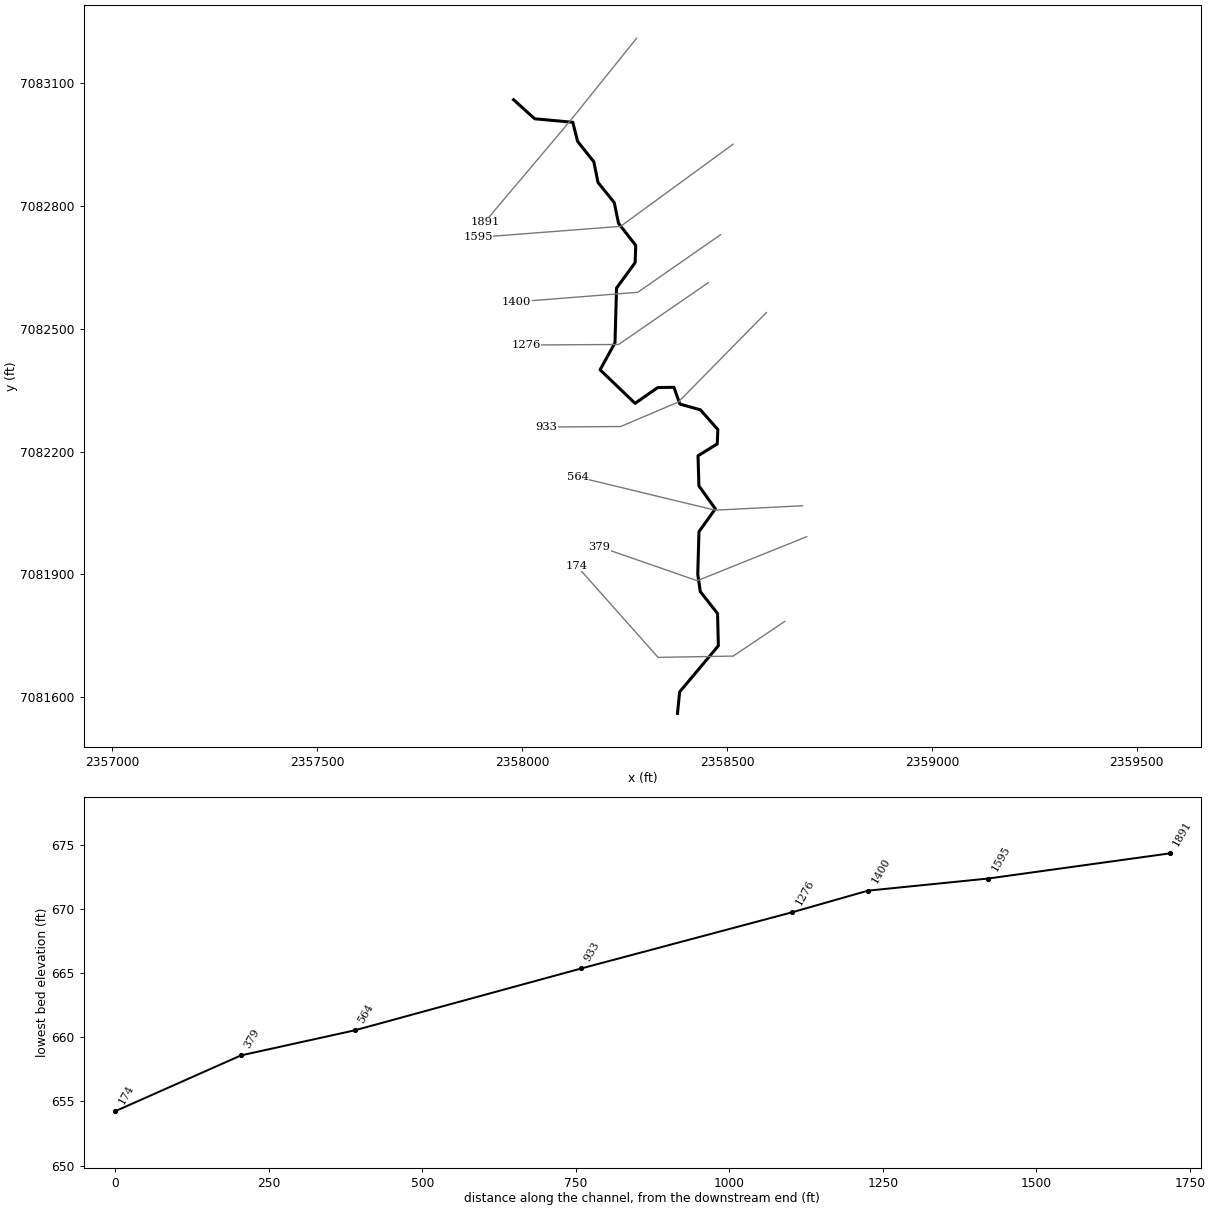
--- Graham Branch Tr 10_1.prj (project) ---

Proj Title=Graham Branch Tr 10_1 Base Level Engineering
Current Plan=p01
Default Exp/Contr=0.3,0.1
English Units
Geom File=g01
Flow File=f01
Plan File=p01
Y Axis Title=Elevation
X Axis Title(PF)=Main Channel Distance
X Axis Title(XS)=Station
BEGIN DESCRIPTION:
Graham Branch Tr 10_1
END DESCRIPTION:
DSS Export Rating Curves= 0
DSS Export Rating Curve Sorted= 0
DSS Export Volume Flow Curves= 0
DXF OffsetX= 0
DXF OffsetY= 0
DXF ScaleX= 1
DXF ScaleY= 10

--- Graham Branch Tr 10_1.p01 (plan) ---

Plan Title=Multiple Run
Short Identifier=Multiple
Geom File=g01
Flow File=f01
Subcritical Flow
K Sum by GR= 0
Std Step Tol= 0.01
Critical Tol= 0.01
Num of Std Step Trials= 20
Max Error Tol= 0.3
Flow Tol Ratio= 0.001
Split Flow NTrial= 30
Split Flow Tol= 0.02
Split Flow Ratio= 0.02
Log Output Level= 0
Friction Slope Method= 1
Unsteady Friction Slope Method= 2
Unsteady Bridges Friction Slope Method= 1
Parabolic Critical Depth
Global Vel Dist=  1 , 1 , 1
Global Log Level= 0
CheckData=True
Encroach Param= -1, 0, 0, 0
BEGIN DESCRIPTION:
Multiple Run
END DESCRIPTION:

--- Graham Branch Tr 10_1.f01 (steady flow) ---

Flow Title=Multiple
Program Version=4.10
Number of Profiles= 7
Profile Names=10-year,25-year,50-year,1pct_min,100-year,1pct_plu,500-year
River Rch & RM=Graham Branch Tr,Reach-1         ,1891
     200     254     296     172     344     685     462
Boundary for River Rch & Prof#=Graham Branch Tr,Reach-1         , 1
Up Type= 0
Dn Type= 3
Dn Slope=0.014
Boundary for River Rch & Prof#=Graham Branch Tr,Reach-1         , 2
Up Type= 0
Dn Type= 3
Dn Slope=0.014
Boundary for River Rch & Prof#=Graham Branch Tr,Reach-1         , 3
Up Type= 0
Dn Type= 3
Dn Slope=0.014
Boundary for River Rch & Prof#=Graham Branch Tr,Reach-1         , 4
Up Type= 0
Dn Type= 3
Dn Slope=0.014
Boundary for River Rch & Prof#=Graham Branch Tr,Reach-1         , 5
Up Type= 0
Dn Type= 3
Dn Slope=0.014
Boundary for River Rch & Prof#=Graham Branch Tr,Reach-1         , 6
Up Type= 0
Dn Type= 3
Dn Slope=0.014
Boundary for River Rch & Prof#=Graham Branch Tr,Reach-1         , 7
Up Type= 0
Dn Type= 3
Dn Slope=0.014
DSS Import GetInterval= 0
DSS Import GetPeak= 0
DSS Import FillOption= 0

--- Graham Branch Tr 10_1.g01 (geometry) ---

Geom Title=Existing Conditions
Program Version=4.10

River Reach=Graham Branch Tr,Reach-1
Reach XY= 30
        2357979.        7083060.       2358030.5      7083013.43
      2358123.58      7083004.79      2358135.26       7082958.2
      2358174.85      7082908.31      2358185.08      7082857.81
      2358224.84      7082808.28      2358235.16       7082757.8
       2358277.2      7082703.89      2358275.63      7082661.74
      2358230.25       7082599.5      2358226.52      7082465.86
       2358190.1      7082399.89      2358275.58      7082317.83
      2358330.98      7082356.49      2358370.37        7082357.
      2358384.81      7082316.14      2358435.16      7082301.85
      2358477.54      7082253.78      2358476.02      7082218.69
      2358429.17      7082189.65      2358431.34      7082115.98
      2358471.43        7082060.      2358431.45      7082004.14
       2358428.5      7081899.83      2358434.74      7081857.67
      2358476.84      7081804.02      2358478.76      7081725.22
      2358384.33      7081612.51        2358379.        7081560.

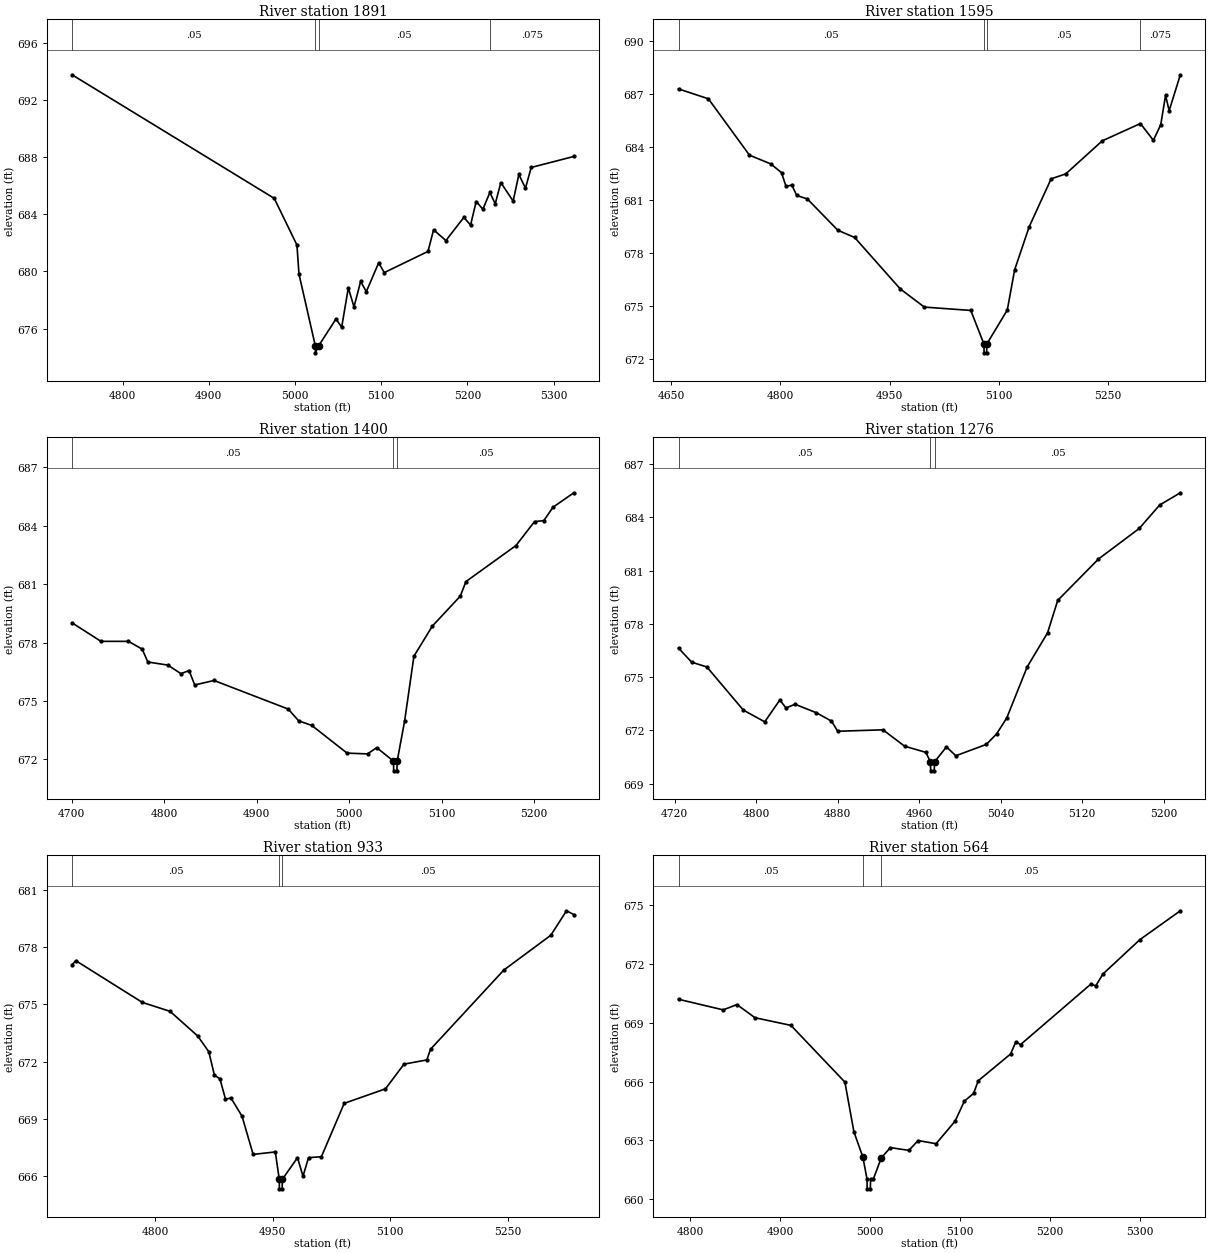
Type RM Length L Ch R = 1 ,1891    ,296,296,296
BEGIN DESCRIPTION:
Graham Branch Tr 10_1 5.0
END DESCRIPTION:
XS GIS Cut Line= 3
      2358279.02      7083210.02      2358117.18      7083008.32
      2357908.93       7082760.9
#Sta/Elev= 30
  4741.4  693.75  4975.9  685.11  5002.2  681.85  5004.6  679.81  5023.5  674.81
  5023.7  674.31  5027.5  674.81  5047.5  676.68  5054.1   676.1  5061.8  678.85
  5068.4  677.52  5076.1   679.3  5082.7  678.59    5097   680.6  5103.5  679.92
  5154.2   681.4  5160.7  682.91    5175  682.16  5195.8  683.78  5203.6  683.24
  5210.1  684.89  5217.9  684.35    5226  685.52  5232.2  684.73  5238.7  686.21
    5253  684.92  5259.6  686.78  5267.3  685.82  5273.9  687.27  5323.4  688.04
#Mann= 4 ,-1 , 0
  4741.4     .05       0  5023.5     .04       0  5027.5     .05       0
    5226    .075       0
Bank Sta=5023.5,5027.5
XS Rating Curve= 0 ,0
Exp/Cntr=0.3,0.1

Type RM Length L Ch R = 1 ,1595    ,195,195,195
BEGIN DESCRIPTION:
Graham Branch Tr 10_1 4.0
END DESCRIPTION:
XS GIS Cut Line= 3
      2358514.54      7082951.12       2358240.2      7082750.45
      2357892.14      7082723.56
#Sta/Elev= 30
  4660.1  687.29  4701.1  686.73  4757.5  683.54  4786.9  683.04  4801.5  682.55
  4807.7  681.77  4815.6  681.85  4822.4  681.26    4837  681.06  4878.8  679.29
  4901.9  678.88  4964.5  675.97  4997.6  674.94  5061.4  674.75  5079.4  672.85
  5079.7  672.35  5083.2  672.35  5083.4  672.85  5111.5  674.77  5121.6  677.05
  5141.6  679.49  5171.7   682.2  5191.8  682.48  5241.9  684.35  5294.3  685.33
  5312.1  684.38  5322.2  685.26  5328.8  686.92  5333.8  686.06  5349.1  688.09
#Mann= 4 ,-1 , 0
  4660.1     .05       0  5079.4    .033       0  5083.4     .05       0
  5294.3    .075       0
Bank Sta=5079.4,5083.4
XS Rating Curve= 0 ,0
Exp/Cntr=0.3,0.1

Type RM Length L Ch R = 1 ,1400    ,124,124,124
BEGIN DESCRIPTION:
Mapping XS b978cf1f
END DESCRIPTION:
XS GIS Cut Line= 3
      2358484.01      7082729.91      2358282.21       7082589.3
      2357986.59      7082565.86
#Sta/Elev= 30
  4700.5  679.01  4731.8  678.06  4761.5  678.06  4776.3  677.66  4782.4     677
  4804.1  676.84  4818.2   676.4    4827  676.56  4833.1  675.82    4854  676.05
  4934.3  674.58  4945.4  673.98  4959.7  673.74  4997.8  672.32  5019.9  672.28
  5029.9   672.6    5048  671.91  5048.2  671.41  5051.7  671.41    5052  671.91
    5060  673.96  5070.1   677.3  5090.1  678.85  5120.2  680.38  5126.3  681.13
  5180.4  682.98  5200.5  684.21  5210.5  684.26  5220.5  684.95    5243  685.69
#Mann= 3 ,-1 , 0
  4700.5     .05       0    5048    .033       0    5052     .05       0
Bank Sta=5048,5052
XS Rating Curve= 0 ,0
Exp/Cntr=0.3,0.1

Type RM Length L Ch R = 1 ,1276    ,343,343,343
BEGIN DESCRIPTION:
Mapping XS 52aa110c
END DESCRIPTION:
XS GIS Cut Line= 3
      2358454.05      7082612.71      2358235.34      7082461.69
      2358008.73      7082460.39
#Sta/Elev= 30
  4723.9  676.63  4736.8  675.84  4751.7  675.57  4787.5  673.14  4808.5  672.48
  4823.3  673.71  4829.4  673.26  4838.2  673.47  4859.2  672.99    4874  672.52
  4880.1  671.95  4924.5  672.03  4945.7  671.11  4966.6  670.76  4971.1  670.22
  4971.3  669.72  4974.8  669.72  4975.1  670.22  4986.8  671.07    4996  670.57
    5026  671.21    5036   671.8    5046   672.7    5066  675.57    5086  677.49
    5096  679.32    5136  681.65    5176  683.37    5196  684.69  5216.3  685.38
#Mann= 3 ,-1 , 0
  4723.9     .05       0  4971.1    .033       0  4975.1     .05       0
Bank Sta=4971.1,4975.1
XS Rating Curve= 0 ,0
Exp/Cntr=0.3,0.1

Type RM Length L Ch R = 1 ,933     ,369,369,369
BEGIN DESCRIPTION:
Mapping XS e147c1d4
END DESCRIPTION:
XS GIS Cut Line= 4
      2358595.99       7082539.8      2358381.17      7082321.07
      2358240.54      7082261.17      2358059.58      7082259.87
#Sta/Elev= 30
  4694.2  677.07    4699  677.28  4783.8   675.1  4819.3  674.63  4854.6  673.34
  4868.7  672.52  4875.8   671.3  4882.9   671.1    4890  670.04    4897   670.1
  4911.1  669.15  4925.3  667.15  4953.6  667.28  4958.6  665.85  4958.8  665.35
  4962.3  665.35  4962.6  665.85  4981.9  666.98  4988.9  666.01    4996  666.98
  5012.4  667.03  5041.5  669.82  5094.2  670.58  5117.8  671.87  5146.9  672.09
  5151.7  672.65  5245.2  676.79  5305.2  678.61  5325.2  679.89  5334.6  679.69
#Mann= 3 ,-1 , 0
  4694.2     .05       0  4958.6    .033       0  4962.6     .05       0
Bank Sta=4958.6,4962.6
XS Rating Curve= 0 ,0
Exp/Cntr=0.3,0.1

Type RM Length L Ch R = 1 ,564     ,185,185,185
BEGIN DESCRIPTION:
Graham Branch Tr 10_1 2.0
END DESCRIPTION:
XS GIS Cut Line= 3
      2358683.94       7082067.5      2358470.92       7082056.7
      2358135.28      7082137.83
#Sta/Elev= 30
  4786.7  670.19  4836.4  669.65  4851.7  669.92  4871.8  669.25  4911.8  668.86
  4971.9  665.97  4981.9  663.44  4991.9  662.15  4996.5  661.03  4996.7  660.53
  5000.2  660.53  5000.5  661.03  5003.6  661.03  5012.3   662.1  5022.5  662.63
  5043.1  662.49  5053.4  662.99  5073.4  662.83  5094.6  663.98  5104.9     665
  5115.1  665.39  5120.4  666.04  5156.3   667.4  5162.2  668.02  5167.4  667.88
  5245.9  670.97  5251.1  670.87  5259.2  671.48  5300.3  673.23  5345.3   674.7
#Mann= 3 ,-1 , 0
  4786.7     .05       0  4991.9    .033       0  5012.3     .05       0
Bank Sta=4991.9,5012.3
XS Rating Curve= 0 ,0
Exp/Cntr=0.3,0.1

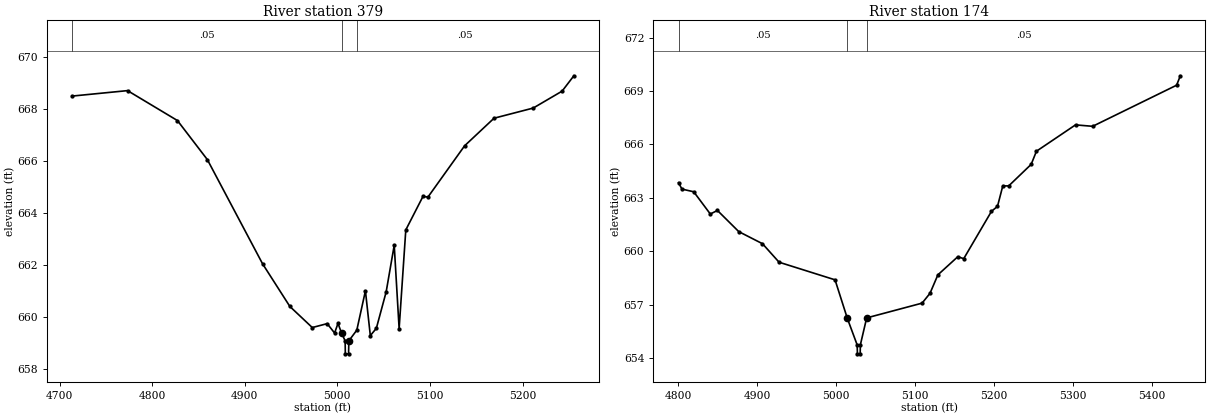
Type RM Length L Ch R = 1 ,379     ,205,205,205
BEGIN DESCRIPTION:
Mapping XS a994126c
END DESCRIPTION:
XS GIS Cut Line= 3
      2358694.55       7081991.9       2358427.2      7081884.26
      2358187.58      7081967.61
#Sta/Elev= 30
  4713.5  668.48  4773.4  668.69  4827.3  667.54  4859.6  666.04  4919.2  662.04
  4948.7   660.4  4972.9  659.59    4989  659.74    4997  659.38  5000.7  659.75
  5004.5  659.38  5008.4  659.08  5008.6  658.58  5012.1  658.58  5012.4  659.08
    5021  659.49  5030.3     661  5035.6  659.28  5042.1  659.56  5052.7  660.96
  5061.4  662.75  5066.7  659.55  5073.9  663.34  5092.5  664.63  5097.8   664.6
  5137.4  666.57  5169.2  667.63  5211.5  668.02  5242.7  668.67  5255.4  669.26
#Mann= 3 ,-1 , 0
  4713.5     .05       0  5004.5    .033       0    5021     .05       0
Bank Sta=5004.5,5012.4
XS Rating Curve= 0 ,0
Exp/Cntr=0.3,0.1

Type RM Length L Ch R = 1 ,174     ,0,0,0
BEGIN DESCRIPTION:
Graham Branch Tr 10_1 1.0
END DESCRIPTION:
XS GIS Cut Line= 4
      2358641.09      7081784.98      2358514.96      7081700.02
      2358331.62       7081696.9        2358133.      7081920.88
#Sta/Elev= 30
  4800.7  663.85    4805  663.49  4819.9  663.34  4840.9  662.09  4849.9  662.29
  4876.9   661.1  4906.9  660.42  4927.9  659.38  4998.7  658.39 5014.28 656.219
  5026.7  654.73    5027  654.23  5030.5  654.23  5030.7  654.73  5038.7  656.25
  5108.8  657.08  5118.8  657.63  5128.8  658.67    5154  659.69  5161.5  659.58
  5196.6  662.24  5204.2  662.52  5210.9  663.67  5218.4  663.67  5246.8  664.88
  5253.5  665.62  5302.9   667.1  5324.6  667.02  5430.8  669.33  5435.5  669.86
#Mann= 3 ,-1 , 0
  4800.7     .05       0 5014.28    .033       0  5038.7     .05       0
Bank Sta=5014.28,5038.7
XS Rating Curve= 0 ,0
Exp/Cntr=0.3,0.1

Chan Stop Cuts=-1
Use User Specified Reach Order=0
Composite Channel Slope=5