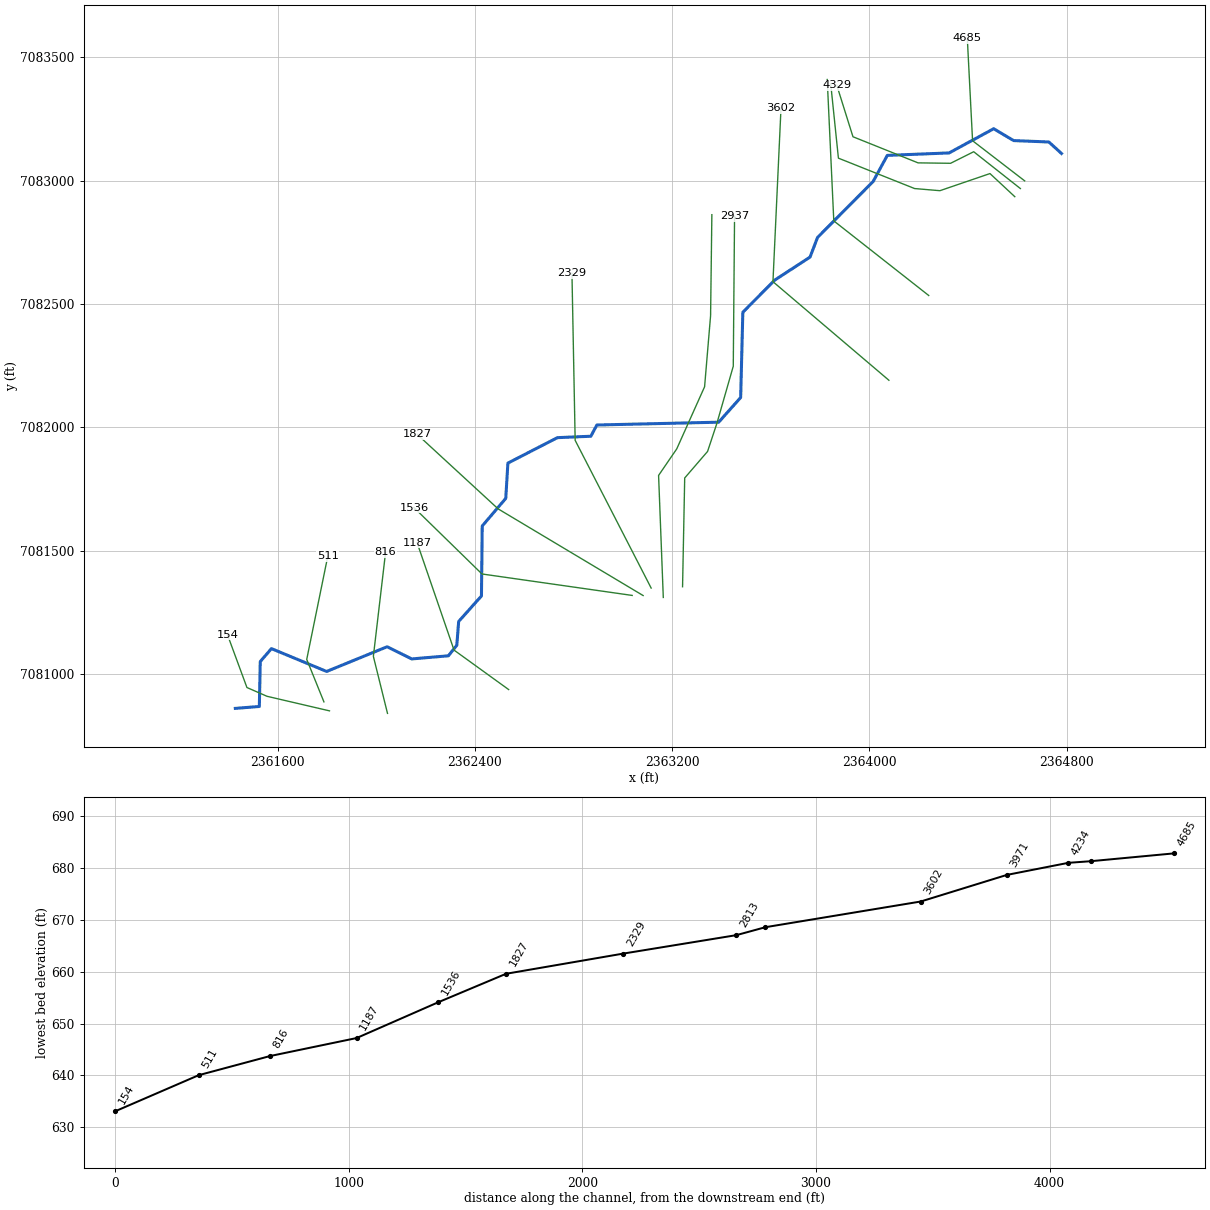
--- Graham Branch Tr 11.prj (project) ---

Proj Title=Graham Branch Tr 11 Base Level Engineering
Current Plan=p01
Default Exp/Contr=0.3,0.1
English Units
Geom File=g01
Flow File=f01
Plan File=p01
Y Axis Title=Elevation
X Axis Title(PF)=Main Channel Distance
X Axis Title(XS)=Station
BEGIN DESCRIPTION:
Graham Branch Tr 11
END DESCRIPTION:
DSS Export Rating Curves= 0
DSS Export Rating Curve Sorted= 0
DSS Export Volume Flow Curves= 0
DXF OffsetX= 0
DXF OffsetY= 0
DXF ScaleX= 1
DXF ScaleY= 10

--- Graham Branch Tr 11.p01 (plan) ---

Plan Title=Multiple Run
Short Identifier=Multiple
Geom File=g01
Flow File=f01
Subcritical Flow
K Sum by GR= 0
Std Step Tol= 0.01
Critical Tol= 0.01
Num of Std Step Trials= 20
Max Error Tol= 0.3
Flow Tol Ratio= 0.001
Split Flow NTrial= 30
Split Flow Tol= 0.02
Split Flow Ratio= 0.02
Log Output Level= 0
Friction Slope Method= 1
Unsteady Friction Slope Method= 2
Unsteady Bridges Friction Slope Method= 1
Parabolic Critical Depth
Global Vel Dist=  1 , 1 , 1
Global Log Level= 0
CheckData=True
Encroach Param= -1, 0, 0, 0
BEGIN DESCRIPTION:
Multiple Run
END DESCRIPTION:

--- Graham Branch Tr 11.f01 (steady flow) ---

Flow Title=Multiple
Program Version=4.10
Number of Profiles= 7
Profile Names=10-year,25-year,50-year,1pct_min,100-year,1pct_plu,500-year
River Rch & RM=Graham Branch Tr,Reach-1         ,4685
     380     508     612     367     733    1462    1050
Boundary for River Rch & Prof#=Graham Branch Tr,Reach-1         , 1
Up Type= 0
Dn Type= 3
Dn Slope=0.015
Boundary for River Rch & Prof#=Graham Branch Tr,Reach-1         , 2
Up Type= 0
Dn Type= 3
Dn Slope=0.015
Boundary for River Rch & Prof#=Graham Branch Tr,Reach-1         , 3
Up Type= 0
Dn Type= 3
Dn Slope=0.015
Boundary for River Rch & Prof#=Graham Branch Tr,Reach-1         , 4
Up Type= 0
Dn Type= 3
Dn Slope=0.015
Boundary for River Rch & Prof#=Graham Branch Tr,Reach-1         , 5
Up Type= 0
Dn Type= 3
Dn Slope=0.015
Boundary for River Rch & Prof#=Graham Branch Tr,Reach-1         , 6
Up Type= 0
Dn Type= 3
Dn Slope=0.015
Boundary for River Rch & Prof#=Graham Branch Tr,Reach-1         , 7
Up Type= 0
Dn Type= 3
Dn Slope=0.015
DSS Import GetInterval= 0
DSS Import GetPeak= 0
DSS Import FillOption= 0

--- Graham Branch Tr 11.g01 (geometry) ---

Geom Title=Existing Conditions
Program Version=4.10

River Reach=Graham Branch Tr,Reach-1
Reach XY= 30
        2364779.        7083110.      2364727.63       7083156.7
      2364584.93      7083162.29        2364504.      7083210.41
      2364323.07      7083112.24      2364072.52      7083102.31
      2364015.36       7082996.8      2363789.78      7082769.68
      2363759.23      7082689.87      2363615.79      7082596.37
      2363486.81      7082466.19      2363477.96      7082120.43
      2363388.83      7082020.47      2362894.96      7082009.04
      2362870.53      7081963.47      2362734.94      7081957.75
      2362534.18      7081854.59      2362525.44      7081711.48
      2362430.06      7081599.56      2362426.93      7081315.86
      2362334.54      7081212.42      2362326.93      7081115.69
      2362292.73      7081073.19      2362144.22      7081060.52
      2362044.39      7081109.91      2361799.18      7081009.72
      2361575.29      7081102.33      2361530.05       7081049.9
      2361526.25      7080867.75        2361429.        7080860.

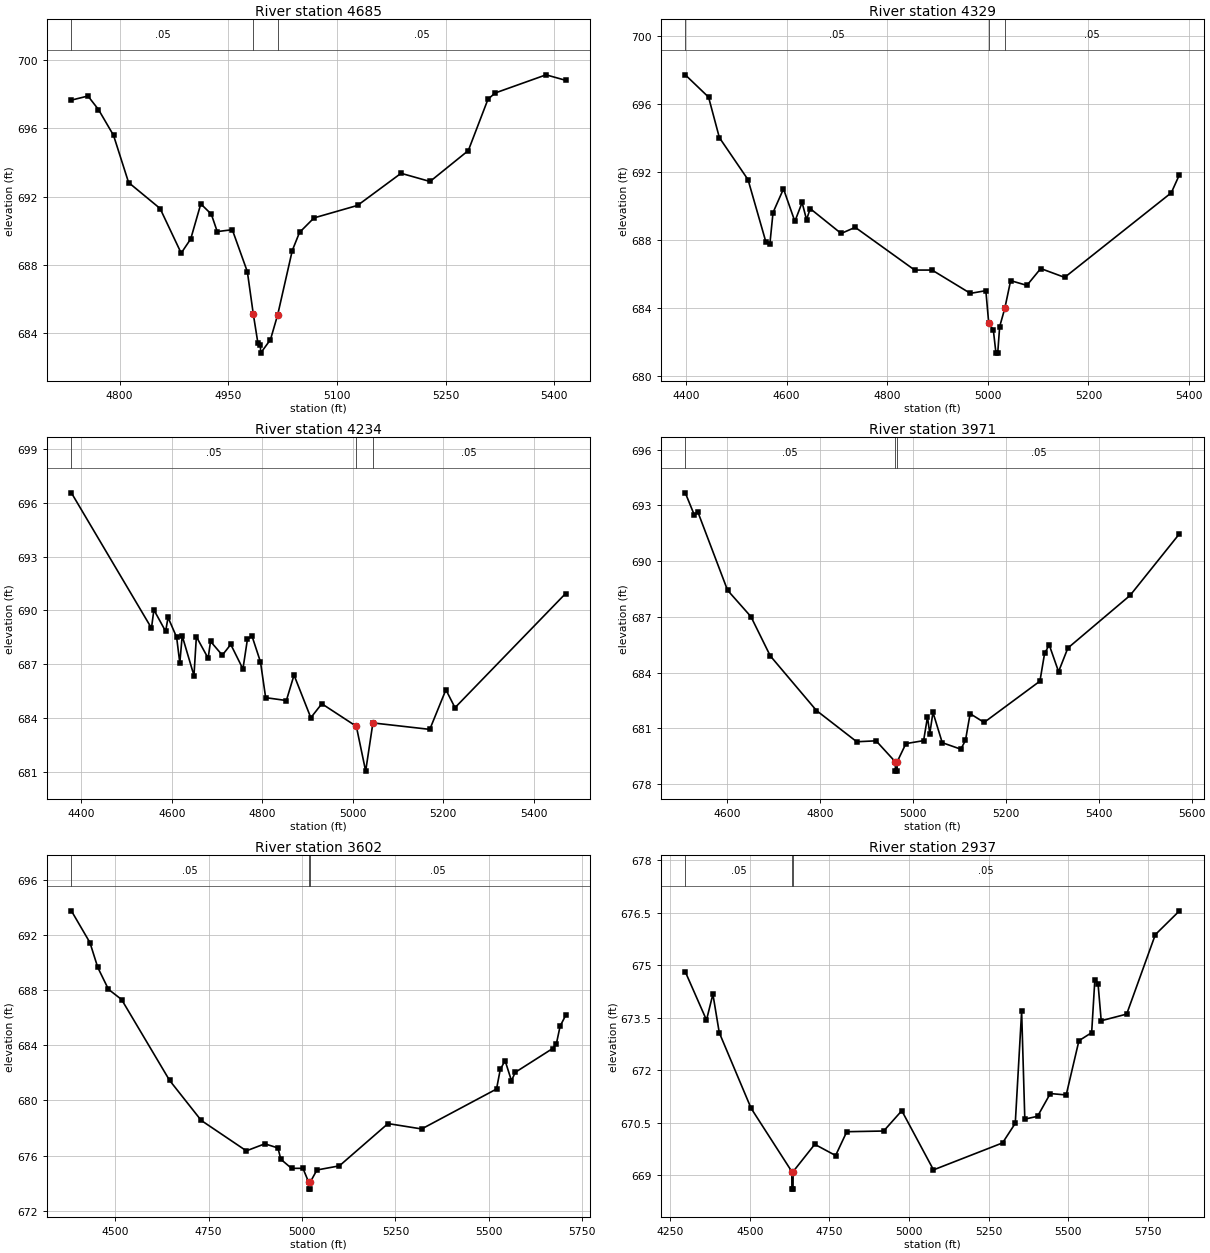
Type RM Length L Ch R = 1 ,4685    ,356,356,356
BEGIN DESCRIPTION:
Graham Branch Tr 11 13.0
END DESCRIPTION:
XS GIS Cut Line= 3
      2364629.56      7082999.05      2364418.32      7083161.69
        2364397.      7083576.94
#Sta/Elev= 30
  4733.4  697.65  4756.3  697.89  4770.8   697.1  4791.6  695.59  4812.4  692.83
  4855.9  691.31    4885   688.7  4898.2  689.53  4912.1  691.58  4926.6  690.98
  4934.8  689.96  4955.6  690.07  4976.4  687.61  4984.6  685.13  4990.9  683.45
  4994.4  683.35  4994.7  682.85  5008.3  683.64  5018.3   685.1  5038.4  688.85
  5048.4  689.91  5068.4  690.76  5128.5  691.49  5188.6  693.37  5228.6  692.89
  5281.5   694.7  5308.7  697.71  5318.7  698.07  5388.8  699.13  5415.8  698.81
#Mann= 3 ,-1 , 0
  4733.4     .05       0  4984.6    .033       0  5018.3     .05       0
Bank Sta=4984.6,5018.3
XS Rating Curve= 0 ,0
Exp/Cntr=0.3,0.1

Type RM Length L Ch R = 1 ,4329    ,95,95,95
BEGIN DESCRIPTION:
Mapping XS 18cf26c3
END DESCRIPTION:
XS GIS Cut Line= 6
      2364612.19      7082967.81      2364422.94      7083117.13
      2364329.19      7083070.25      2364197.25      7083071.99
      2363933.36      7083177.89      2363867.86      7083386.46
#Sta/Elev= 30
  4398.5  697.69  4444.8  696.38  4466.3     694  4523.3  691.53  4558.6  687.89
  4566.7  687.75    4573   689.6  4593.8  690.99  4616.4  689.08  4630.8  690.19
  4639.6  689.18  4646.9  689.83  4708.4  688.37  4736.4  688.73  4854.6  686.22
  4889.2  686.22  4965.4  684.85  4996.1  685.01  5001.8  683.12    5011   682.7
  5016.2  681.34  5019.7  681.34  5023.6   682.9  5033.8  683.97  5045.4   685.6
  5077.7  685.32  5105.2  686.31  5152.8  685.79  5364.8  690.76  5381.1  691.83
#Mann= 3 ,-1 , 0
  4398.5     .05       0  5001.8    .033       0  5033.8     .05       0
Bank Sta=5001.8,5033.8
XS Rating Curve= 0 ,0
Exp/Cntr=0.3,0.1

Type RM Length L Ch R = 1 ,4234    ,263,263,263
BEGIN DESCRIPTION:
Mapping XS 57c95699
END DESCRIPTION:
XS GIS Cut Line= 6
      2364589.58      7082934.86      2364488.92      7083028.59
      2364285.79      7082959.14      2364183.36      7082967.82
      2363874.33      7083091.09      2363843.09      7083393.13
#Sta/Elev= 30
    4378  696.56    4555  689.01  4560.3  690.03  4586.3  688.83  4591.6  689.61
  4610.6   688.5  4617.6  687.06  4622.9  688.58  4648.9  686.36  4654.2  688.53
  4680.2  687.33  4685.5  688.27  4711.5   687.5  4730.2   688.1  4757.1  686.73
  4767.1   688.4  4777.2  688.56  4795.9  687.12  4807.3  685.13  4853.1  684.97
    4870  686.39  4907.1  684.01  4931.4  684.79  5007.7  683.53  5028.3  681.03
  5044.3  683.72    5170  683.36  5205.6  685.57  5225.7  684.57  5470.1  690.94
#Mann= 3 ,-1 , 0
    4378     .05       0  5007.7    .033       0  5044.3     .05       0
Bank Sta=5007.7,5044.3
XS Rating Curve= 0 ,0
Exp/Cntr=0.3,0.1

Type RM Length L Ch R = 1 ,3971    ,369,369,369
BEGIN DESCRIPTION:
Graham Branch Tr 11 11.0
END DESCRIPTION:
XS GIS Cut Line= 3
      2364240.57      7082534.17      2363855.62      7082836.69
        2363829.      7083409.97
#Sta/Elev= 30
  4510.4  693.67  4529.7  692.49  4537.8  692.62  4601.4  688.43  4651.7  687.01
  4693.3   684.9  4792.7  681.96  4879.4  680.28    4921  680.33  4962.4   679.2
  4962.7   678.7  4966.2   678.7  4966.4   679.2  4985.2  680.18  5023.3  680.34
  5031.6  681.61  5036.6  680.72  5043.4  681.86  5063.4  680.23  5103.4  679.88
  5113.4  680.36  5123.4  681.79  5153.5  681.32  5273.6  683.54  5283.6  685.03
  5293.6  685.49  5313.7  684.05  5333.7  685.32  5467.5  688.15  5573.9  691.47
#Mann= 3 ,-1 , 0
  4510.4     .05       0  4962.4    .033       0  4966.4     .05       0
Bank Sta=4962.4,4966.4
XS Rating Curve= 0 ,0
Exp/Cntr=0.3,0.1

Type RM Length L Ch R = 1 ,3602    ,665,665,665
BEGIN DESCRIPTION:
Graham Branch Tr 11 10.0
END DESCRIPTION:
XS GIS Cut Line= 3
      2364079.12      7082190.41      2363608.91      7082590.21
       2363641.6      7083294.65
#Sta/Elev= 30
  4382.8  693.77  4432.5  691.46  4453.4  689.66    4482  688.07  4517.1  687.33
  4645.5  681.46  4730.2  678.55    4851  676.34  4900.4  676.85  4935.5  676.55
  4943.2  675.73  4971.8  675.07  5002.4  675.07  5017.8  674.06  5018.1  673.56
  5021.6  673.56  5021.8  674.06  5039.8  674.95  5099.9  675.25    5230  678.32
  5320.1  677.93  5520.4  680.83  5530.4  682.25  5543.3  682.89  5560.4  681.43
  5570.4  682.04  5670.5  683.77  5680.5  684.11  5690.5  685.39  5705.2  686.17
#Mann= 3 ,-1 , 0
  4382.8     .05       0  5017.8    .033       0  5021.8     .05       0
Bank Sta=5017.8,5021.8
XS Rating Curve= 0 ,0
Exp/Cntr=0.3,0.1

Type RM Length L Ch R = 1 ,2937    ,124,124,124
BEGIN DESCRIPTION:
Graham Branch Tr 11 9.0
END DESCRIPTION:
XS GIS Cut Line= 6
      2363242.39      7081353.27      2363251.07      7081794.21
      2363343.85      7081901.89      2363381.47      7082015.45
      2363448.02      7082247.38      2363453.22      7082855.87
#Sta/Elev= 30
  4297.2  674.81  4363.9  673.43    4384  674.17    4404  673.07    4504  670.91
    4632   669.1  4632.2   668.6  4635.7   668.6    4636   669.1    4704  669.88
  4769.5  669.56  4804.6  670.24  4920.5  670.26  4977.4  670.84    5077  669.15
  5293.9  669.92  5333.9  670.48  5353.9  673.68  5363.9   670.6  5403.9  670.68
  5443.9  671.33  5493.9  671.29  5533.9  672.84  5573.9  673.07  5583.9  674.58
  5593.9  674.47  5603.9  673.41  5683.9   673.6  5773.9  675.87  5849.8  676.55
#Mann= 3 ,-1 , 0
  4297.2     .05       0    4632    .033       0    4636     .05       0
Bank Sta=4632,4636
XS Rating Curve= 0 ,0
Exp/Cntr=0.3,0.1

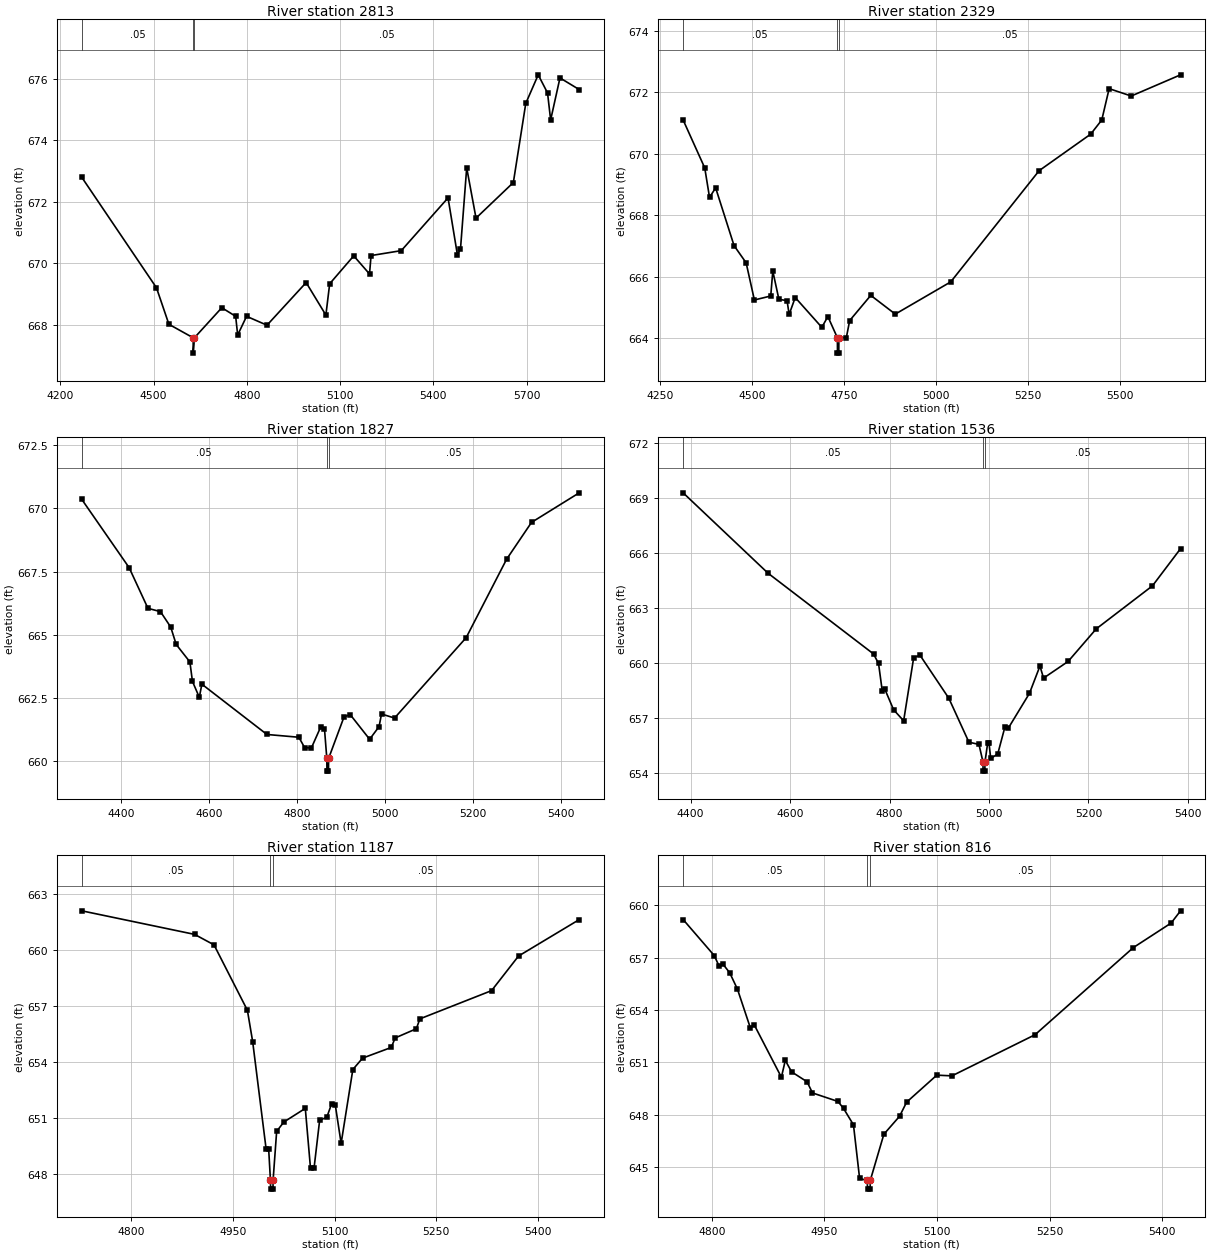
Type RM Length L Ch R = 1 ,2813    ,484,484,484
BEGIN DESCRIPTION:
Graham Branch Tr 11 8.0
END DESCRIPTION:
XS GIS Cut Line= 6
      2363164.26      7081309.87      2363145.17      7081804.63
      2363218.85      7081912.31       2363331.7      7082164.05
      2363356.01      7082452.24      2363361.21      7082861.93
#Sta/Elev= 30
  4268.8   672.8  4509.1   669.2  4549.1  668.01  4627.2  667.57  4627.4  667.07
  4631.2  667.57  4719.3  668.55  4763.9  668.27  4770.4  667.66    4799  668.27
  4864.7  667.98  4990.7  669.37  5054.2  668.31  5066.4  669.33  5143.8  670.24
  5194.6  669.65  5199.6  670.25  5296.8  670.41  5447.3  672.13  5477.3  670.28
  5487.3  670.46  5507.3  673.11  5537.3  671.47  5657.4  672.63  5697.4  675.21
  5737.4  676.14  5767.4  675.55  5777.4  674.67  5807.4  676.04  5869.3  675.66
#Mann= 3 ,-1 , 0
  4268.8     .05       0  4627.2     .04       0  4631.2     .05       0
Bank Sta=4627.2,4631.2
XS Rating Curve= 0 ,0
Exp/Cntr=0.3,0.1

Type RM Length L Ch R = 1 ,2329    ,502,502,502
BEGIN DESCRIPTION:
Mapping XS 0f0201ac
END DESCRIPTION:
XS GIS Cut Line= 3
      2363115.08      7081347.85      2362806.91      7081946.81
      2362793.89      7082623.89
#Sta/Elev= 30
  4313.3   671.1    4372  669.54    4385  668.58  4401.6  668.89  4451.6  667.01
  4484.4  666.45  4506.8  665.24  4551.2  665.37  4556.8  666.18  4573.4  665.26
  4595.5  665.22  4601.2  664.77  4617.7  665.32  4689.9  664.35  4706.4   664.7
  4732.2  664.01  4732.5  663.51    4736  663.51  4736.2  664.01  4756.4  664.01
  4765.6  664.57  4822.9  665.39  4889.4  664.78  5040.1  665.83  5280.1  669.45
  5420.2  670.64  5450.2   671.1  5470.2  672.12  5530.2  671.88  5664.1  672.57
#Mann= 3 ,-1 , 0
  4313.3     .05       0  4732.2    .033       0  4736.2     .05       0
Bank Sta=4732.2,4736.2
XS Rating Curve= 0 ,0
Exp/Cntr=0.3,0.1

Type RM Length L Ch R = 1 ,1827    ,291,291,291
BEGIN DESCRIPTION:
Mapping XS fd12d437
END DESCRIPTION:
XS GIS Cut Line= 3
       2363082.5      7081317.49      2362494.41      7081669.04
      2362166.75      7081970.66
#Sta/Elev= 30
  4310.6  670.36  4418.2  667.66    4461  666.05  4489.4  665.92  4512.7  665.31
  4525.2  664.62  4556.3  663.93  4562.1  663.16  4577.7  662.53  4583.5  663.05
  4731.4  661.06    4804  660.95    4817  660.54  4832.5  660.53  4853.9  661.37
  4862.2  661.28  4867.5  660.11  4867.8  659.61  4871.3  659.61  4871.5  660.11
  4906.5  661.75  4920.5  661.85  4964.8  660.87  4986.2  661.37  4991.8  661.87
  5021.4  661.71  5184.2  664.89    5276  667.99  5332.7  669.45  5441.1  670.62
#Mann= 3 ,-1 , 0
  4310.6     .05       0  4867.5    .033       0  4871.5     .05       0
Bank Sta=4867.5,4871.5
XS Rating Curve= 0 ,0
Exp/Cntr=0.3,0.1

Type RM Length L Ch R = 1 ,1536    ,349,349,349
BEGIN DESCRIPTION:
Graham Branch Tr 11 5.0
END DESCRIPTION:
XS GIS Cut Line= 3
      2363038.12      7081318.01       2362429.1      7081404.96
      2362153.33      7081674.19
#Sta/Elev= 30
  4384.8   669.3  4555.6  664.91  4767.8   660.5  4777.9  659.98  4785.5  658.45
  4790.5  658.58  4808.2  657.45  4828.4  656.85  4848.6   660.3  4861.3  660.43
  4919.3  658.08  4959.7  655.68  4979.9  655.56    4988   654.6  4988.2   654.1
  4991.7   654.1    4992   654.6  4997.5  655.65    5000  655.65  5003.6  654.79
  5017.7  655.04  5031.9  656.49    5039  656.45  5081.5  658.35  5102.6  659.84
  5109.8  659.18  5159.2  660.09  5215.8  661.87  5328.9  664.22  5385.4  666.25
#Mann= 3 ,-1 , 0
  4384.8     .05       0    4988    .033       0    4992     .05       0
Bank Sta=4988,4992
XS Rating Curve= 0 ,0
Exp/Cntr=0.3,0.1

Type RM Length L Ch R = 1 ,1187    ,371,371,371
BEGIN DESCRIPTION:
Graham Branch Tr 11 4.0
END DESCRIPTION:
XS GIS Cut Line= 3
      2362537.23      7080936.29      2362315.77      7081096.27
      2362165.76      7081532.39
#Sta/Elev= 30
  4726.8  662.09  4893.3  660.83    4922  660.27  4971.3  656.77  4979.1  655.09
  4998.9  649.36  5002.7  649.36  5005.3   647.7  5005.6   647.2  5009.1   647.2
  5009.3   647.7  5014.5  650.29  5025.1  650.79  5056.8  651.52  5064.5  648.31
  5069.8  648.35    5078  650.89  5088.5  651.04  5095.8  651.78    5101  651.72
  5109.7  649.65    5127   653.6  5141.4  654.21  5183.7  654.78  5189.5  655.29
  5220.7  655.78    5226  656.31  5331.8  657.82  5371.6  659.67  5461.2  661.62
#Mann= 3 ,-1 , 0
  4726.8     .05       0  5005.3    .033       0  5009.3     .05       0
Bank Sta=5005.3,5009.3
XS Rating Curve= 0 ,0
Exp/Cntr=0.3,0.1

Type RM Length L Ch R = 1 ,816     ,305,305,305
BEGIN DESCRIPTION:
Graham Branch Tr 11 3.0
END DESCRIPTION:
XS GIS Cut Line= 3
      2362045.95      7080839.74      2361988.65      7081070.95
      2362038.14      7081492.46
#Sta/Elev= 30
  4761.8  659.19  4803.3  657.12  4809.9   656.5  4815.1  656.62  4823.9  656.13
  4834.2  655.19  4851.3  652.98  4856.5  653.15  4892.7  650.14  4897.9  651.11
  4906.3  650.45  4926.9  649.88  4934.1  649.24  4968.1  648.75  4975.5  648.35
  4988.7  647.41  4996.9  644.33  5007.1  644.22  5007.4  643.72  5010.9  643.72
  5011.1  644.22  5029.2  646.87  5050.1   647.9  5059.5  648.71  5099.7  650.26
  5119.9  650.22  5230.6  652.58  5361.5  657.58  5411.9  658.99  5424.4  659.69
#Mann= 3 ,-1 , 0
  4761.8     .05       0  5007.1    .033       0  5011.1     .05       0
Bank Sta=5007.1,5011.1
XS Rating Curve= 0 ,0
Exp/Cntr=0.3,0.1

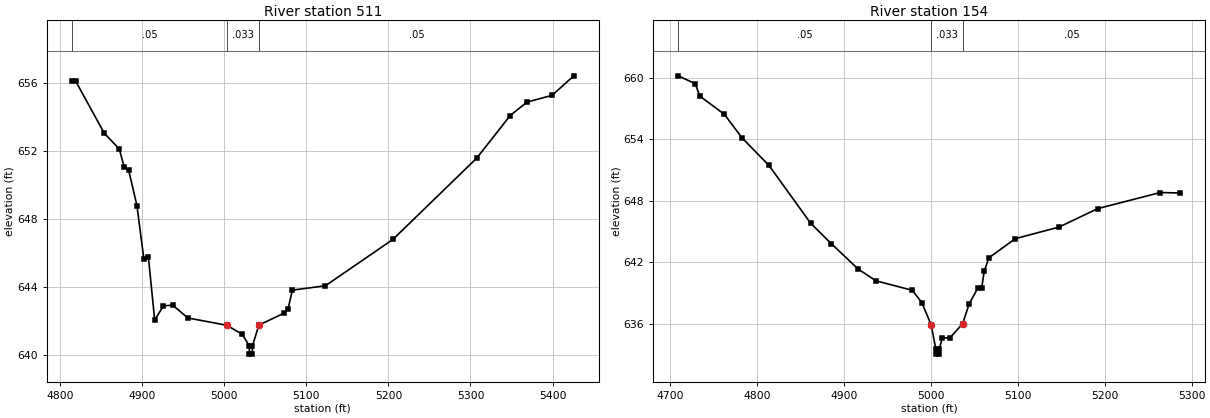
Type RM Length L Ch R = 1 ,511     ,357,357,357
BEGIN DESCRIPTION:
Graham Branch Tr 11 2.0
END DESCRIPTION:
XS GIS Cut Line= 3
      2361788.14      7080886.42      2361718.45      7081058.65
      2361803.58      7081475.96
#Sta/Elev= 30
  4814.2  656.13  4818.8  656.13  4853.9  653.04    4872  652.13    4878  651.08
  4883.4   650.9  4893.6  648.78  4902.1  645.61  4907.5  645.78  4915.2  642.04
  4925.9  642.87    4937  642.92  4955.7  642.16  5003.2  641.73  5021.8   641.2
  5030.4  640.53  5030.7  640.03  5034.2  640.03  5034.4  640.53  5042.2  641.74
  5072.7  642.44  5077.8  642.71    5083   643.8  5123.3  644.06  5205.5  646.79
  5307.6  651.58  5348.4  654.09  5368.8  654.88  5399.4  655.28  5425.9  656.43
#Mann= 3 ,-1 , 0
  4814.2     .05       0  5003.2    .033       0  5042.2     .05       0
Bank Sta=5003.2,5042.2
XS Rating Curve= 0 ,0
Exp/Cntr=0.3,0.1

Type RM Length L Ch R = 1 ,154     ,0,0,0
BEGIN DESCRIPTION:
Graham Branch Tr 11 1.0
END DESCRIPTION:
XS GIS Cut Line= 4
      2361810.69      7080849.96      2361557.54      7080908.96
      2361475.95      7080944.55      2361396.94        7081159.
#Sta/Elev= 30
  4709.4  660.19  4729.1  659.42  4734.2  658.22  4762.5  656.44    4783  654.13
  4813.8  651.46  4861.9  645.81  4885.7  643.82  4916.5  641.35    4937  640.21
  4978.7  639.29  4989.7  638.08  5000.5  635.89  5005.7  633.57  5005.9  633.07
  5009.4  633.07  5009.7  633.57  5013.1  634.62  5022.3  634.69  5036.6  636.03
  5044.1  637.97    5054  639.49  5058.4  639.49  5061.4  641.13  5066.7  642.45
  5097.2  644.32  5147.4  645.45    5192  647.25  5263.9  648.82  5286.9  648.77
#Mann= 3 ,-1 , 0
  4709.4     .05       0  5000.5    .033       0  5036.6     .05       0
Bank Sta=5000.5,5036.6
XS Rating Curve= 0 ,0
Exp/Cntr=0.3,0.1

Chan Stop Cuts=-1
Use User Specified Reach Order=0
Composite Channel Slope=5