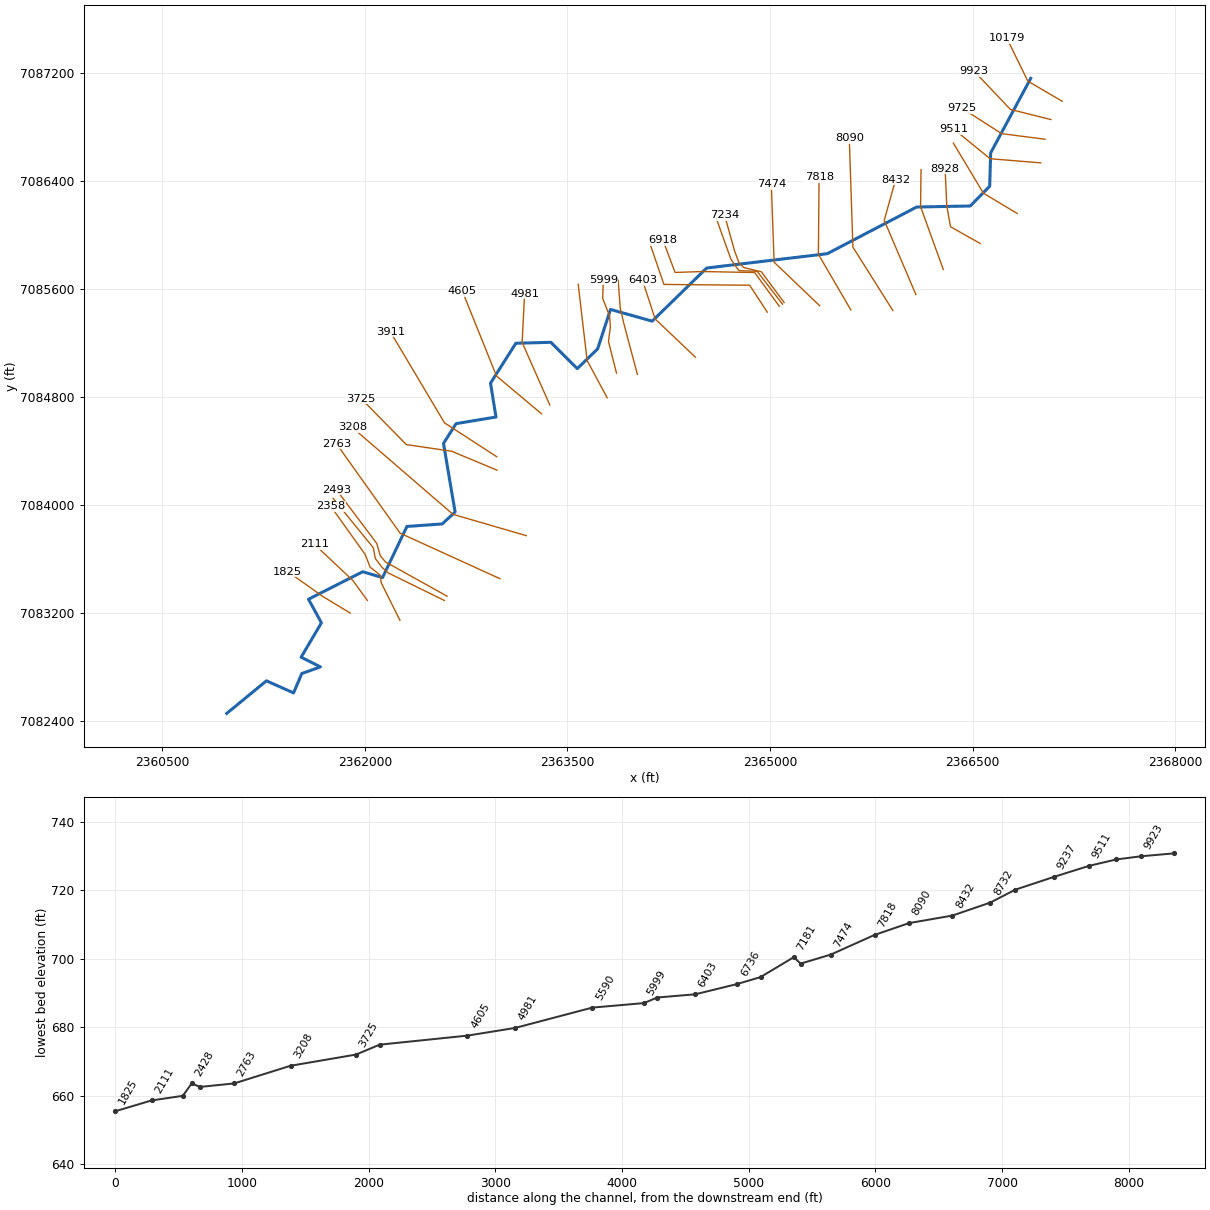
--- Graham Branch Tr 12.prj (project) ---

Proj Title=Graham Branch Tr 12 Base Level Engineering
Current Plan=p01
Default Exp/Contr=0.3,0.1
English Units
Geom File=g01
Flow File=f01
Plan File=p01
Y Axis Title=Elevation
X Axis Title(PF)=Main Channel Distance
X Axis Title(XS)=Station
BEGIN DESCRIPTION:
Graham Branch Tr 12
END DESCRIPTION:
DSS Export Rating Curves= 0
DSS Export Rating Curve Sorted= 0
DSS Export Volume Flow Curves= 0
DXF OffsetX= 0
DXF OffsetY= 0
DXF ScaleX= 1
DXF ScaleY= 10

--- Graham Branch Tr 12.p01 (plan) ---

Plan Title=Multiple Run
Short Identifier=Multiple
Geom File=g01
Flow File=f01
Subcritical Flow
K Sum by GR= 0
Std Step Tol= 0.01
Critical Tol= 0.01
Num of Std Step Trials= 20
Max Error Tol= 0.3
Flow Tol Ratio= 0.001
Split Flow NTrial= 30
Split Flow Tol= 0.02
Split Flow Ratio= 0.02
Log Output Level= 0
Friction Slope Method= 1
Unsteady Friction Slope Method= 2
Unsteady Bridges Friction Slope Method= 1
Parabolic Critical Depth
Global Vel Dist=  1 , 1 , 1
Global Log Level= 0
CheckData=True
Encroach Param= -1, 0, 0, 0
BEGIN DESCRIPTION:
Multiple Run
END DESCRIPTION:

--- Graham Branch Tr 12.f01 (steady flow) ---

Flow Title=Multiple
Program Version=4.10
Number of Profiles= 7
Profile Names=10-year,25-year,50-year,1pct_min,100-year,1pct_plu,500-year
River Rch & RM=Graham Branch Tr,Reach-1         ,10179
     133     164     187     107     213     424     274
River Rch & RM=Graham Branch Tr,Reach-1         ,7818
     381     506     607     362     722    1440    1022
River Rch & RM=Graham Branch Tr,Reach-1         ,2493
     437     586     706     423     844    1683    1207
Boundary for River Rch & Prof#=Graham Branch Tr,Reach-1         , 1
Up Type= 0
Dn Type= 3
Dn Slope=0.00939
Boundary for River Rch & Prof#=Graham Branch Tr,Reach-1         , 2
Up Type= 0
Dn Type= 3
Dn Slope=0.00939
Boundary for River Rch & Prof#=Graham Branch Tr,Reach-1         , 3
Up Type= 0
Dn Type= 3
Dn Slope=0.00939
Boundary for River Rch & Prof#=Graham Branch Tr,Reach-1         , 4
Up Type= 0
Dn Type= 3
Dn Slope=0.00939
Boundary for River Rch & Prof#=Graham Branch Tr,Reach-1         , 5
Up Type= 0
Dn Type= 3
Dn Slope=0.00939
Boundary for River Rch & Prof#=Graham Branch Tr,Reach-1         , 6
Up Type= 0
Dn Type= 3
Dn Slope=0.00939
Boundary for River Rch & Prof#=Graham Branch Tr,Reach-1         , 7
Up Type= 0
Dn Type= 3
Dn Slope=0.00939
DSS Import GetInterval= 0
DSS Import GetPeak= 0
DSS Import FillOption= 0

--- Graham Branch Tr 12.g01 (geometry) ---

Geom Title=Existing Conditions
Program Version=4.10

River Reach=Graham Branch Tr,Reach-1
Reach XY= 30
        2366929.        7087160.      2366632.75      7086608.45
      2366625.46      7086361.46      2366481.45      7086215.46
      2366084.94      7086207.74      2365423.06      7085862.26
      2364530.55      7085756.25      2364127.35       7085363.1
      2363818.88      7085449.66      2363723.53      7085157.55
      2363572.91      7085011.56      2363377.55      7085206.47
      2363118.49      7085199.52      2362930.96      7084904.11
      2362971.38       7084653.5       2362676.3      7084604.64
      2362582.75      7084458.45      2362668.82      7083950.29
      2362573.16      7083862.05       2362312.2      7083843.58
      2362131.58      7083464.97      2361985.04      7083508.37
       2361583.6      7083304.74      2361679.37      7083130.37
      2361529.11      7082875.72      2361671.81      7082803.98
      2361534.12      7082754.88      2361473.17      7082611.53
      2361272.25       7082700.9        2360979.        7082460.

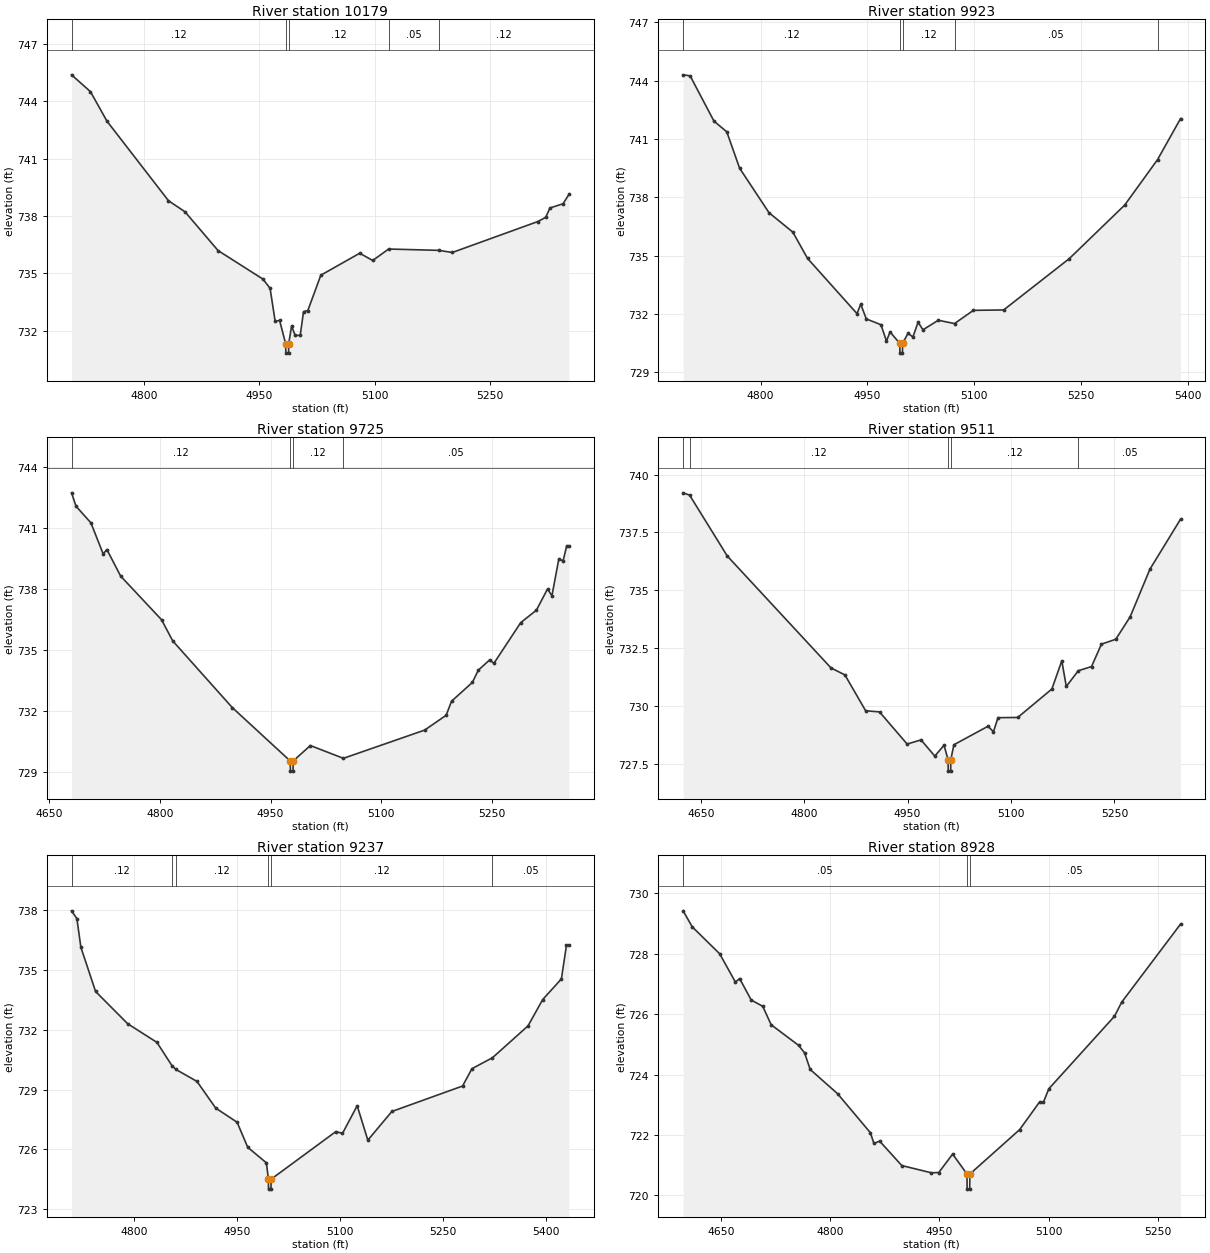
Type RM Length L Ch R = 1 ,10179   ,256,256,256
BEGIN DESCRIPTION:
Graham Branch Tr 12 28.0
END DESCRIPTION:
XS GIS Cut Line= 3
      2367161.78      7086990.57      2366907.78      7087139.61
      2366752.73      7087456.28
#Sta/Elev= 30
  4705.5  745.39  4730.1  744.51  4751.5  742.97  4831.6   738.8  4853.1  738.22
  4896.1  736.19  4954.7  734.69  4963.8  734.21  4970.4  732.49  4976.2  732.53
    4984  731.32  4984.3  730.82  4987.8  730.82    4988  731.32  4991.8  732.24
  4996.4  731.75    5003  731.75  5007.3  732.99  5012.9  733.05  5029.8   734.9
  5080.4  736.05  5097.3  735.67    5118  736.27  5183.2   736.2  5200.9  736.09
  5312.2  737.71  5322.4  737.93  5327.9  738.42  5344.9  738.64  5352.6  739.13
#Mann= 5 ,-1 , 0
  4705.5     .12       0    4984     .07       0    4988     .12       0
    5118     .05       0  5183.2     .12       0
Bank Sta=4984,4988
XS Rating Curve= 0 ,0
Exp/Cntr=0.3,0.1

Type RM Length L Ch R = 1 ,9923    ,198,198,198
BEGIN DESCRIPTION:
Graham Branch Tr 12 27.0
END DESCRIPTION:
XS GIS Cut Line= 3
      2367078.48      7086855.13      2366778.81      7086930.08
      2366510.75       7087212.8
#Sta/Elev= 30
  4691.1   744.3  4700.9  744.25  4734.4  741.92  4752.4  741.37  4770.4   739.5
  4811.7  737.21  4845.2  736.21  4865.8  734.86  4935.3  732.02  4940.5  732.51
  4948.3  731.75  4968.9  731.45  4976.6  730.61  4981.7  731.08  4995.3  730.49
  4995.6  729.99  4999.1  729.99  4999.3  730.49  5006.9  731.01  5013.8  730.82
    5021  731.58  5027.9  731.19  5049.4  731.68  5072.2  731.51  5098.7  732.19
  5141.2  732.21  5233.4  734.85  5311.1   737.6  5357.3  739.94  5389.6  742.05
#Mann= 5 ,-1 , 0
  4691.1     .12       0  4995.3     .07       0  4999.3     .12       0
  5072.2     .05       0  5357.3     .12       0
Bank Sta=4995.3,4999.3
XS Rating Curve= 0 ,0
Exp/Cntr=0.3,0.1

Type RM Length L Ch R = 1 ,9725    ,214,214,214
BEGIN DESCRIPTION:
Mapping XS 2aabf4e6
END DESCRIPTION:
XS GIS Cut Line= 3
      2367035.05       7086709.3      2366713.91      7086750.96
       2366418.8      7086940.18
#Sta/Elev= 30
  4680.2  742.75  4686.3  742.09  4706.5  741.27  4723.1  739.74  4728.1  739.96
  4746.8  738.65  4802.3   736.5  4817.4  735.46  4898.1  732.18  4976.7  729.55
    4977  729.05  4980.5  729.05  4980.7  729.55    5004  730.31  5048.8  729.68
    5159  731.07  5188.1   731.8  5195.4  732.49  5223.7  733.42  5231.7  734.02
  5246.9  734.52  5252.9  734.36  5289.2  736.36  5310.4  736.97  5325.6  738.02
  5331.5  737.68  5340.8  739.48  5346.7  739.41  5351.5  740.13  5354.6  740.13
#Mann= 4 ,-1 , 0
  4680.2     .12       0  4976.7     .07       0  4980.7     .12       0
  5048.8     .05       0
Bank Sta=4976.7,4980.7
XS Rating Curve= 0 ,0
Exp/Cntr=0.3,0.1

Type RM Length L Ch R = 1 ,9511    ,274,274,274
BEGIN DESCRIPTION:
Graham Branch Tr 12 26.0
END DESCRIPTION:
XS GIS Cut Line= 3
      2367002.82      7086534.71      2366628.56      7086565.18
      2366360.48      7086783.77
#Sta/Elev= 30
  4624.5  739.21  4633.9  739.11  4688.5  736.48    4839  731.64  4859.1  731.34
  4889.2  729.79  4909.3  729.74  4949.4  728.35  4969.5  728.53  4989.5  727.83
  5002.9   728.3  5008.7  727.68    5009  727.18  5012.5  727.18  5012.7  727.68
  5017.2  728.32  5066.7  729.12  5074.6  728.88  5081.1  729.49  5109.8   729.5
  5159.3  730.73  5173.7  731.95  5180.2  730.84  5197.6  731.52  5216.8   731.7
  5231.2  732.67    5252  732.88  5272.8  733.85  5301.5  735.91  5345.9  738.07
#Mann= 5 ,-1 , 0
  4624.5     .05       0  4633.9     .12       0  5008.7     .07       0
  5012.7     .12       0  5197.6     .05       0
Bank Sta=5008.7,5012.7
XS Rating Curve= 0 ,0
Exp/Cntr=0.3,0.1

Type RM Length L Ch R = 1 ,9237    ,309,309,309
BEGIN DESCRIPTION:
Graham Branch Tr 12 25.0
END DESCRIPTION:
XS GIS Cut Line= 3
      2366829.03      7086159.98        2366579.        7086310.
      2366356.32      7086681.13
#Sta/Elev= 30
  4708.7  737.98  4716.5  737.59  4722.3  736.15  4743.7  733.93  4790.4  732.31
  4833.1  731.37  4854.8  730.21  4860.8  730.01  4891.4  729.41  4918.7  728.07
  4949.8  727.36  4965.3   726.1  4992.5  725.32  4995.4   724.5  4995.6     724
  4999.1     724  4999.4   724.5  5093.6  726.89  5103.3   726.8  5124.7  728.19
  5140.2  726.46  5175.2   727.9  5278.2  729.18  5291.8  730.05  5321.7   730.6
  5373.5   732.2  5394.8  733.52  5422.1  734.56  5429.5  736.26  5433.1  736.26
#Mann= 6 ,-1 , 0
  4708.7     .12       0  4854.8     .05       0  4860.8     .12       0
  4995.4     .07       0  4999.4     .12       0  5321.7     .05       0
Bank Sta=4995.4,4999.4
XS Rating Curve= 0 ,0
Exp/Cntr=0.3,0.1

Type RM Length L Ch R = 1 ,8928    ,196,196,196
BEGIN DESCRIPTION:
Mapping XS 33a1b8c9
END DESCRIPTION:
XS GIS Cut Line= 4
       2366554.2      7085938.45      2366335.43      7086061.72
      2366307.66      7086217.97       2366295.5      7086490.59
#Sta/Elev= 30
  4598.3  729.42  4610.8  728.89  4648.4     728  4670.1  727.06  4675.8  727.18
  4691.7  726.47  4707.6  726.26  4719.1  725.65  4756.7  724.97    4765  724.72
  4772.7  724.17  4810.2  723.37  4855.2  722.08  4860.2  721.72    4868   721.8
  4898.4  720.99  4939.1  720.75  4949.2  720.76  4968.2  721.37  4987.9  720.71
  4988.1  720.21  4991.6  720.21  4991.9  720.71  5060.2  722.18  5087.7   723.1
  5092.7  723.08  5100.2  723.53  5190.3  725.93  5200.3   726.4    5281  728.98
#Mann= 3 ,-1 , 0
  4598.3     .05       0  4987.9    .033       0  4991.9     .05       0
Bank Sta=4987.9,4991.9
XS Rating Curve= 0 ,0
Exp/Cntr=0.3,0.1

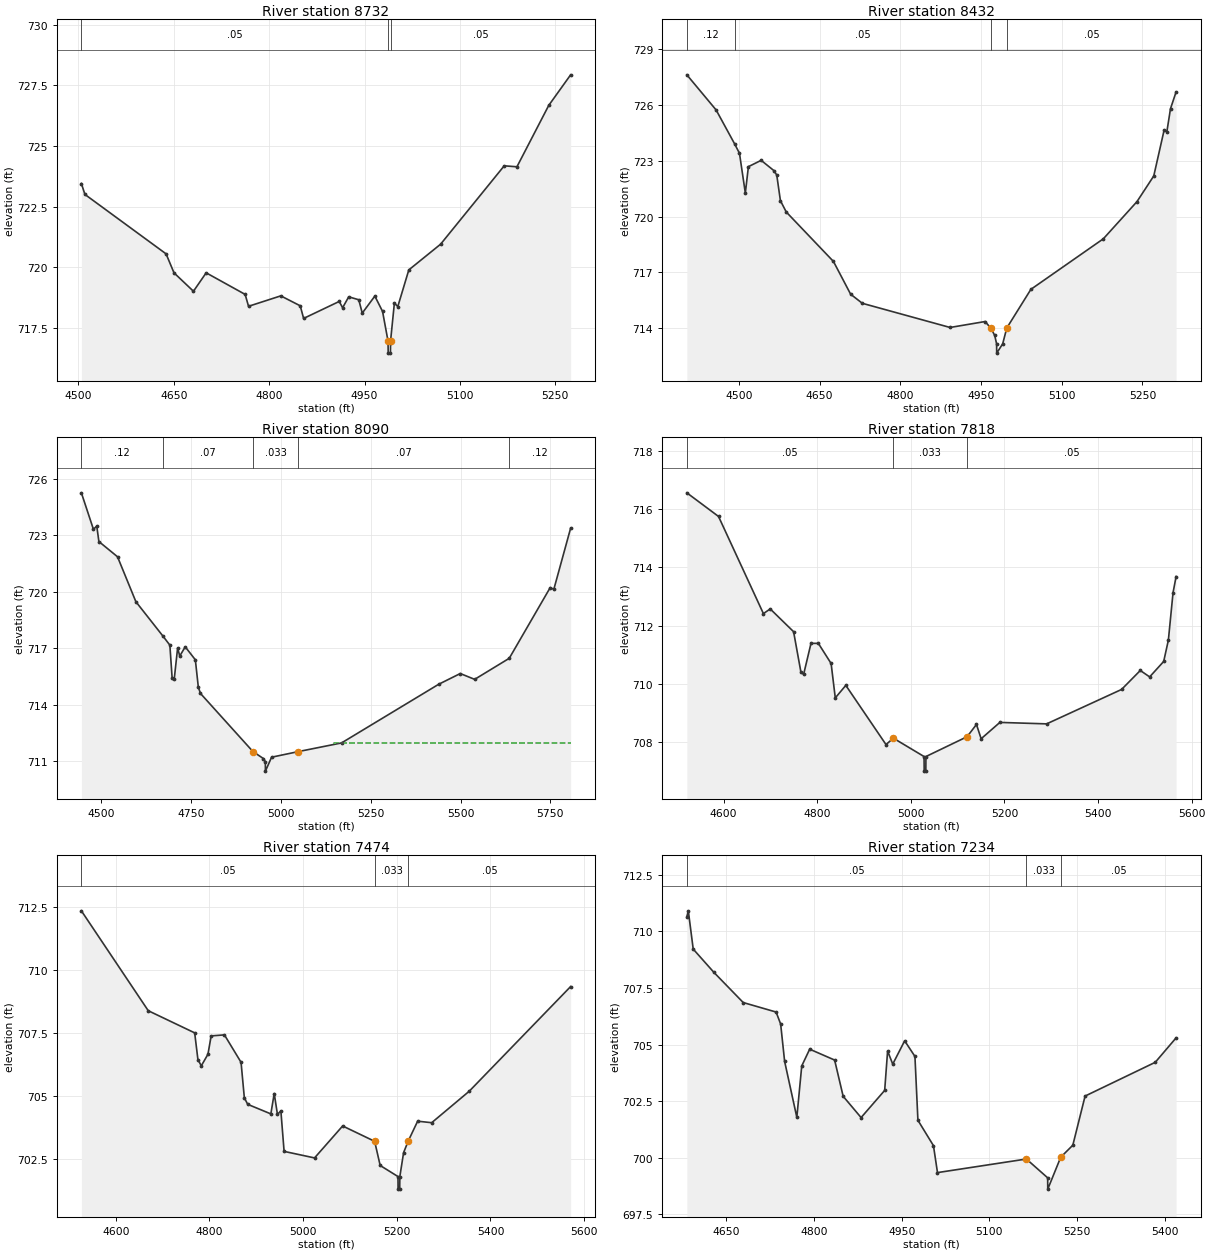
Type RM Length L Ch R = 1 ,8732    ,300,300,300
BEGIN DESCRIPTION:
Graham Branch Tr 12 23.0
END DESCRIPTION:
XS GIS Cut Line= 3
      2366282.31      7085744.77      2366113.82      7086210.43
      2366117.38      7086484.41
#Sta/Elev= 30
  4504.8  723.45  4510.4     723    4638  720.55  4650.4  719.77    4681  719.01
    4701  719.77  4762.3  718.88  4767.6  718.39  4818.3  718.82  4848.9  718.41
  4854.2  717.89  4910.2  718.59  4915.5  718.33  4925.1  718.78  4940.9  718.66
  4946.4  718.11  4966.2  718.81  4978.3  718.18  4986.9  716.96  4987.2  716.46
  4990.7  716.46  4990.9  716.96  4996.9  718.52  5002.3  718.38  5019.6  719.89
  5069.6  720.95  5169.6  724.18  5189.6  724.14  5239.6  726.67    5274  727.93
#Mann= 3 ,-1 , 0
  4504.8     .05       0  4986.9    .033       0  4990.9     .05       0
Bank Sta=4986.9,4990.9
XS Rating Curve= 0 ,0
Exp/Cntr=0.3,0.1

Type RM Length L Ch R = 1 ,8432    ,342,342,342
BEGIN DESCRIPTION:
Graham Branch Tr 12 22.0
END DESCRIPTION:
XS GIS Cut Line= 3
        2366079.        7085560.      2365845.01      7086108.91
        2365929.      7086410.01
#Sta/Elev= 30
  4403.3  727.63  4457.7  725.74    4492  723.92  4501.1  723.41    4512  721.27
  4517.7  722.69  4541.4  723.03    4565  722.48  4570.4  722.24  4577.2  720.86
  4588.1  720.25  4675.8  717.59  4707.7  715.83  4729.4  715.34  4892.5  714.04
  4957.7  714.36  4968.6  713.99  4975.5  713.61    4979  713.16  4979.2  712.66
  4990.3  713.16  4997.9  714.01  5042.7  716.09  5177.4  718.81  5239.9  720.81
  5271.1  722.19  5290.3  724.65  5295.5  724.58  5302.2  725.81  5312.6  726.71
#Mann= 4 ,-1 , 0
  4403.3     .12       0    4492     .05       0  4968.6    .033       0
  4997.9     .05       0
Bank Sta=4968.6,4997.9
XS Rating Curve= 0 ,0
Exp/Cntr=0.3,0.1

Type RM Length L Ch R = 1 ,8090    ,272,272,272
BEGIN DESCRIPTION:
Graham Branch Tr 12 21.0
END DESCRIPTION:
XS GIS Cut Line= 3
      2365908.74      7085441.77      2365613.04      7085910.97
      2365586.18      7086716.72
#Sta/Elev= 30
  4445.4  725.26  4478.9  723.32  4488.2  723.49  4494.1  722.67  4545.9  721.86
    4597  719.47  4672.7  717.63  4691.5  717.16  4697.8  715.42  4703.7  715.36
  4713.1  717.01    4719  716.58  4734.3  717.07  4762.4  716.38  4770.7  714.92
  4776.7  714.59  4922.6   711.5  4951.6  711.13  4957.1  710.96  4957.3  710.46
  4974.4   711.2  5049.1   711.5  5169.1  711.96  5439.3  715.08  5499.3  715.65
  5539.3  715.34  5635.5  716.46  5749.4  720.22  5759.5  720.13  5806.2  723.38
#Mann= 5 ,-1 , 0
  4445.4     .12       0  4672.7     .07       0  4922.6    .033       0
  5049.1     .07       0  5635.5     .12       0
#XS Ineff= 2 , 0
       0                  5149.1       0  711.97
Permanent Ineff=
       F       F
Bank Sta=4922.6,5049.1
XS Rating Curve= 0 ,0
Exp/Cntr=0.3,0.1

Type RM Length L Ch R = 1 ,7818    ,344,344,344
BEGIN DESCRIPTION:
Graham Branch Tr 12 20.0
END DESCRIPTION:
XS GIS Cut Line= 3
      2365597.89      7085446.13      2365357.48      7085857.73
      2365362.68      7086426.54
#Sta/Elev= 30
  4521.3  716.55    4589  715.74  4684.9  712.41  4699.5  712.57  4749.4  711.79
  4765.1   710.4  4770.9  710.33  4786.6  711.39  4802.3  711.39  4829.6   710.7
  4838.5  709.52    4861  709.95  4946.9  707.92  4962.6  708.14  5028.2  707.51
  5028.5  707.01    5032  707.01  5032.2  707.51  5120.2  708.19  5140.2  708.61
  5150.2  708.12  5190.2  708.68  5290.2  708.63  5450.3  709.81  5490.3  710.46
  5510.3  710.24  5540.3  710.77  5550.3   711.5  5560.3  713.13  5566.8  713.68
#Mann= 3 ,-1 , 0
  4521.3     .05       0  4962.6    .033       0  5120.2     .05       0
Bank Sta=4962.6,5120.2
XS Rating Curve= 0 ,0
Exp/Cntr=0.3,0.1

Type RM Length L Ch R = 1 ,7474    ,240,240,240
BEGIN DESCRIPTION:
Graham Branch Tr 12 19.0
END DESCRIPTION:
XS GIS Cut Line= 3
      2365367.65      7085476.73      2365029.83      7085799.43
      2365009.09      7086376.38
#Sta/Elev= 30
  4526.6  712.35  4669.4  708.38  4768.5   707.5  4775.4  706.44  4782.6  706.19
  4796.8  706.65  4803.7  707.38    4832  707.42  4867.5  706.33  4874.5  704.92
  4881.7  704.66  4931.1  704.28  4938.3  705.09  4945.2  704.26  4952.5   704.4
  4959.4  702.79  5024.4  702.53  5084.4   703.8  5152.7  703.19  5164.5  702.23
  5202.5  701.79  5202.7  701.29  5206.2  701.29  5206.5  701.79  5214.5  702.74
 5224.47 703.204  5244.5  703.99  5274.5  703.93  5354.6  705.18  5571.1  709.34
#Mann= 3 ,-1 , 0
  4526.6     .05       0  5152.7    .033       0 5224.47     .05       0
#XS Ineff= 2 , 0
       0  5084.4   703.8               0
Permanent Ineff=
       F       F
Bank Sta=5152.7,5224.47
XS Rating Curve= 0 ,0
Exp/Cntr=0.3,0.1

Type RM Length L Ch R = 1 ,7234    ,53,53,53
BEGIN DESCRIPTION:
Mapping XS 0a3290af
END DESCRIPTION:
XS GIS Cut Line= 6
      2365104.02      7085500.95      2364935.61      7085728.39
       2364805.4      7085759.64      2364770.68      7085792.63
      2364737.69      7085881.17      2364663.05      7086148.48
#Sta/Elev= 30
  4582.2  710.65  4584.7  710.91  4593.1  709.22  4628.6  708.19  4678.7  706.86
    4735  706.44  4742.8  705.91  4749.6  704.26  4770.5  701.79  4778.9  704.06
  4792.5   704.8  4835.2  704.32  4849.8  702.72  4880.5  701.78  4920.9  702.98
  4925.9  704.72  4934.7  704.14  4955.1  705.17  4972.7  704.48  4977.8  701.66
  5004.4  700.54  5011.3  699.35  5163.5  699.95  5199.9  699.12  5200.1  698.62
  5222.3  700.03    5243  700.56    5264  702.73  5384.1  704.22  5419.8   705.3
#Mann= 3 ,-1 , 0
  4582.2     .05       0  5163.5    .033       0  5222.3     .05       0
#XS Ineff= 2 , 0
       0  4955.1  705.17               0
Permanent Ineff=
       F       F
Bank Sta=5163.5,5222.3
XS Rating Curve= 0 ,0
Exp/Cntr=0.3,0.1

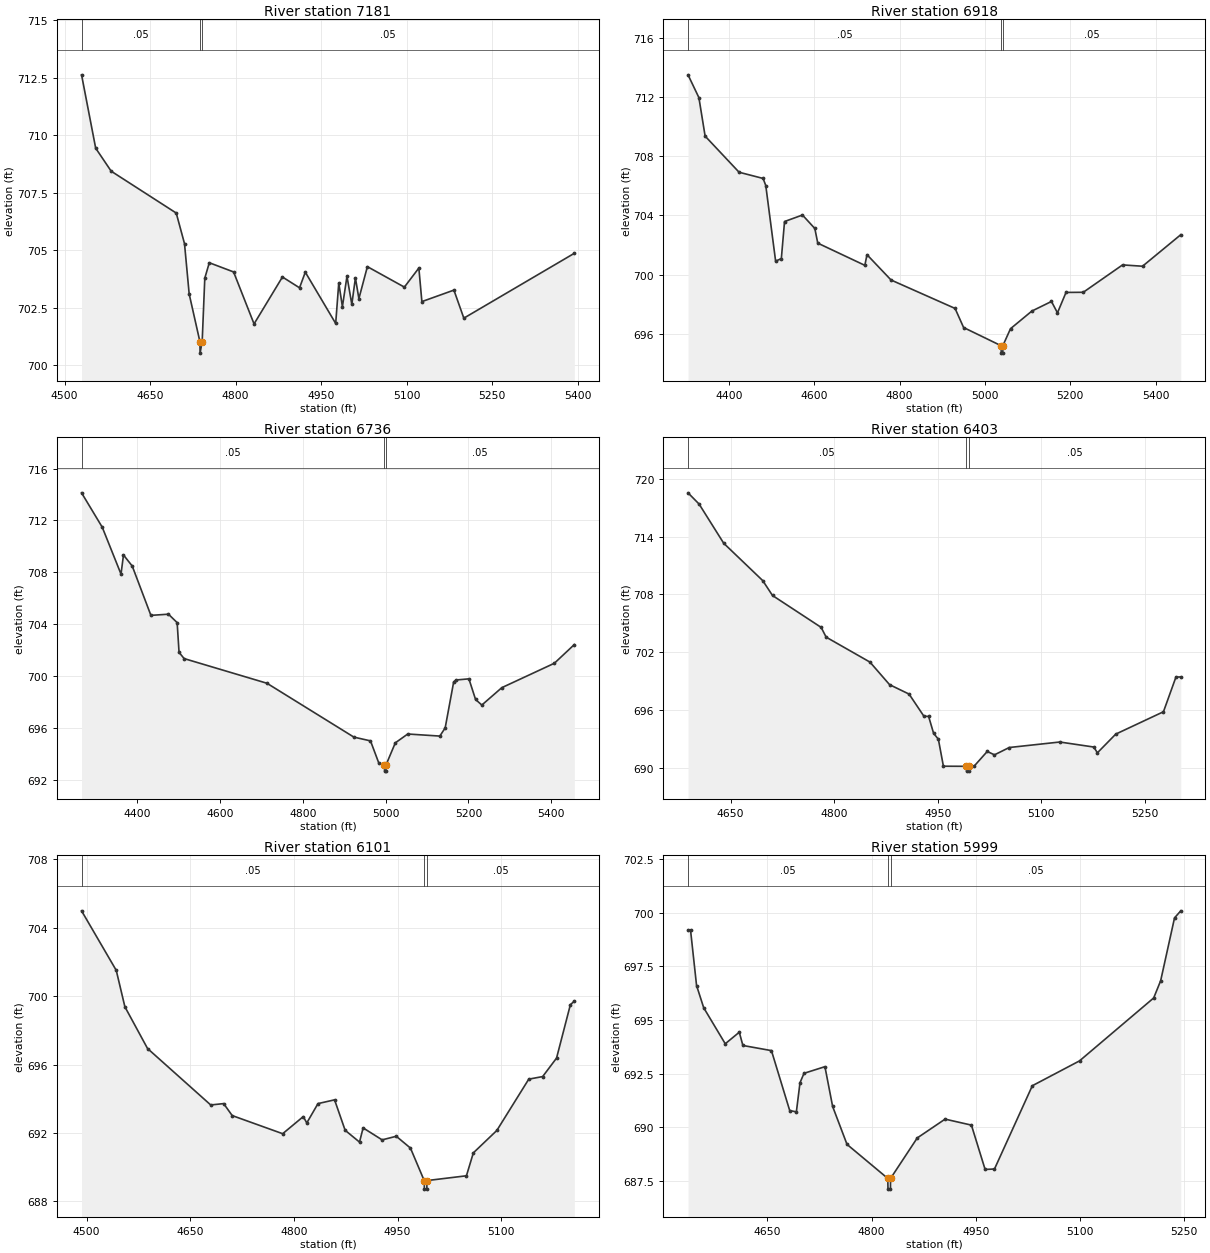
Type RM Length L Ch R = 1 ,7181    ,263,263,263
BEGIN DESCRIPTION:
Mapping XS 59072c1f
END DESCRIPTION:
XS GIS Cut Line= 6
      2365091.85      7085488.82      2364904.36      7085731.86
      2364770.68      7085737.07      2364749.84      7085763.11
      2364709.91      7085822.14      2364602.28      7086122.48
#Sta/Elev= 30
  4529.9  712.62  4554.7  709.43  4581.9  708.43    4696  706.61  4710.5  705.28
  4718.7  703.09  4737.5  701.02  4737.8  700.52  4741.5  701.02  4746.1  703.78
    4754  704.45  4796.6  704.05  4832.5  701.79  4882.3  703.83  4912.3  703.36
  4922.4  704.04  4975.7  701.81  4981.1  703.57  4987.5  702.54  4995.5  703.86
    5004  702.64  5010.3  703.79  5016.4  702.89  5031.3  704.28  5096.2  703.39
  5121.6  704.22  5126.9  702.76  5183.1  703.26  5200.5  702.04  5394.3  704.86
#Mann= 3 ,-1 , 0
  4529.9     .05       0  4737.5    .033       0  4741.5     .05       0
Bank Sta=4737.5,4741.5
XS Rating Curve= 0 ,0
Exp/Cntr=0.3,0.1

Type RM Length L Ch R = 1 ,6918    ,182,182,182
BEGIN DESCRIPTION:
Graham Branch Tr 12 17.0
END DESCRIPTION:
XS GIS Cut Line= 5
       2365068.2       7085473.3      2364885.91      7085722.93
      2364498.88      7085730.28      2364296.81      7085723.47
      2364206.44      7085963.96
#Sta/Elev= 30
  4303.8  713.49  4329.3  711.95  4343.9  709.35  4423.5  706.91  4479.9  706.49
  4486.1  706.01  4509.2   700.9  4522.6  701.08  4530.1  703.58  4572.1  704.02
  4601.1  703.11    4608  702.12  4718.4  700.62  4723.4  701.34  4779.8  699.63
  4929.9  697.71  4949.9  696.42  5037.9  695.19  5038.2  694.69  5041.7  694.69
  5041.9  695.19  5059.9  696.34  5109.9  697.53  5155.9  698.18    5170  697.41
    5190  698.79  5230.5   698.8  5322.6  700.65  5369.4  700.56  5459.1  702.69
#Mann= 3 ,-1 , 0
  4303.8     .05       0  5037.9    .033       0  5041.9     .05       0
Bank Sta=5037.9,5041.9
XS Rating Curve= 0 ,0
Exp/Cntr=0.3,0.1

Type RM Length L Ch R = 1 ,6736    ,333,333,333
BEGIN DESCRIPTION:
Graham Branch Tr 12 16.0
END DESCRIPTION:
XS GIS Cut Line= 5
      2364979.24      7085429.87      2364848.99      7085628.88
      2364352.25      7085633.41      2364214.41      7085635.05
      2364111.17      7085935.56
#Sta/Elev= 30
  4265.4  714.13  4315.4  711.48  4360.7  707.87  4366.7  709.34  4387.8  708.49
  4432.9  704.69  4475.3  704.78  4496.3  704.13  4500.9  701.84  4513.2  701.36
  4713.2  699.46  4923.2  695.31  4963.3  695.02  4983.3  693.32  4997.1  693.19
  4997.4  692.69  5000.9  692.69  5001.1  693.19  5023.3  694.87  5053.3  695.55
  5130.8  695.39  5143.7  696.02  5164.2  699.56  5169.7  699.71    5201   699.8
  5217.1  698.21  5232.2  697.78  5280.5  699.12  5407.4     701  5455.6  702.44
#Mann= 3 ,-1 , 0
  4265.4     .05       0  4997.1    .033       0  5001.1     .05       0
Bank Sta=4997.1,5001.1
XS Rating Curve= 0 ,0
Exp/Cntr=0.3,0.1

Type RM Length L Ch R = 1 ,6403    ,302,302,302
BEGIN DESCRIPTION:
Graham Branch Tr 12 15.0
END DESCRIPTION:
XS GIS Cut Line= 3
      2364447.76      7085095.91      2364149.09      7085379.42
      2364055.53      7085666.66
#Sta/Elev= 30
  4588.2  718.54  4604.3  717.37  4639.9  713.31  4696.5  709.43  4710.6  707.89
  4781.1  704.58  4788.3  703.57  4851.8  700.98  4880.2  698.64  4908.5  697.66
  4929.9  695.37  4936.8  695.34    4944  693.59  4950.9  692.98  4958.2  690.18
  4991.4  690.17  4991.7  689.67  4995.2  689.67  4995.4  690.17  5002.9   690.2
  5021.7  691.71  5032.2  691.36  5053.6  692.12  5126.8  692.69    5176  692.17
  5181.3  691.57  5207.9  693.51    5277  695.83  5295.1  699.43  5302.1  699.44
#Mann= 3 ,-1 , 0
  4588.2     .05       0  4991.4    .033       0  4995.4     .05       0
Bank Sta=4991.4,4995.4
XS Rating Curve= 0 ,0
Exp/Cntr=0.3,0.1

Type RM Length L Ch R = 1 ,6101    ,102,102,102
BEGIN DESCRIPTION:
Graham Branch Tr 12 14.0
END DESCRIPTION:
XS GIS Cut Line= 4
      2364017.72      7084969.39      2363918.77      7085340.89
      2363890.99      7085460.68      2363875.42      7085665.67
#Sta/Elev= 30
  4492.8  704.99    4543  701.51  4555.5  699.38  4588.3  696.94  4679.7  693.64
  4698.4  693.72  4710.8  693.02  4783.8  691.96  4813.6  692.96  4818.7  692.59
  4834.9  693.72  4858.9  693.94  4874.2  692.16    4895  691.47  4900.2   692.3
  4927.7   691.6  4948.2  691.81  4968.7  691.12  4988.6  689.22  4988.9  688.72
  4992.4  688.72  4992.6  689.22  5049.7   689.5  5059.7  690.84  5093.7  692.15
  5139.9  695.15    5160   695.3  5180.1  696.38  5200.1   699.5  5205.8  699.71
#Mann= 3 ,-1 , 0
  4492.8     .05       0  4988.6    .033       0  4992.6     .05       0
Bank Sta=4988.6,4992.6
XS Rating Curve= 0 ,0
Exp/Cntr=0.3,0.1

Type RM Length L Ch R = 1 ,5999    ,409,409,409
BEGIN DESCRIPTION:
Mapping XS c2ba4f8c
END DESCRIPTION:
XS GIS Cut Line= 6
      2363863.21      7084978.07      2363804.18      7085212.42
      2363817.67      7085318.44      2363812.86      7085399.92
      2363760.78      7085531.86      2363765.99        7085669.
#Sta/Elev= 30
  4535.8  699.21  4539.4  699.21  4548.1  696.61  4558.4  695.57  4589.4  693.89
  4609.6  694.43  4614.8  693.81  4655.9  693.57  4682.2  690.77  4691.8  690.71
    4697  692.07  4702.8  692.51  4732.9  692.82    4744  690.96  4764.7  689.19
  4823.4   687.6  4823.7   687.1  4827.2   687.1  4827.4   687.6  4865.8  689.49
  4905.9  690.37  4943.8  690.09  4963.5  688.02    4977  688.04  5031.5  691.93
  5099.4  693.09  5206.2  696.03  5216.2  696.83  5236.2  699.77  5245.2   700.1
#Mann= 3 ,-1 , 0
  4535.8     .05       0  4823.4    .033       0  4827.4     .05       0
Bank Sta=4823.4,4827.4
XS Rating Curve= 0 ,0
Exp/Cntr=0.3,0.1

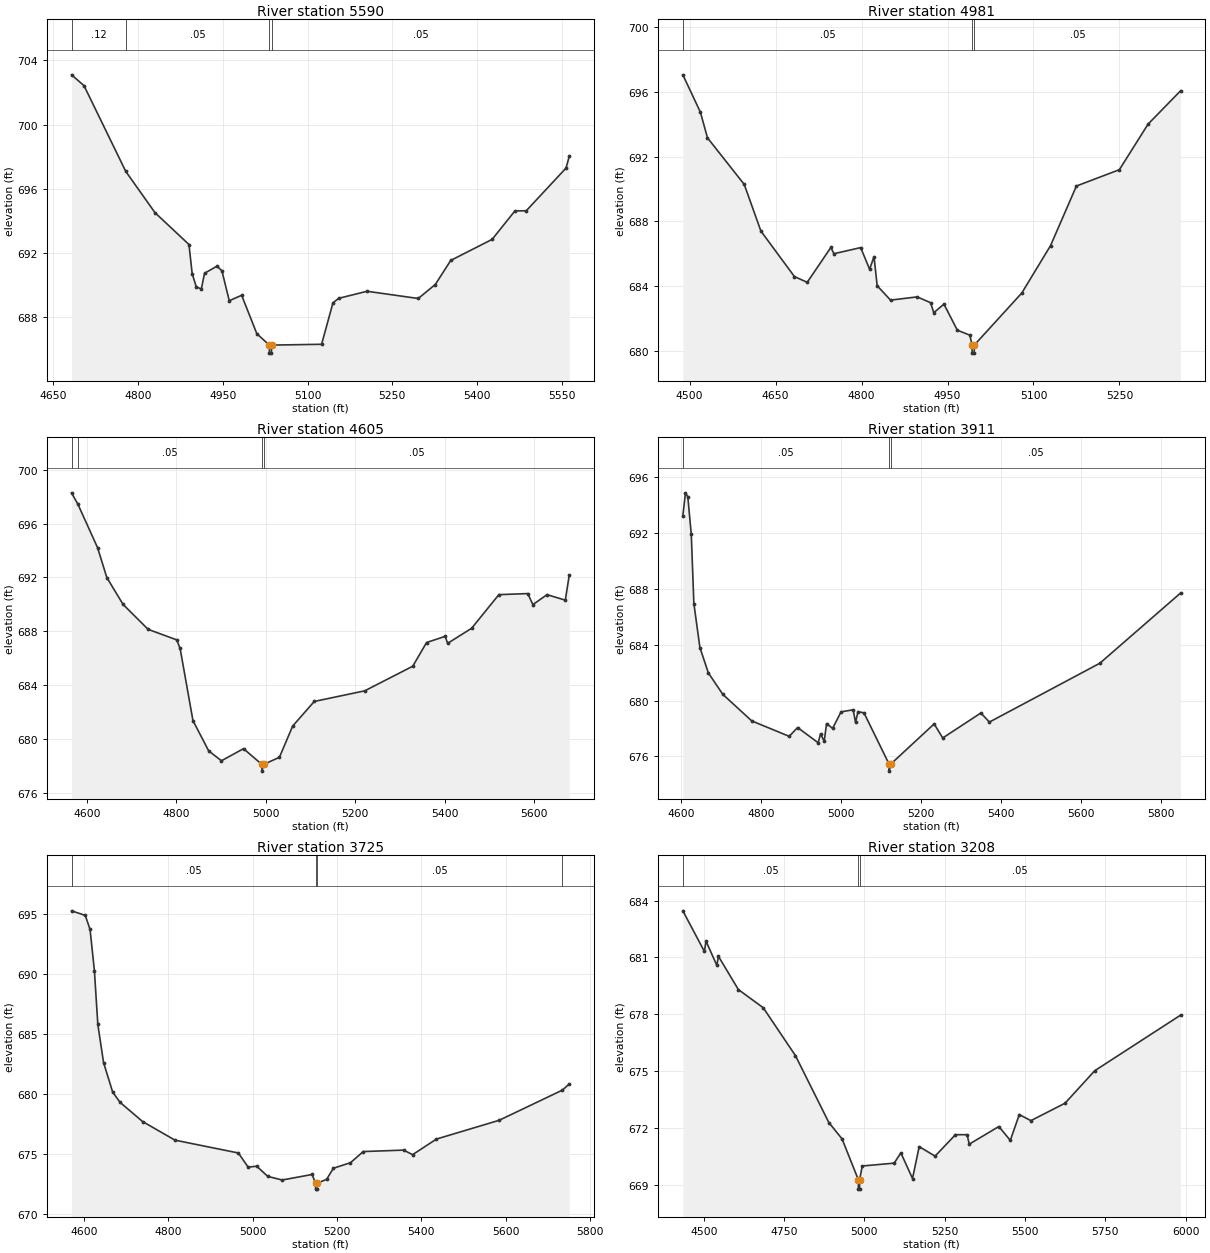
Type RM Length L Ch R = 1 ,5590    ,609,609,609
BEGIN DESCRIPTION:
Graham Branch Tr 12 13.0
END DESCRIPTION:
XS GIS Cut Line= 3
      2363794.36       7084795.5      2363645.79      7085071.91
      2363579.89      7085635.56
#Sta/Elev= 30
    4682   703.1    4704  702.43    4778  697.09  4829.8  694.52  4889.9  692.54
  4895.6  690.73  4902.8  689.91  4911.8  689.77  4917.5  690.75  4939.4  691.19
  4948.2  690.91  4961.3  689.04  4983.2  689.38  5010.1  686.99  5032.2  686.28
  5032.4  685.78  5035.9  685.78  5036.2  686.28  5124.8  686.33  5144.9  688.91
    5155  689.19  5205.3  689.63  5295.9  689.18  5326.1  690.05  5353.5  691.55
  5426.8  692.86  5467.1  694.63  5487.2  694.64  5557.7   697.3  5563.3  698.03
#Mann= 4 ,-1 , 0
    4682     .12       0    4778     .05       0  5032.2    .033       0
  5036.2     .05       0
Bank Sta=5032.2,5036.2
XS Rating Curve= 0 ,0
Exp/Cntr=0.3,0.1

Type RM Length L Ch R = 1 ,4981    ,376,376,376
BEGIN DESCRIPTION:
Graham Branch Tr 12 12.0
END DESCRIPTION:
XS GIS Cut Line= 3
      2363369.76      7084742.04      2363164.89      7085205.59
      2363183.19      7085566.52
#Sta/Elev= 30
  4488.3  697.06  4518.9  694.75  4531.3  693.16  4595.4  690.28  4624.5  687.39
  4682.9  684.58  4705.3  684.22  4746.5  686.38  4751.9  685.99  4798.5  686.37
  4814.1  685.03  4821.8  685.81  4827.3  684.01  4850.6  683.12  4897.2  683.32
  4920.5  682.96    4926  682.34  4943.8  682.87  4967.1  681.26    4989  680.95
  4992.8  680.34    4993  679.84  4996.5  679.84  4996.8  680.34  5079.6  683.56
  5129.7  686.49  5174.9  690.18  5249.8  691.19  5299.9  694.01  5356.5  696.07
#Mann= 3 ,-1 , 0
  4488.3     .05       0  4992.8     .04       0  4996.8     .05       0
Bank Sta=4992.8,4996.8
XS Rating Curve= 0 ,0
Exp/Cntr=0.3,0.1

Type RM Length L Ch R = 1 ,4605    ,694,694,694
BEGIN DESCRIPTION:
Graham Branch Tr 12 11.0
END DESCRIPTION:
XS GIS Cut Line= 3
      2363308.25      7084677.43      2362975.27      7084956.72
       2362721.9      7085586.03
#Sta/Elev= 30
  4565.4  698.29  4579.5  697.45  4623.5  694.22  4644.3  691.99  4680.7  689.99
  4736.7  688.14  4800.5  687.36  4808.2  686.72  4836.9  681.36    4872  679.11
  4900.6  678.37    4950  679.27    4991   678.1  4991.2   677.6    4995   678.1
  5030.3  678.63  5059.9  680.95  5108.2  682.78  5221.1  683.57  5328.5   685.4
  5359.3  687.16    5401  687.62  5406.4   687.1  5460.1  688.22    5521  690.72
  5585.7   690.8  5597.1  689.98  5628.8  690.72  5669.6  690.31  5678.4  692.16
#Mann= 4 ,-1 , 0
  4565.4     .12       0  4579.5     .05       0    4991    .033       0
    4995     .05       0
Bank Sta=4991,4995
XS Rating Curve= 0 ,0
Exp/Cntr=0.3,0.1

Type RM Length L Ch R = 1 ,3911    ,186,186,186
BEGIN DESCRIPTION:
Graham Branch Tr 12 10.0
END DESCRIPTION:
XS GIS Cut Line= 3
      2362976.68       7084359.7      2362590.24      7084610.54
      2362188.87      7085285.27
#Sta/Elev= 30
  4603.5  693.21    4610  694.86  4615.9  694.58  4624.6  691.89  4631.1  686.94
  4646.2  683.79  4667.3  681.98  4703.6  680.44  4776.1  678.54  4869.7  677.44
  4890.8  678.07  4942.2  676.98  4948.1  677.61  4957.3  677.09  4963.3  678.35
  4978.4  678.01  4999.5  679.19  5029.8  679.34  5035.8  678.44  5041.9   679.2
  5056.9  679.12  5119.8  675.45    5120  674.95  5123.8  675.45  5232.6  678.33
    5254  677.32  5349.5  679.11  5370.9  678.46  5647.4  682.67  5849.3  687.69
#Mann= 3 ,-1 , 0
  4603.5     .05       0  5119.8    .033       0  5123.8     .05       0
Bank Sta=5119.8,5123.8
XS Rating Curve= 0 ,0
Exp/Cntr=0.3,0.1

Type RM Length L Ch R = 1 ,3725    ,517,517,517
BEGIN DESCRIPTION:
Graham Branch Tr 12 9.0
END DESCRIPTION:
XS GIS Cut Line= 4
      2362979.03      7084259.99      2362643.62      7084400.03
      2362307.69      7084449.51      2361973.63      7084789.82
#Sta/Elev= 30
  4570.8  695.24  4603.3  694.86  4614.7  693.69    4625  690.25  4633.1  685.78
  4646.7   682.6  4668.4  680.13  4686.1  679.28  4739.2  677.69    4816  676.14
  4966.3  675.07  4989.5  673.89  5009.7  673.97    5036  673.12  5070.3  672.82
  5141.1  673.28  5149.2  672.56  5149.5  672.06    5153  672.06  5153.2  672.56
  5175.4  672.87  5191.6   673.8  5232.1  674.26  5262.4  675.19  5358.2  675.31
  5379.3  674.93  5435.9  676.23  5584.3  677.79  5734.7  680.31  5750.7  680.82
#Mann= 4 ,-1 , 0
  4570.8     .05       0  5149.2     .04       0  5153.2     .05       0
  5734.7    .075       0
Bank Sta=5149.2,5153.2
XS Rating Curve= 0 ,0
Exp/Cntr=0.3,0.1

Type RM Length L Ch R = 1 ,3208    ,445,445,445
BEGIN DESCRIPTION:
Graham Branch Tr 12 8.0
END DESCRIPTION:
XS GIS Cut Line= 3
      2363195.45      7083775.49      2362652.99      7083933.11
      2361907.88      7084576.27
#Sta/Elev= 30
  4435.1  683.46  4502.1  681.32  4507.3  681.86  4540.8  680.59    4546  681.06
  4607.9  679.31  4685.4  678.35  4785.5  675.83  4889.6   672.3  4930.6  671.44
  4981.3  669.29  4981.6  668.79  4985.1  668.79  4985.3  669.29  4993.7  670.01
  5092.9  670.16  5113.8   670.7    5150  669.35  5170.8  671.03  5220.2  670.53
  5283.8  671.66    5320  671.66  5326.6  671.16  5418.7  672.09  5454.4  671.36
  5482.4  672.72  5518.5   672.4  5624.9  673.32  5717.1  675.03  5984.3  677.96
#Mann= 3 ,-1 , 0
  4435.1     .05       0  4981.3     .04       0  4985.3     .05       0
Bank Sta=4981.3,4985.3
XS Rating Curve= 0 ,0
Exp/Cntr=0.3,0.1

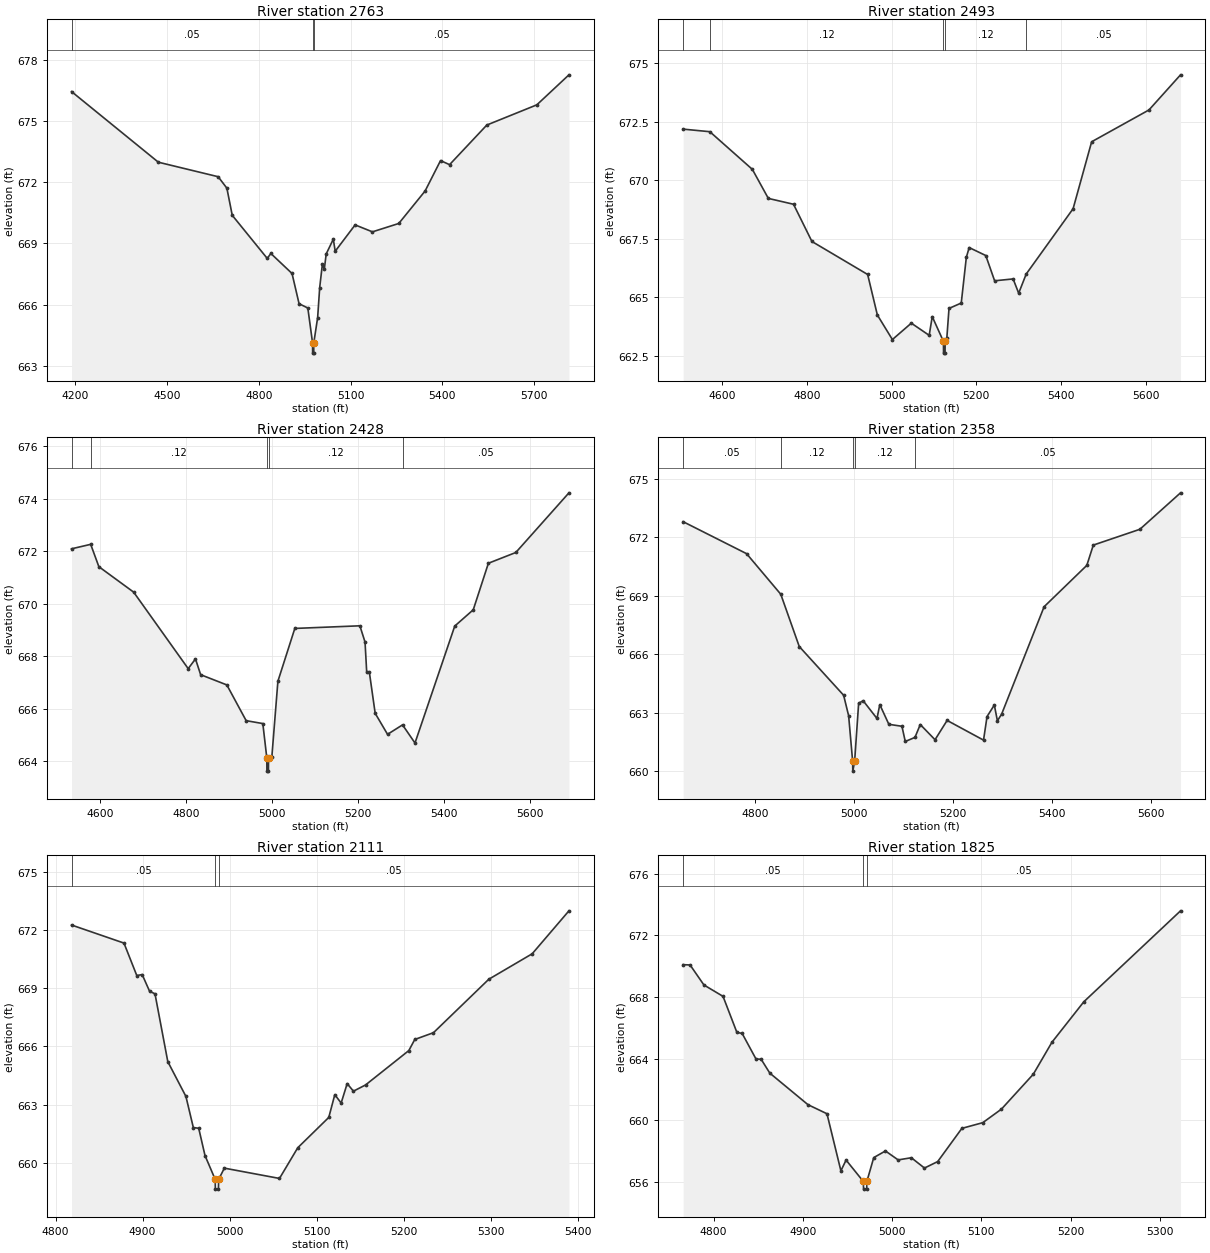
Type RM Length L Ch R = 1 ,2763    ,270,270,270
BEGIN DESCRIPTION:
Graham Branch Tr 12 7.0
END DESCRIPTION:
XS GIS Cut Line= 3
      2363001.04      7083456.77      2362261.94      7083793.51
      2361790.18      7084456.37
#Sta/Elev= 30
  4187.8  676.44  4471.6  672.98    4667  672.27  4695.5  671.71  4713.1  670.38
  4827.4  668.27  4839.3  668.51  4908.5  667.53  4931.5  666.05  4960.1  665.84
  4975.6  664.13  4975.9  663.63  4979.4  663.63  4979.6  664.13  4992.2  665.37
  4998.9  666.84  5007.8     668  5013.9  667.73  5020.2  668.49  5043.4  669.21
  5049.6  668.62  5114.7  669.91  5171.3  669.57  5257.4  669.98  5343.4  671.57
  5393.9  673.06  5423.4  672.86  5545.1   674.8  5708.6  675.79  5813.6  677.26
#Mann= 3 ,-1 , 0
  4187.8     .05       0  4975.6    .033       0  4979.6     .05       0
Bank Sta=4975.6,4979.6
XS Rating Curve= 0 ,0
Exp/Cntr=0.3,0.1

Type RM Length L Ch R = 1 ,2493    ,65,65,65
BEGIN DESCRIPTION:
Mapping XS 5ada62ae
END DESCRIPTION:
XS GIS Cut Line= 6
      2362609.73      7083327.14       2362193.1      7083558.89
      2362154.04      7083579.72      2362114.98       7083626.6
      2362088.94      7083717.74      2361789.93      7084115.55
#Sta/Elev= 30
  4507.7  672.18  4570.8  672.07  4671.2  670.46  4708.9  669.22  4768.4  668.97
  4811.8  667.38  4943.4  665.97  4966.3  664.24  5001.8  663.19  5046.5  663.89
  5088.7  663.37  5095.9  664.17  5122.4  663.11  5122.6  662.61  5126.1  662.61
  5126.4  663.11  5130.3  663.24  5135.5  664.52  5164.4  664.75  5176.4   666.7
  5183.1  667.12  5222.3  666.78  5243.2   665.7  5286.9  665.78    5300  665.17
  5317.8  665.99  5428.5  668.78  5472.3  671.64  5607.7     673  5682.2   674.5
#Mann= 5 ,-1 , 0
  4507.7     .05       0  4570.8     .12       0  5122.4     .07       0
  5126.4     .12       0  5317.8     .05       0
Bank Sta=5122.4,5126.4
XS Rating Curve= 0 ,0
Exp/Cntr=0.3,0.1

Type RM Length L Ch R = 1 ,2428    ,70,70,70
BEGIN DESCRIPTION:
Mapping XS 19bef7ee
END DESCRIPTION:
XS GIS Cut Line= 6
      2362588.92      7083295.88      2362174.87      7083498.99
        2362128.      7083540.66      2362078.52      7083605.76
      2362062.89      7083686.49      2361766.04      7084051.05
#Sta/Elev= 30
  4533.3  672.09  4577.9  672.26  4596.9  671.41    4678  670.44  4804.9  667.53
  4821.9   667.9  4833.9   667.3  4894.9  666.91  4939.9  665.55  4978.7  665.44
    4988  664.13  4988.2  663.63  4991.7  663.63    4992  664.13  4999.6  664.15
  5013.8  667.05  5053.2  669.06  5204.7  669.16  5216.7  668.54  5220.6  667.39
  5226.8  667.39  5240.3  665.83  5269.1  665.03    5304  665.39    5333   664.7
  5425.6  669.15  5468.7  669.77  5503.9  671.54  5567.8  671.95  5691.5  674.22
#Mann= 5 ,-1 , 0
  4533.3     .05       0  4577.9     .12       0    4988     .07       0
    4992     .12       0    5304     .05       0
Bank Sta=4988,4992
XS Rating Curve= 0 ,0
Exp/Cntr=0.3,0.1

Type RM Length L Ch R = 1 ,2358    ,247,247,247
BEGIN DESCRIPTION:
Mapping XS 17afee65
END DESCRIPTION:
XS GIS Cut Line= 6
      2362260.42      7083148.73      2362121.92      7083426.11
      2362114.28      7083483.06      2362039.98      7083542.08
      2362002.48      7083637.22      2361747.79      7083993.79
#Sta/Elev= 30
  4655.4   672.8  4783.5  671.16  4852.5  669.08  4889.8   666.4  4979.4   663.9
  4989.5  662.85  4997.6  660.51  4997.9  660.01  5001.6  660.51  5009.7  663.49
  5018.8  663.62  5046.7  662.71  5052.4  663.42  5070.7  662.41  5097.1  662.31
  5103.8  661.53  5123.4  661.74  5134.1   662.4  5163.9  661.62  5188.3  662.61
  5261.8   661.6  5268.9  662.81  5283.6   663.4  5289.8  662.59  5298.3  662.93
  5384.1  668.44  5470.3  670.56  5483.4   671.6  5577.4  672.41  5659.5  674.28
#Mann= 5 ,-1 , 0
  4655.4     .05       0  4852.5     .12       0  4997.6     .07       0
  5001.6     .12       0  5123.4     .05       0
Bank Sta=4997.6,5001.6
XS Rating Curve= 0 ,0
Exp/Cntr=0.3,0.1

Type RM Length L Ch R = 1 ,2111    ,286,286,286
BEGIN DESCRIPTION:
Graham Branch Tr 12 5.0
END DESCRIPTION:
XS GIS Cut Line= 3
      2362019.25      7083296.08      2361912.49      7083442.98
      2361629.03      7083709.97
#Sta/Elev= 30
  4818.4  672.25  4878.6  671.32  4893.3  669.65  4899.5   669.7    4908  668.84
  4914.2  668.71  4928.9  665.22  4949.7  663.43  4958.2  661.83  4964.4  661.79
  4971.6  660.39  4983.3  659.16  4983.5  658.66    4987  658.66  4987.3  659.16
  4993.8  659.74  5057.1  659.21  5078.1  660.79  5113.7  662.35  5120.6  663.52
  5127.9  663.09  5134.8  664.09    5142   663.7  5155.9  664.02  5205.6  665.79
  5212.4  666.36  5233.9  666.71  5297.4  669.46  5347.2  670.77  5389.4  672.98
#Mann= 3 ,-1 , 0
  4818.4     .05       0  4983.3    .033       0  4987.3     .05       0
Bank Sta=4983.3,4987.3
XS Rating Curve= 0 ,0
Exp/Cntr=0.3,0.1

Type RM Length L Ch R = 1 ,1825    ,470,470,470
BEGIN DESCRIPTION:
Graham Branch Tr 12 4.0
END DESCRIPTION:
XS GIS Cut Line= 3
      2361892.97      7083202.32      2361692.59      7083323.35
      2361428.99      7083510.01
#Sta/Elev= 30
  4765.9   670.1  4773.7  670.08  4789.2  668.78  4810.6  668.04  4826.1   665.7
    4832  665.63  4847.5  663.97  4853.3  663.95    4863  663.05  4905.7     661
    4927  660.41  4942.6   656.7  4948.4   657.4  4967.7  656.01    4968  655.51
  4971.5  655.51  4971.7  656.01  4979.4  657.56  4992.5  657.99  5006.7  657.41
  5021.5  657.55  5036.2  656.88    5051   657.3  5078.1  659.46  5101.5  659.83
  5122.4  660.71  5158.1  662.98    5179  665.06  5214.7  667.69    5323   673.6
#Mann= 3 ,-1 , 0
  4765.9     .05       0  4967.7    .033       0  4971.7     .05       0
Bank Sta=4967.7,4971.7
XS Rating Curve= 0 ,0
Exp/Cntr=0.3,0.1