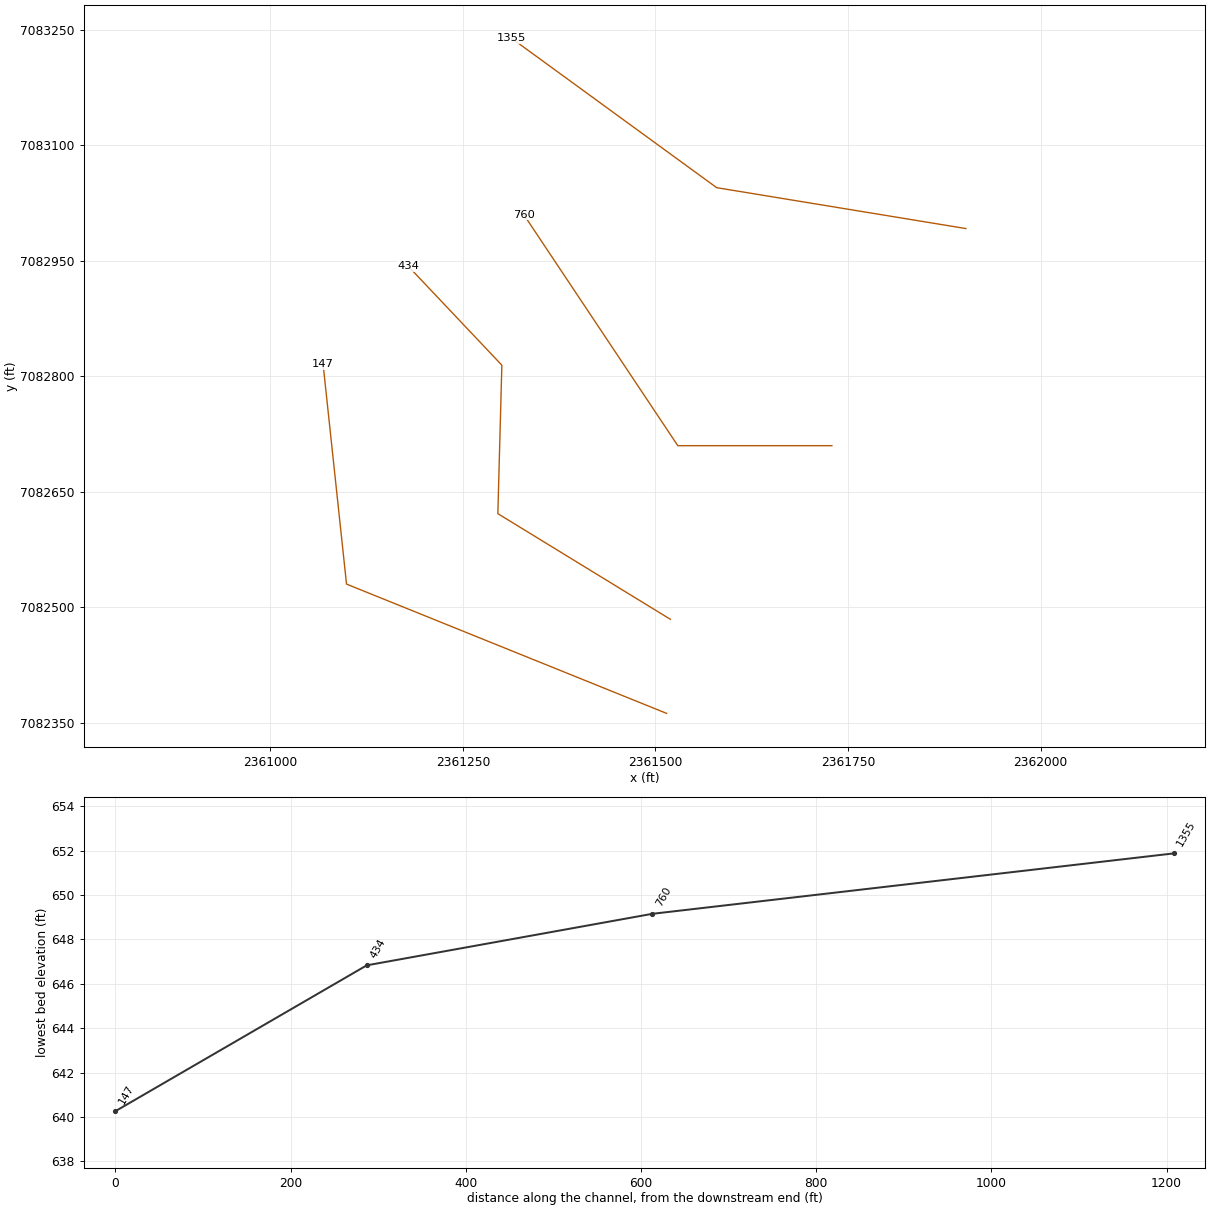
HEC-RAS study Graham Branch Tr 12.prj: Graham Branch Tr 12 Base Level Engineering

--- Graham Branch Tr 12.g01 (geometry) --- (continued)

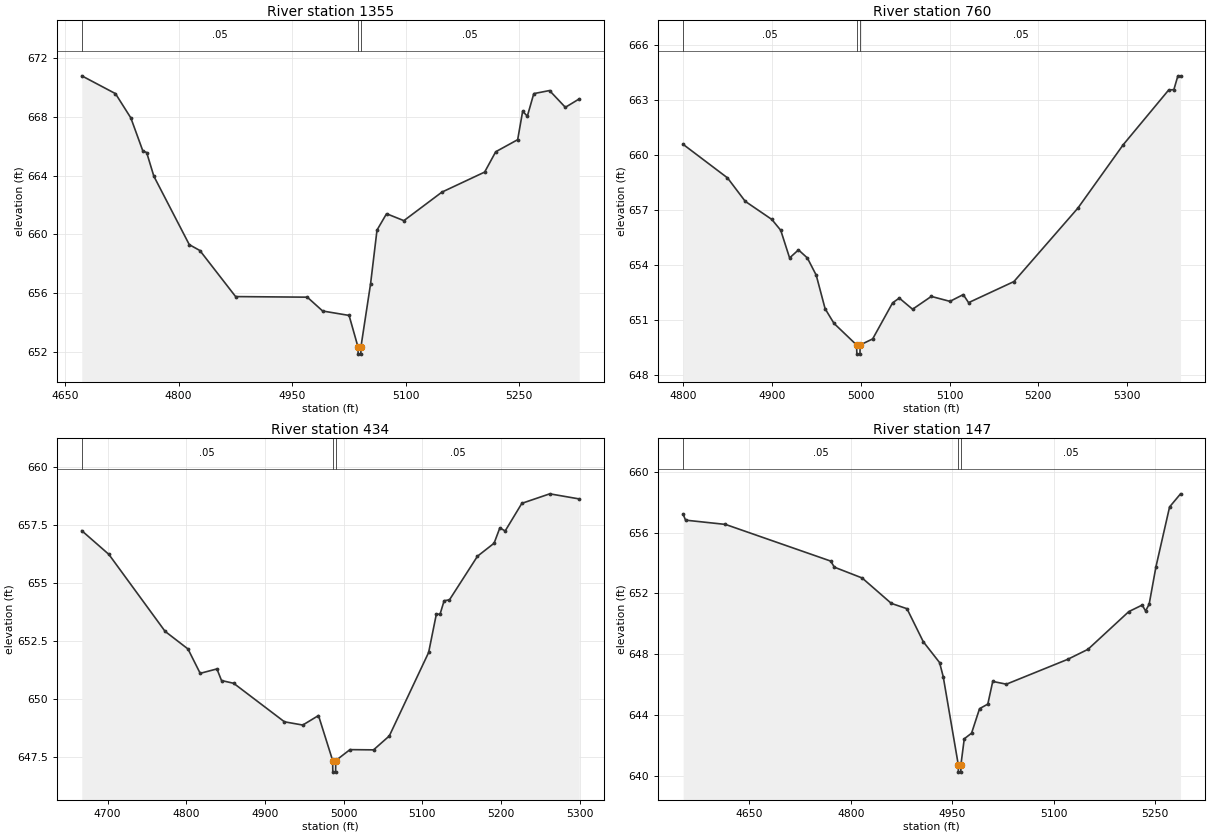
Type RM Length L Ch R = 1 ,1355    ,595,595,595
BEGIN DESCRIPTION:
Graham Branch Tr 12 3.0
END DESCRIPTION:
XS GIS Cut Line= 3
      2361902.96      7082991.83      2361579.48       7083044.9
      2361313.29      7083238.76
#Sta/Elev= 30
  4672.2  670.78  4716.7  669.57    4737  667.92  4752.9  665.67  4757.9  665.57
  4767.4  663.96  4814.2  659.31  4828.2  658.91  4875.4  655.78  4970.1  655.74
  4990.4   654.8  5025.3   654.5    5037  652.37  5037.3  651.87  5040.8  651.87
    5041  652.37  5053.7  656.65  5062.2   660.3  5074.8  661.41  5097.7  660.94
    5148  662.88  5204.4  664.24    5219  665.62    5248  666.44  5254.6  668.37
  5260.8  668.04  5269.3  669.57  5290.1  669.78    5311  668.64  5329.3  669.21
#Mann= 3 ,-1 , 0
  4672.2     .05       0    5037     .04       0    5041     .05       0
Bank Sta=5037,5041
XS Rating Curve= 0 ,0
Exp/Cntr=0.3,0.1

Type RM Length L Ch R = 1 ,760     ,326,326,326
BEGIN DESCRIPTION:
Graham Branch Tr 12 2.0
END DESCRIPTION:
XS GIS Cut Line= 3
      2361729.04        7082710.        2361529.        7082710.
        2361329.        7083010.
#Sta/Elev= 30
  4799.7   660.6  4849.7  658.77  4869.7  657.49  4899.7   656.5  4909.7  655.91
  4919.7   654.4  4929.7  654.84  4939.7   654.4  4949.7  653.46  4959.7  651.63
  4969.7  650.83  4995.2  649.65  4995.5  649.15    4999  649.15  4999.2  649.65
  5013.3  649.98  5035.8  651.95  5043.3  652.21  5058.3   651.6  5079.4   652.3
  5100.4  652.03  5115.4   652.4  5121.4  651.96  5172.5  653.11  5244.6  657.12
  5295.7  660.58  5346.8  663.56  5352.8  663.59  5357.3  664.34  5360.3  664.34
#Mann= 3 ,-1 , 0
  4799.7     .05       0  4995.2    .033       0  4999.2     .05       0
Bank Sta=4995.2,4999.2
XS Rating Curve= 0 ,0
Exp/Cntr=0.3,0.1

Type RM Length L Ch R = 1 ,434     ,287,287,287
BEGIN DESCRIPTION:
Mapping XS c791f926
END DESCRIPTION:
XS GIS Cut Line= 4
      2361519.35      7082484.61      2361295.39      7082621.77
       2361300.6      7082814.48      2361179.03      7082942.99
#Sta/Elev= 30
  4667.3  657.24  4701.7  656.22  4773.2   652.9  4802.3  652.14  4817.8  651.09
  4839.1  651.28  4844.9  650.78  4860.4  650.66  4924.9     649  4948.2  648.86
  4968.2  649.27  4986.2  647.33  4986.4  646.83  4989.9  646.83  4990.2  647.33
  5008.2   647.8  5038.2  647.79  5058.2  648.39  5108.2  651.99    5118  653.64
  5122.7  653.64  5127.9  654.22  5134.7  654.26  5170.3  656.14  5191.4   656.7
  5198.7  657.36  5205.5  657.23  5226.7  658.42  5262.2  658.83  5299.6  658.61
#Mann= 3 ,-1 , 0
  4667.3     .05       0  4986.2    .033       0  4990.2     .05       0
Bank Sta=4986.2,4990.2
XS Rating Curve= 0 ,0
Exp/Cntr=0.3,0.1

Type RM Length L Ch R = 1 ,147     ,0,0,0
BEGIN DESCRIPTION:
Graham Branch Tr 12 1.0
END DESCRIPTION:
XS GIS Cut Line= 3
      2361514.45       7082362.5      2361098.96      7082530.31
       2361068.5      7082816.09
#Sta/Elev= 30
  4551.9  657.21  4555.5  656.82  4614.5  656.54  4770.1  654.13  4775.5  653.73
  4816.6  653.02  4859.7  651.35  4882.9     651    4907  648.83  4931.1  647.46
  4936.5  646.53  4958.7  640.76  4958.9  640.26  4962.4  640.26  4962.7  640.76
  4967.6  642.45  4978.4  642.82  4990.2  644.43  5002.4  644.73  5009.7  646.22
  5029.9  646.04  5120.4  647.67  5150.5  648.33  5210.9  650.81  5230.7  651.24
  5235.7  650.85    5241   651.3  5251.1  653.77  5271.2  657.69  5287.4  658.55
#Mann= 3 ,-1 , 0
  4551.9     .05       0  4958.7    .033       0  4962.7     .05       0
Bank Sta=4958.7,4962.7
XS Rating Curve= 0 ,0
Exp/Cntr=0.3,0.1

Chan Stop Cuts=-1
Use User Specified Reach Order=0
Composite Channel Slope=5