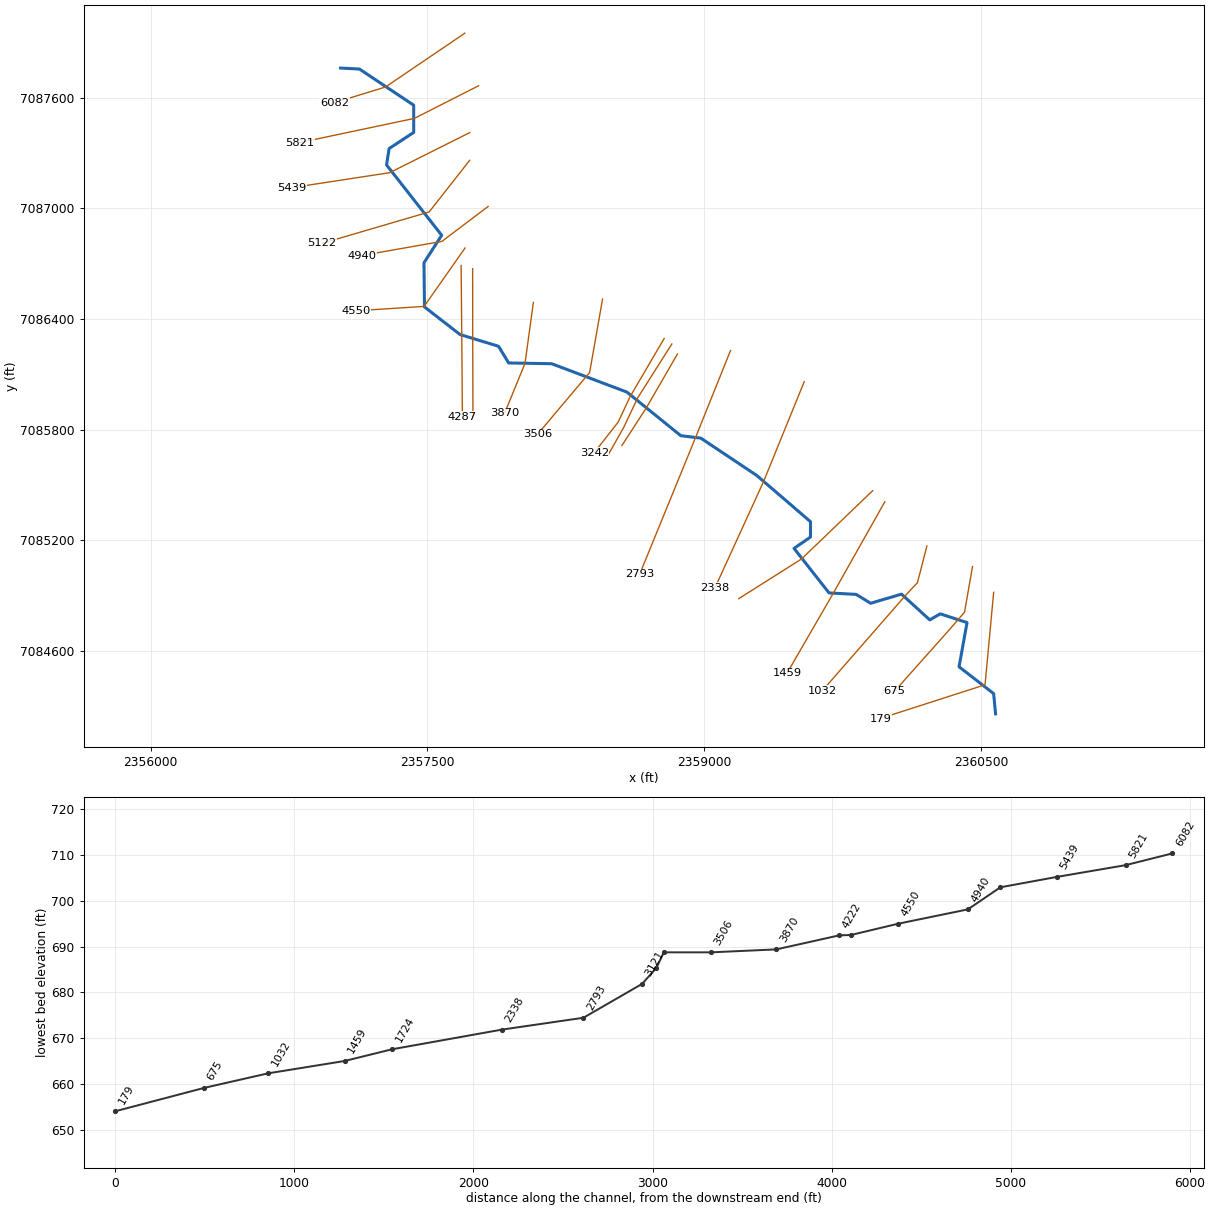
--- Graham Branch Tr 13.prj (project) ---

Proj Title=Graham Branch Tr 13 Base Level Engineering
Current Plan=p01
Default Exp/Contr=0.3,0.1
English Units
Geom File=g01
Flow File=f01
Plan File=p01
BEGIN DESCRIPTION:
Graham Branch Tr 13
END DESCRIPTION:

--- Graham Branch Tr 13.p01 (plan) ---

Plan Title=Multiple Run
Short Identifier=Multiple
Geom File=g01
Flow File=f01
Subcritical Flow
K Sum by GR= 0
Std Step Tol= 0.01
Critical Tol= 0.01
Num of Std Step Trials= 20
Max Error Tol= 0.3
Flow Tol Ratio= 0.001
Split Flow NTrial= 30
Split Flow Tol= 0.02
Split Flow Ratio= 0.02
Log Output Level= 0
Friction Slope Method= 1
Unsteady Friction Slope Method= 2
Unsteady Bridges Friction Slope Method= 1
Parabolic Critical Depth
Global Vel Dist=  1 , 1 , 1
Global Log Level= 0
CheckData=True
Encroach Param= -1, 0, 0, 0
BEGIN DESCRIPTION:
Multiple Run
END DESCRIPTION:

--- Graham Branch Tr 13.f01 (steady flow) ---

Flow Title=Multiple
Number of Profiles=7
Profile Names=10-year,25-year,50-year,1pct_min,100-year,1pct_plu,500-year
River Rch & RM= Graham Branch Tr,Reach-1,6082
     352     465     554     329     656    1310     921
River Rch & RM= Graham Branch Tr,Reach-1,4222
     515     696     842     507    1011    2018    1460
Boundary for River Rch & Prof#=Graham Branch Tr,Reach-1,1
Up Type=0
Dn Type=3
Dn Slope=0.005
Boundary for River Rch & Prof#=Graham Branch Tr,Reach-1,2
Up Type=0
Dn Type=3
Dn Slope=0.005
Boundary for River Rch & Prof#=Graham Branch Tr,Reach-1,3
Up Type=0
Dn Type=3
Dn Slope=0.005
Boundary for River Rch & Prof#=Graham Branch Tr,Reach-1,4
Up Type=0
Dn Type=3
Dn Slope=0.005
Boundary for River Rch & Prof#=Graham Branch Tr,Reach-1,5
Up Type=0
Dn Type=3
Dn Slope=0.005
Boundary for River Rch & Prof#=Graham Branch Tr,Reach-1,6
Up Type=0
Dn Type=3
Dn Slope=0.005
Boundary for River Rch & Prof#=Graham Branch Tr,Reach-1,7
Up Type=0
Dn Type=3
Dn Slope=0.005

--- Graham Branch Tr 13.g01 (geometry) ---

Geom Title=Existing Conditions

River Reach=Graham Branch Tr,Reach-1
Reach XY= 30
      2357029.00      7087760.00      2357131.49      7087754.64
      2357425.56      7087558.75      2357425.56      7087411.25
      2357292.19      7087323.65      2357278.46      7087234.89
      2357577.24      7086853.88      2357481.18      7086704.55
      2357484.18      7086465.44      2357676.70      7086315.83
      2357885.43      7086252.21      2357940.15      7086161.87
      2358173.47      7086157.62      2358581.23      7086003.93
      2358872.83      7085767.86      2358981.42      7085754.46
      2359285.05      7085551.84      2359576.06      7085301.57
      2359575.85      7085218.14      2359486.78      7085156.94
      2359676.55      7084915.47      2359823.07      7084907.70
      2359901.81      7084859.62      2360069.37      7084908.91
      2360222.33      7084769.30      2360278.90      7084802.20
      2360424.38      7084754.76      2360381.08      7084515.26
      2360568.58      7084369.84      2360579.00      7084260.00

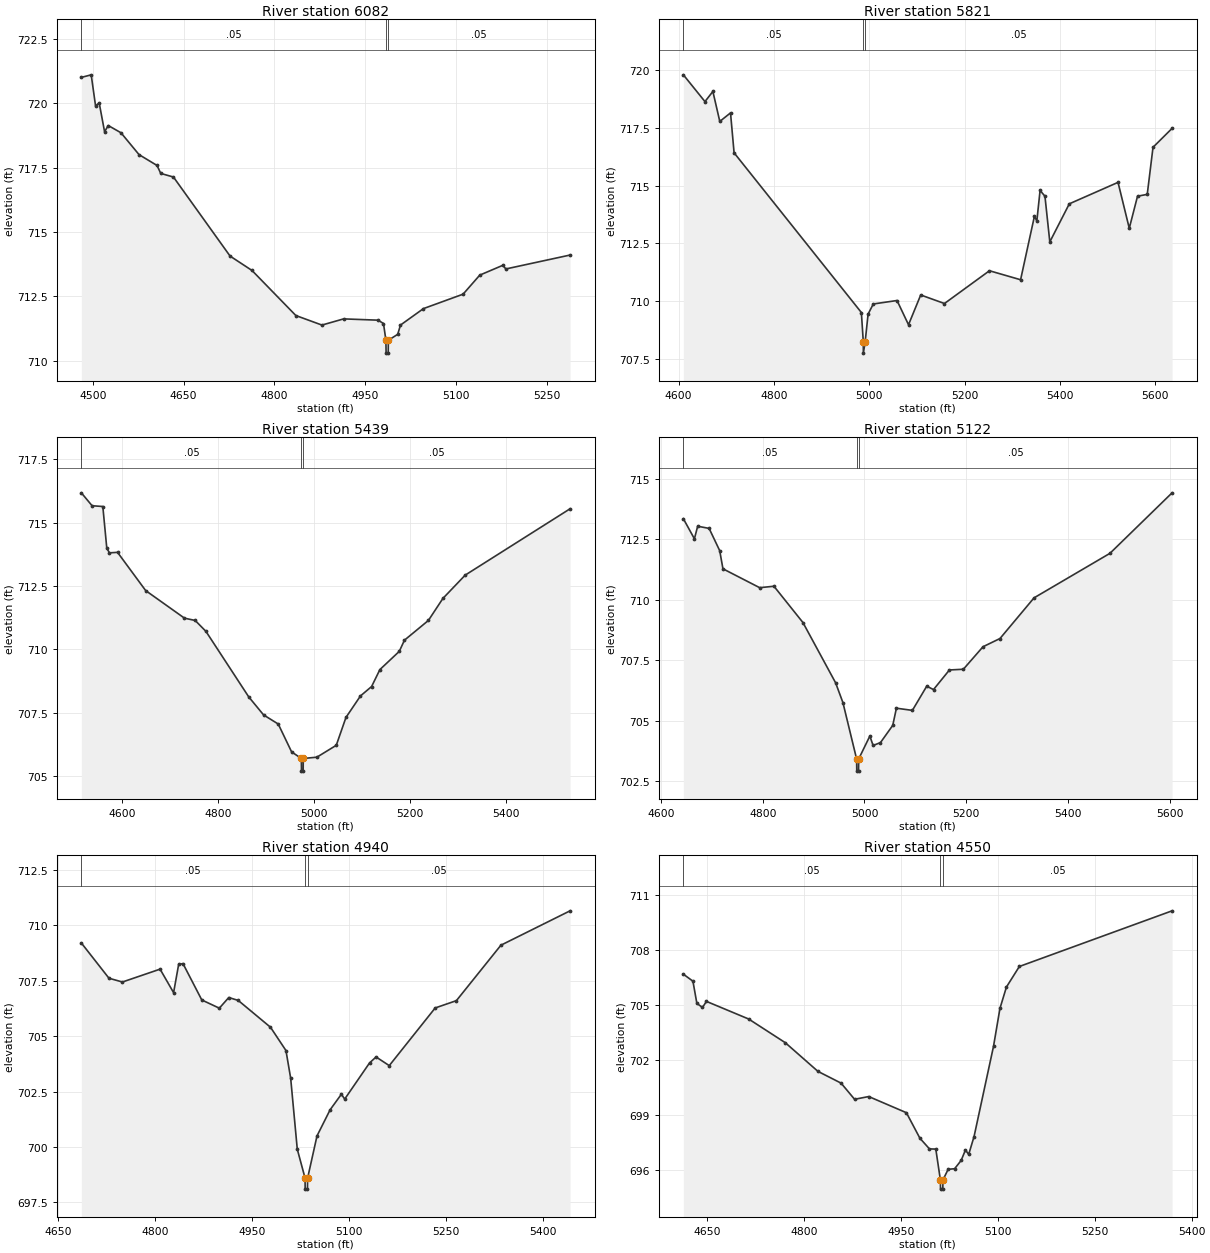
Type RM Length L Ch R = 1,6082,261,261,261
BEGIN DESCRIPTION:
Graham Branch Tr 13 16.0
END DESCRIPTION:
XS GIS Cut Line= 3
      2357702.48      7087948.85      2357272.88      7087657.29
      2356996.65      7087572.65
#Sta/Elev= 30
  4480.8  721.01  4497.1  721.11  4504.3  719.90  4510.3  720.02  4519.2  718.90
  4525.3  719.14  4546.3  718.86  4576.2  718.01  4605.9  717.59  4612.1  717.28
  4633.1  717.14  4726.7  714.07  4763.0  713.51  4835.5  711.76  4878.6  711.39
  4914.5  711.63  4971.5  711.58  4980.4  711.45  4984.4  710.80  4984.7  710.30
  4988.2  710.30  4988.4  710.80  5003.9  711.03  5008.5  711.39  5046.5  712.03
  5112.0  712.59  5139.6  713.33  5177.6  713.71  5182.8  713.57  5288.9  714.11
#Mann=3,-1,0
  4480.8    0.05       0  4984.4    0.04       0  4988.4    0.05       0
Bank Sta=4984.4,4988.4
Exp/Cntr=0.3,0.1

Type RM Length L Ch R = 1,5821,382,382,382
BEGIN DESCRIPTION:
Graham Branch Tr 13 15.0
END DESCRIPTION:
XS GIS Cut Line= 3
      2357777.14      7087664.14      2357429.43      7087487.29
      2356808.04      7087356.06
#Sta/Elev= 30
  4609.9  719.80  4655.2  718.64  4671.8  719.08  4686.3  717.78  4708.8  718.15
  4716.3  716.42  4983.3  709.50  4987.3  708.24  4987.5  707.74  4991.3  708.24
  4997.4  709.43  5008.3  709.87  5058.1  710.02  5082.2  708.97  5107.8  710.26
  5157.6  709.89  5252.0  711.31  5317.3  710.92  5346.3  713.67  5351.4  713.47
  5358.2  714.79  5368.4  714.54  5378.6  712.56  5419.5  714.21  5521.7  715.14
  5545.3  713.15  5562.6  714.54  5583.0  714.62  5595.1  716.66  5635.1  717.48
#Mann=3,-1,0
  4609.9    0.05       0  4987.3    0.04       0  4991.3    0.05       0
Bank Sta=4987.3,4991.3
Exp/Cntr=0.3,0.1

Type RM Length L Ch R = 1,5439,317,317,317
BEGIN DESCRIPTION:
Graham Branch Tr 13 14.0
END DESCRIPTION:
XS GIS Cut Line= 3
      2357729.02      7087410.01      2357295.33      7087192.91
      2356766.77      7087112.07
#Sta/Elev= 30
  4515.0  716.18  4537.4  715.67  4559.8  715.64  4568.1  713.99  4573.7  713.81
  4590.5  713.83  4649.2  712.32  4730.2  711.23  4752.5  711.14  4774.9  710.71
  4864.3  708.12  4895.2  707.41  4925.8  707.05  4953.7  705.95  4974.0  705.69
  4974.3  705.19  4977.8  705.19  4978.0  705.69  5006.4  705.74  5046.9  706.21
  5067.1  707.31  5097.4  708.16  5120.6  708.53  5137.9  709.20  5178.4  709.92
  5189.1  710.36  5239.1  711.14  5269.4  712.01  5315.9  712.93  5534.7  715.55
#Mann=3,-1,0
  4515.0    0.05       0  4974.0    0.04       0  4978.0    0.05       0
Bank Sta=4974,4978
Exp/Cntr=0.3,0.1

Type RM Length L Ch R = 1,5122,182,182,182
BEGIN DESCRIPTION:
Graham Branch Tr 13 13.0
END DESCRIPTION:
XS GIS Cut Line= 3
      2357729.01      7087260.01      2357509.22      7086980.09
      2356929.03      7086810.01
#Sta/Elev= 30
  4644.1  713.35  4665.8  712.52  4672.2  713.04  4694.7  712.95  4715.5  712.03
  4721.9  711.28  4794.1  710.50  4822.1  710.56  4879.1  709.06  4943.3  706.57
  4957.7  705.75  4984.6  703.42  4984.9  702.92  4988.4  702.92  4988.6  703.42
  5010.6  704.37  5017.0  703.98  5031.5  704.10  5055.6  704.81  5062.8  705.52
  5094.2  705.43  5122.4  706.43  5135.7  706.29  5167.0  707.10  5194.4  707.13
  5233.0  708.06  5266.4  708.40  5333.3  710.08  5482.5  711.92  5604.6  714.42
#Mann=3,-1,0
  4644.1    0.05       0  4984.6    0.04       0  4988.6    0.05       0
Bank Sta=4984.6,4988.6
Exp/Cntr=0.3,0.1

Type RM Length L Ch R = 1,4940,390,390,390
BEGIN DESCRIPTION:
Graham Branch Tr 13 12.0
END DESCRIPTION:
XS GIS Cut Line= 3
      2357828.99      7087010.00      2357578.40      7086820.63
      2357143.69      7086744.04
#Sta/Elev= 30
  4685.9  709.20  4728.6  707.61  4749.4  707.44  4807.6  708.02  4828.5  706.96
  4836.3  708.23  4843.0  708.27  4872.1  706.63  4899.2  706.26  4913.8  706.74
  4928.4  706.61  4978.3  705.40  5002.2  704.35  5009.5  703.10  5019.7  699.90
  5031.7  698.60  5031.9  698.10  5035.4  698.10  5035.7  698.60  5050.2  700.50
  5070.5  701.68  5087.9  702.38  5093.0  702.16  5131.4  703.79  5141.5  704.06
  5161.9  703.67  5232.9  706.27  5265.7  706.60  5334.5  709.10  5441.4  710.65
#Mann=3,-1,0
  4685.9    0.05       0  5031.7    0.04       0  5035.7    0.05       0
Bank Sta=5031.7,5035.7
Exp/Cntr=0.3,0.1

Type RM Length L Ch R = 1,4550,263,263,263
BEGIN DESCRIPTION:
Graham Branch Tr 13 11.0
END DESCRIPTION:
XS GIS Cut Line= 3
      2357703.99      7086784.99      2357482.07      7086468.30
      2357113.13      7086444.65
#Sta/Elev= 30
  4613.3  706.67  4628.1  706.29  4634.2  705.08  4642.9  704.86  4649.0  705.19
  4714.4  704.23  4771.1  702.94  4821.6  701.38  4857.4  700.74  4878.3  699.86
  4900.2  700.01  4958.5  699.13  4979.4  697.74  4994.2  697.16  5004.0  697.15
  5011.1  695.47  5011.3  694.97  5014.8  694.97  5015.1  695.47  5023.1  696.05
  5033.1  696.08  5043.2  696.53  5049.9  697.10  5054.9  696.86  5063.2  697.83
  5093.3  702.74  5103.3  704.81  5113.3  705.97  5133.3  707.09  5369.7  710.12
#Mann=3,-1,0
  4613.3    0.05       0  5011.1   0.033       0  5015.1    0.05       0
Bank Sta=5011.1,5015.1
Exp/Cntr=0.3,0.1

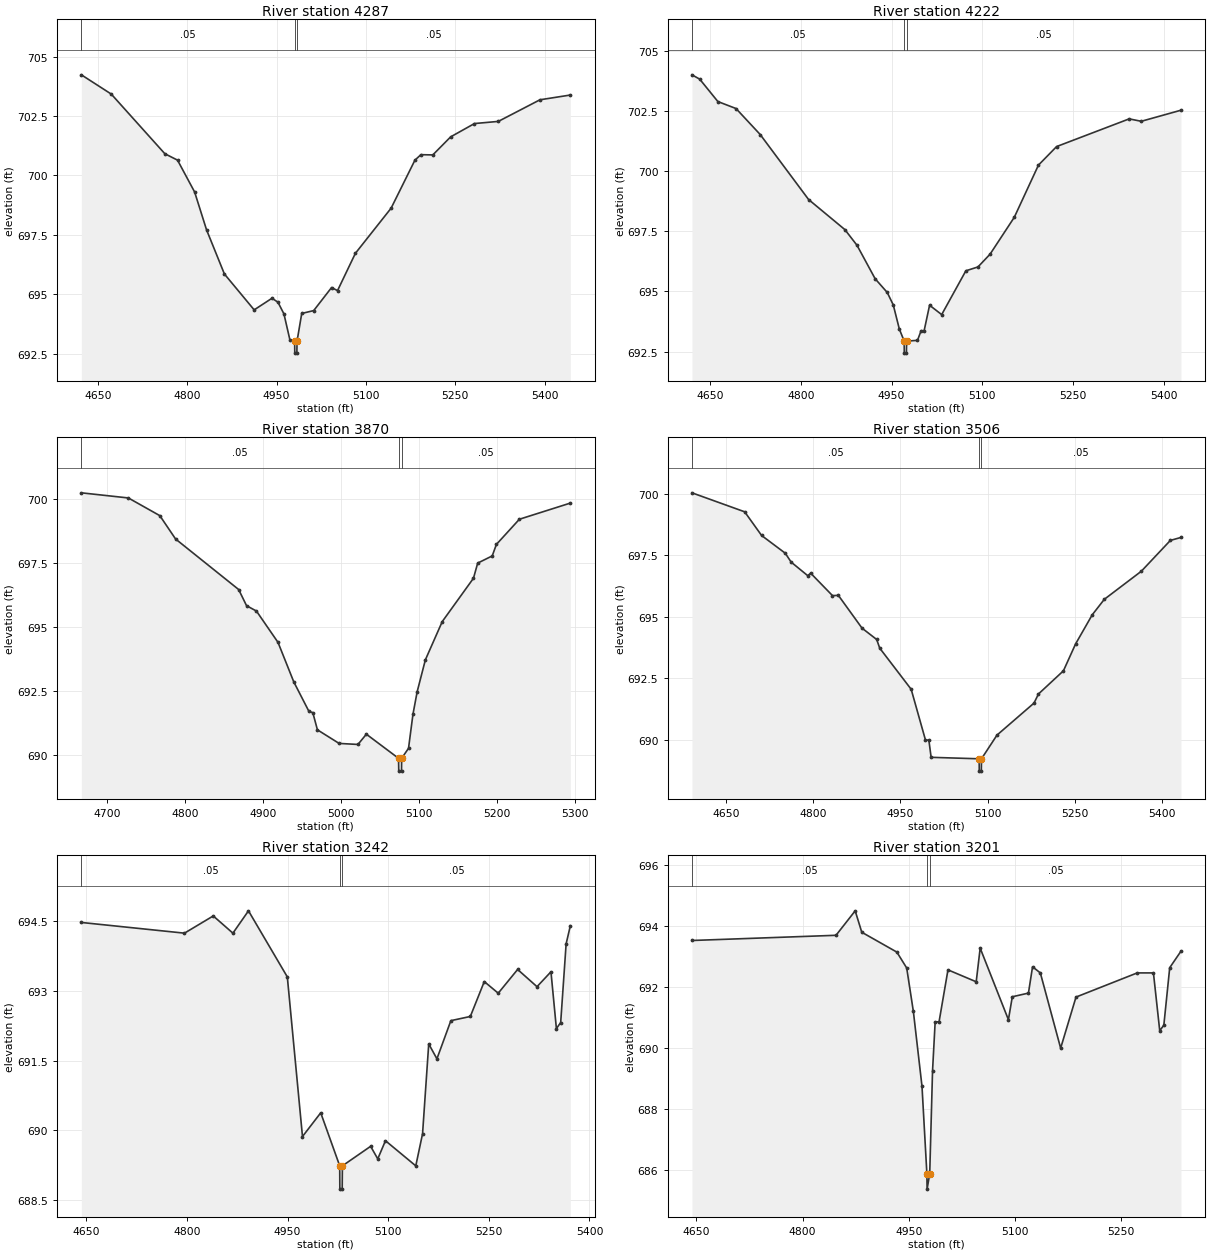
Type RM Length L Ch R = 1,4287,65,65,65
BEGIN DESCRIPTION:
Mapping XS b9e659e6
END DESCRIPTION:
XS GIS Cut Line= 3
      2357682.54      7086690.16      2357686.01      7086315.19
      2357689.48      7085868.99
#Sta/Elev= 30
  4622.1  704.23  4672.3  703.42  4762.3  700.91  4783.6  700.64  4812.3  699.30
  4832.3  697.71  4862.3  695.85  4912.3  694.34  4942.3  694.83  4952.3  694.66
  4962.3  694.17  4972.3  693.08  4980.3  693.02  4980.5  692.52  4984.0  692.52
  4984.3  693.02  4992.2  694.19  5012.3  694.31  5042.3  695.28  5052.3  695.15
  5082.3  696.72  5142.3  698.62  5182.3  700.64  5192.3  700.87  5212.3  700.86
  5242.3  701.62  5282.3  702.18  5322.3  702.27  5392.3  703.18  5443.3  703.38
#Mann=3,-1,0
  4622.1    0.05       0  4980.3    0.04       0  4984.3    0.05       0
Bank Sta=4980.3,4984.3
Exp/Cntr=0.3,0.1

Type RM Length L Ch R = 1,4222,352,352,352
BEGIN DESCRIPTION:
Graham Branch Tr 13 10.0
END DESCRIPTION:
XS GIS Cut Line= 3
      2357745.04      7086672.79      2357745.48      7086292.89
      2357746.77      7085864.40
#Sta/Elev= 30
  4620.1  704.00  4632.9  703.82  4662.9  702.89  4692.9  702.60  4732.9  701.52
  4812.9  698.82  4872.9  697.57  4892.9  696.92  4922.9  695.53  4942.9  694.96
  4952.9  694.44  4962.9  693.44  4970.9  692.94  4971.1  692.44  4974.6  692.44
  4974.9  692.94  4992.9  692.97  4998.9  693.37  5003.9  693.37  5012.9  694.43
  5032.9  694.04  5072.9  695.86  5092.9  696.02  5112.9  696.55  5152.9  698.08
  5192.9  700.25  5222.9  701.02  5342.9  702.17  5362.9  702.07  5428.5  702.53
#Mann=3,-1,0
  4620.1    0.05       0  4970.9    0.04       0  4974.9    0.05       0
Bank Sta=4970.9,4974.9
Exp/Cntr=0.3,0.1

Type RM Length L Ch R = 1,3870,364,364,364
BEGIN DESCRIPTION:
Graham Branch Tr 13 9.0
END DESCRIPTION:
XS GIS Cut Line= 3
      2358074.03      7086489.62      2358029.00      7086160.00
      2357917.80      7085888.15
#Sta/Elev= 30
  4667.2  700.23  4727.4  700.03  4767.7  699.34  4787.9  698.43  4868.7  696.46
  4878.8  695.83  4891.5  695.62  4919.1  694.40  4939.3  692.86  4958.7  691.71
  4963.7  691.66  4969.6  690.99  4997.4  690.46  5021.5  690.42  5032.3  690.82
  5073.5  689.88  5073.8  689.38  5077.3  689.38  5077.5  689.88  5086.3  690.27
  5092.0  691.60  5097.4  692.48  5107.9  693.72  5129.5  695.21  5169.5  696.90
  5174.9  697.49  5193.5  697.77  5198.9  698.22  5228.3  699.20  5293.6  699.83
#Mann=3,-1,0
  4667.2    0.05       0  5073.5   0.033       0  5077.5    0.05       0
Bank Sta=5073.5,5077.5
Exp/Cntr=0.3,0.1

Type RM Length L Ch R = 1,3506,264,264,264
BEGIN DESCRIPTION:
Graham Branch Tr 13 8.0
END DESCRIPTION:
XS GIS Cut Line= 3
      2358449.04      7086507.93      2358379.00      7086110.00
      2358097.46      7085776.11
#Sta/Elev= 30
  4591.6  700.03  4682.2  699.26  4711.3  698.30  4752.0  697.58  4762.1  697.22
  4790.6  696.67  4795.7  696.77  4833.2  695.86  4843.3  695.87  4884.0  694.54
  4909.2  694.08  4914.4  693.73  4968.5  692.06  4993.1  690.00  4998.9  690.00
  5002.8  689.30  5085.4  689.24  5085.6  688.74  5089.1  688.74  5089.4  689.24
  5116.0  690.20  5179.7  691.50  5187.4  691.87  5230.3  692.81  5251.2  693.90
  5279.8  695.08  5300.6  695.71  5364.3  696.85  5414.2  698.10  5432.4  698.22
#Mann=3,-1,0
  4591.6    0.05       0  5085.4   0.033       0  5089.4    0.05       0
Bank Sta=5085.4,5089.4
Exp/Cntr=0.3,0.1

Type RM Length L Ch R = 1,3242,41,41,41
BEGIN DESCRIPTION:
Mapping XS 96eb68d9
END DESCRIPTION:
XS GIS Cut Line= 4
      2358783.28      7086294.88      2358598.80      7085980.18
      2358533.70      7085841.29      2358403.73      7085675.42
#Sta/Elev= 30
  4642.6  694.47  4796.3  694.24  4839.2  694.61  4868.5  694.24  4891.7  694.72
  4949.6  693.30  4972.2  689.87  4999.4  690.38  5027.7  689.24  5027.9  688.74
  5031.4  688.74  5031.7  689.24  5073.8  689.66  5084.4  689.39  5095.9  689.78
  5141.1  689.24  5151.2  689.93  5160.4  691.86  5172.6  691.54  5193.4  692.36
  5222.4  692.45  5243.2  693.20  5264.0  692.95  5292.9  693.46  5321.8  693.09
  5342.6  693.41  5350.7  692.19  5357.1  692.32  5365.2  694.01  5371.5  694.40
#Mann=3,-1,0
  4642.6    0.05       0  5027.7   0.033       0  5031.7    0.05       0
Bank Sta=5027.7,5031.7
Exp/Cntr=0.3,0.1

Type RM Length L Ch R = 1,3201,80,80,80
BEGIN DESCRIPTION:
Mapping XS 93b17d67
END DESCRIPTION:
XS GIS Cut Line= 5
      2358824.48      7086264.45      2358640.03      7085973.67
      2358598.80      7085886.87      2358564.08      7085813.08
      2358480.78      7085666.14
#Sta/Elev= 30
  4643.8  693.52  4847.3  693.69  4874.4  694.49  4883.7  693.79  4933.3  693.14
  4947.2  692.62  4956.6  691.20  4968.8  688.75  4975.7  685.89  4976.0  685.39
  4979.7  685.89  4983.7  689.26  4987.4  690.86  4992.9  690.86  5005.5  692.56
  5045.4  692.17  5051.0  693.27  5090.9  690.93  5096.4  691.68  5119.2  691.80
  5125.0  692.66  5136.0  692.46  5164.7  690.00  5186.4  691.67  5272.9  692.46
  5295.8  692.46  5304.7  690.57  5310.5  690.75  5318.8  692.63  5334.7  693.17
#Mann=3,-1,0
  4643.8    0.05       0  4975.7   0.033       0  4979.7    0.05       0
Bank Sta=4975.7,4979.7
Exp/Cntr=0.3,0.1

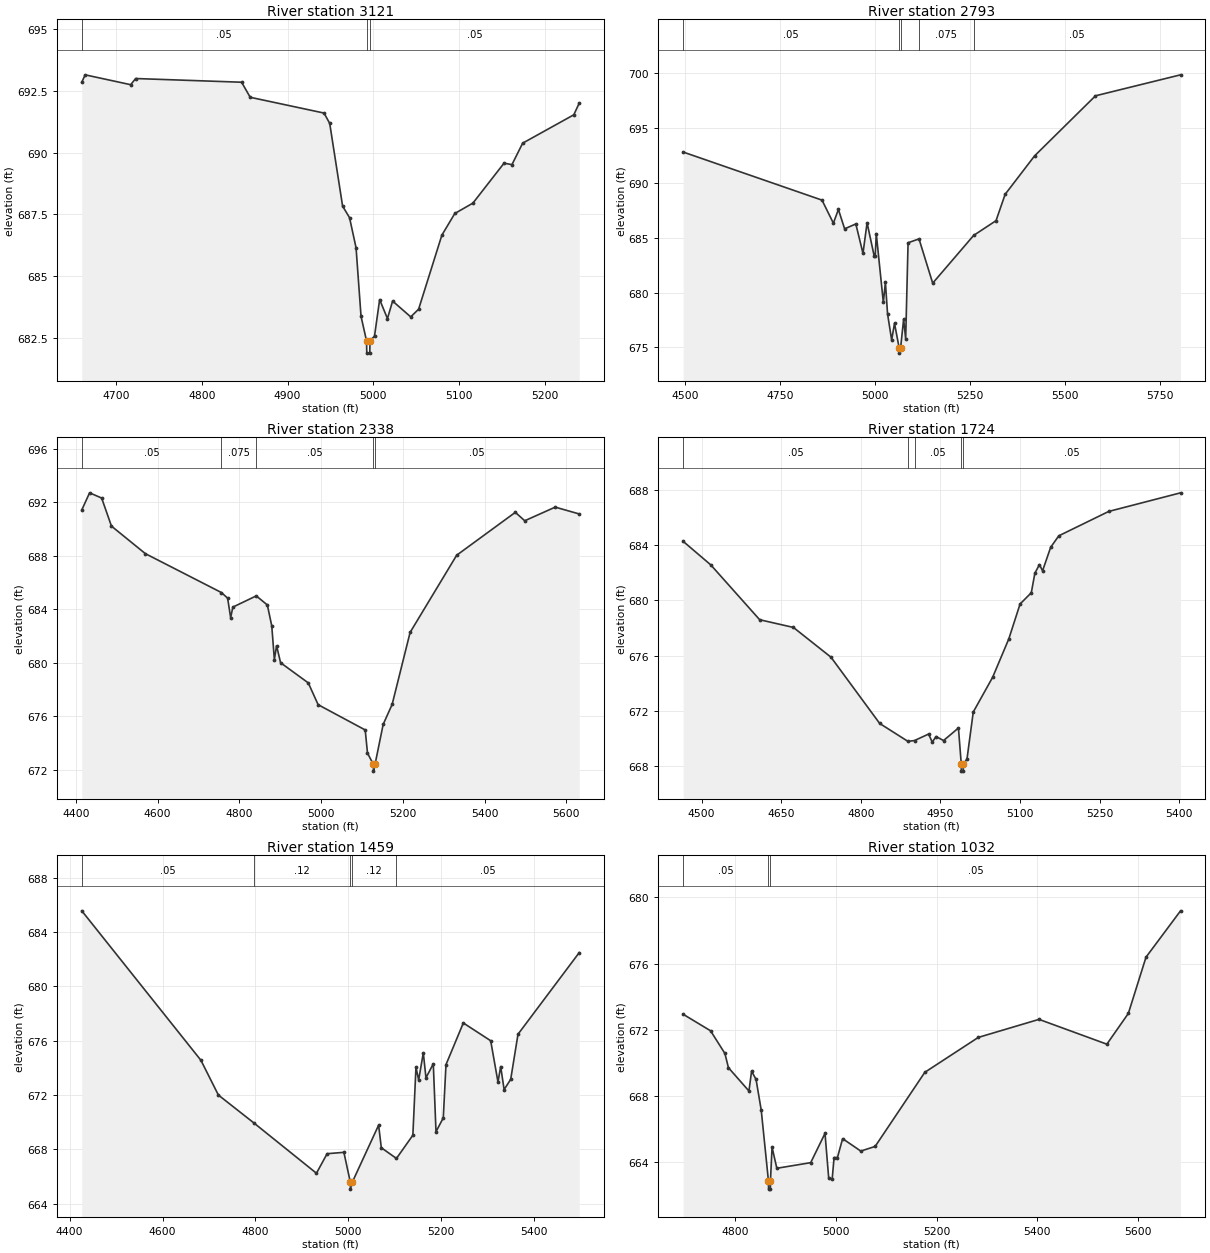
Type RM Length L Ch R = 1,3121,328,328,328
BEGIN DESCRIPTION:
Mapping XS 4b4ca053
END DESCRIPTION:
XS GIS Cut Line= 3
      2358854.89      7086210.25      2358685.60      7085917.25
      2358554.19      7085714.74
#Sta/Elev= 30
  4660.1  692.85  4664.0  693.15  4717.1  692.75  4722.9  693.00  4846.4  692.85
  4856.4  692.24  4942.5  691.60  4949.1  691.18  4964.1  687.83  4972.2  687.36
  4979.8  686.14  4985.6  683.36  4992.0  682.37  4992.3  681.87  4995.8  681.87
  4996.0  682.37  5001.3  682.56  5007.3  684.04  5016.4  683.27  5022.4  683.98
  5043.5  683.34  5052.7  683.65  5079.8  686.65  5094.9  687.53  5116.0  687.95
  5152.3  689.57  5161.5  689.51  5174.0  690.38  5233.6  691.53  5239.9  692.00
#Mann=3,-1,0
  4660.1    0.05       0  4992.0   0.033       0  4996.0    0.05       0
Bank Sta=4992,4996
Exp/Cntr=0.3,0.1

Type RM Length L Ch R = 1,2793,455,455,455
BEGIN DESCRIPTION:
Graham Branch Tr 13 6.0
END DESCRIPTION:
XS GIS Cut Line= 3
      2359142.59      7086229.21      2358954.03      7085760.08
      2358649.98      7085016.12
#Sta/Elev= 30
  4494.4  692.79  4860.0  688.41  4889.9  686.31  4903.1  687.56  4919.5  685.80
  4949.0  686.24  4967.8  683.56  4978.6  686.35  4997.3  683.32  5000.0  683.32
  5002.8  685.36  5021.4  679.09  5026.8  680.93  5032.5  678.05  5043.3  675.67
  5050.8  677.19  5062.9  674.98  5063.2  674.48  5066.9  674.98  5074.8  677.57
  5080.2  675.79  5086.5  684.53  5115.3  684.88  5151.3  680.85  5259.2  685.20
  5318.0  686.54  5342.0  688.94  5419.5  692.44  5579.8  697.91  5803.7  699.82
#Mann=5,-1,0
  4494.4    0.05       0  5062.9   0.033       0  5066.9    0.05       0
  5115.3   0.075       0  5259.2    0.05       0
Bank Sta=5062.9,5066.9
Exp/Cntr=0.3,0.1

Type RM Length L Ch R = 1,2338,614,614,614
BEGIN DESCRIPTION:
Graham Branch Tr 13 5.0
END DESCRIPTION:
XS GIS Cut Line= 3
      2359542.07      7086060.59      2359321.28      7085518.10
      2359058.59      7084943.72
#Sta/Elev= 30
  4414.3  691.44  4433.4  692.72  4462.9  692.33  4486.9  690.23  4569.9  688.17
  4756.0  685.26  4771.2  684.84  4778.6  683.38  4784.0  684.17  4841.3  685.01
  4868.4  684.33  4879.2  682.77  4885.6  680.25  4891.0  681.28  4900.8  680.01
  4968.6  678.50  4992.7  676.87  5107.9  674.98  5113.5  673.25  5127.9  672.40
  5128.1  671.90  5131.9  672.40  5151.9  675.40  5173.8  676.89  5217.8  682.28
  5331.7  688.05  5475.3  691.26  5498.3  690.63  5572.9  691.65  5631.6  691.14
#Mann=5,-1,0
  4414.3    0.05       0  4756.0   0.075       0  4841.3    0.05       0
  5127.9   0.033       0  5131.9    0.05       0
Bank Sta=5127.9,5131.9
Exp/Cntr=0.3,0.1

Type RM Length L Ch R = 1,1724,265,265,265
BEGIN DESCRIPTION:
Graham Branch Tr 13 4.0
END DESCRIPTION:
XS GIS Cut Line= 3
      2359913.04      7085469.73      2359527.11      7085099.37
      2359186.96      7084884.36
#Sta/Elev= 30
  4465.1  684.29  4517.2  682.58  4609.3  678.60  4672.9  678.04  4743.7  675.88
  4835.5  671.07  4888.7  669.77  4901.1  669.83  4927.6  670.30  4934.5  669.72
  4941.8  670.12  4955.8  669.83  4983.9  670.74  4989.2  668.11  4989.4  667.61
  4992.9  667.61  4993.2  668.11  5000.0  668.49  5011.8  671.90  5048.3  674.42
  5078.8  677.21  5100.0  679.74  5121.2  680.56  5127.9  681.98  5136.5  682.60
  5142.4  682.15  5157.7  683.86  5173.0  684.69  5267.1  686.46  5402.4  687.81
#Mann=5,-1,0
  4465.1    0.05       0  4888.7    0.12       0  4901.1    0.05       0
  4989.2   0.033       0  4993.2    0.05       0
Bank Sta=4989.2,4993.2
Exp/Cntr=0.3,0.1

Type RM Length L Ch R = 1,1459,427,427,427
BEGIN DESCRIPTION:
Graham Branch Tr 13 3.0
END DESCRIPTION:
XS GIS Cut Line= 3
      2359978.98      7085409.97      2359697.23      7084910.11
      2359448.60      7084480.11
#Sta/Elev= 30
  4426.2  685.56  4682.6  674.55  4720.2  671.99  4796.4  669.94  4931.2  666.23
  4954.2  667.67  4990.3  667.77  5004.2  665.56  5004.4  665.06  5008.2  665.56
  5065.0  669.77  5070.8  668.11  5103.4  667.32  5138.7  669.03  5145.4  674.04
  5151.2  673.10  5161.2  675.10  5166.9  673.26  5182.7  674.29  5188.5  669.29
  5204.2  670.31  5210.0  674.23  5247.3  677.30  5306.2  675.99  5321.9  672.95
  5327.7  674.09  5335.1  672.39  5349.3  673.15  5365.0  676.47  5496.7  682.48
#Mann=5,-1,0
  4426.2    0.05       0  4796.4    0.12       0  5004.2    0.07       0
  5008.2    0.12       0  5103.4    0.05       0
Bank Sta=5004.2,5008.2
Exp/Cntr=0.3,0.1

Type RM Length L Ch R = 1,1032,357,357,357
BEGIN DESCRIPTION:
Graham Branch Tr 13 2.0
END DESCRIPTION:
XS GIS Cut Line= 4
      2360206.87      7085170.37      2360155.87      7084971.79
      2360088.79      7084899.56      2359638.52      7084383.74
#Sta/Elev= 30
  4696.4  672.94  4750.9  671.94  4779.4  670.57  4786.4  669.71  4827.2  668.30
  4832.4  669.50  4841.3  669.00  4851.6  667.14  4865.9  662.87  4866.2  662.37
  4869.7  662.37  4869.9  662.87  4873.1  664.90  4882.6  663.63  4949.9  663.97
  4978.3  665.74  4985.6  663.05  4992.5  662.96  4996.3  664.28  5003.0  664.28
  5013.3  665.42  5049.4  664.67  5077.9  664.95  5176.6  669.43  5282.9  671.54
  5403.5  672.63  5538.3  671.13  5581.0  672.99  5616.1  676.39  5684.7  679.19
#Mann=3,-1,0
  4696.4    0.05       0  4865.9   0.033       0  4869.9    0.05       0
Bank Sta=4865.9,4869.9
Exp/Cntr=0.3,0.1

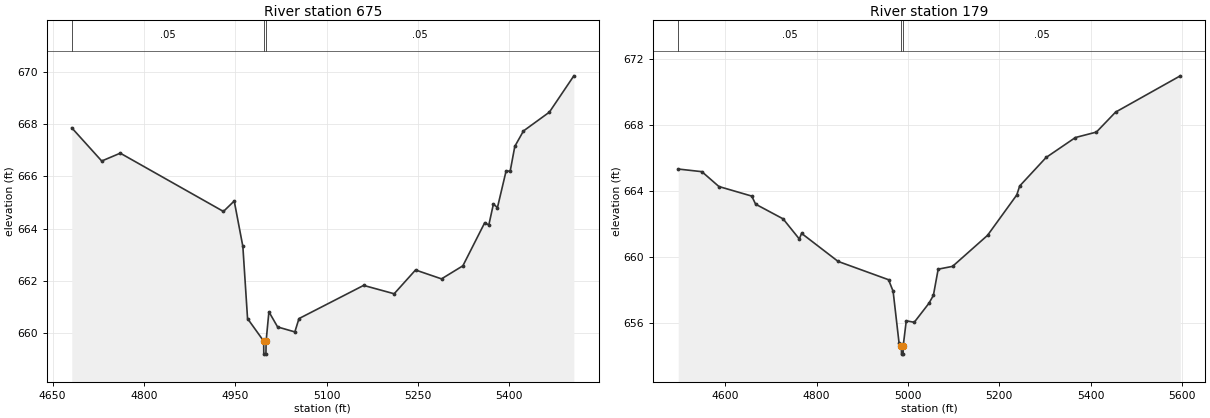
Type RM Length L Ch R = 1,675,496,496,496
BEGIN DESCRIPTION:
Mapping XS 7de2b860
END DESCRIPTION:
XS GIS Cut Line= 4
      2360454.02      7085058.49      2360410.61      7084811.09
      2360334.22      7084722.55      2360030.43      7084381.44
#Sta/Elev= 30
  4681.4  667.86  4730.6  666.59  4761.1  666.89  4930.6  664.66  4948.3  665.06
  4962.5  663.32  4970.2  660.56  4996.7  659.70  4996.9  659.20  5000.4  659.20
  5000.7  659.70  5005.3  660.82  5019.6  660.24  5047.9  660.05  5054.7  660.56
  5160.9  661.83  5211.1  661.51  5246.2  662.42  5288.9  662.08  5324.0  662.58
  5359.9  664.23  5366.6  664.14  5374.1  664.94  5380.8  664.81  5395.0  666.21
  5401.7  666.20  5409.3  667.15  5423.5  667.74  5466.1  668.46  5506.3  669.85
#Mann=3,-1,0
  4681.4    0.05       0  4996.7   0.033       0  5000.7    0.05       0
Bank Sta=4996.7,5000.7
Exp/Cntr=0.3,0.1

Type RM Length L Ch R = 1,179,0,0,0
BEGIN DESCRIPTION:
Graham Branch Tr 13 1.0
END DESCRIPTION:
XS GIS Cut Line= 3
      2360568.60      7084918.72      2360521.98      7084417.69
      2359954.04      7084235.01
#Sta/Elev= 30
  4496.8  665.33  4548.6  665.17  4585.9  664.27  4657.8  663.69  4666.3  663.20
  4726.5  662.31  4762.0  661.09  4767.0  661.43  4847.0  659.73  4957.5  658.62
  4967.5  657.92  4980.4  654.81  4985.6  654.61  4985.9  654.11  4989.4  654.11
  4989.6  654.61  4996.3  656.13  5013.8  656.04  5045.9  657.19  5055.7  657.67
  5066.2  659.26  5097.7  659.43  5174.3  661.31  5238.4  663.76  5244.7  664.30
  5302.6  666.03  5366.8  667.24  5412.8  667.57  5454.8  668.78  5596.6  670.98
#Mann=3,-1,0
  4496.8    0.05       0  4985.6   0.033       0  4989.6    0.05       0
Bank Sta=4985.6,4989.6
Exp/Cntr=0.3,0.1

Chan Stop Cuts=-1