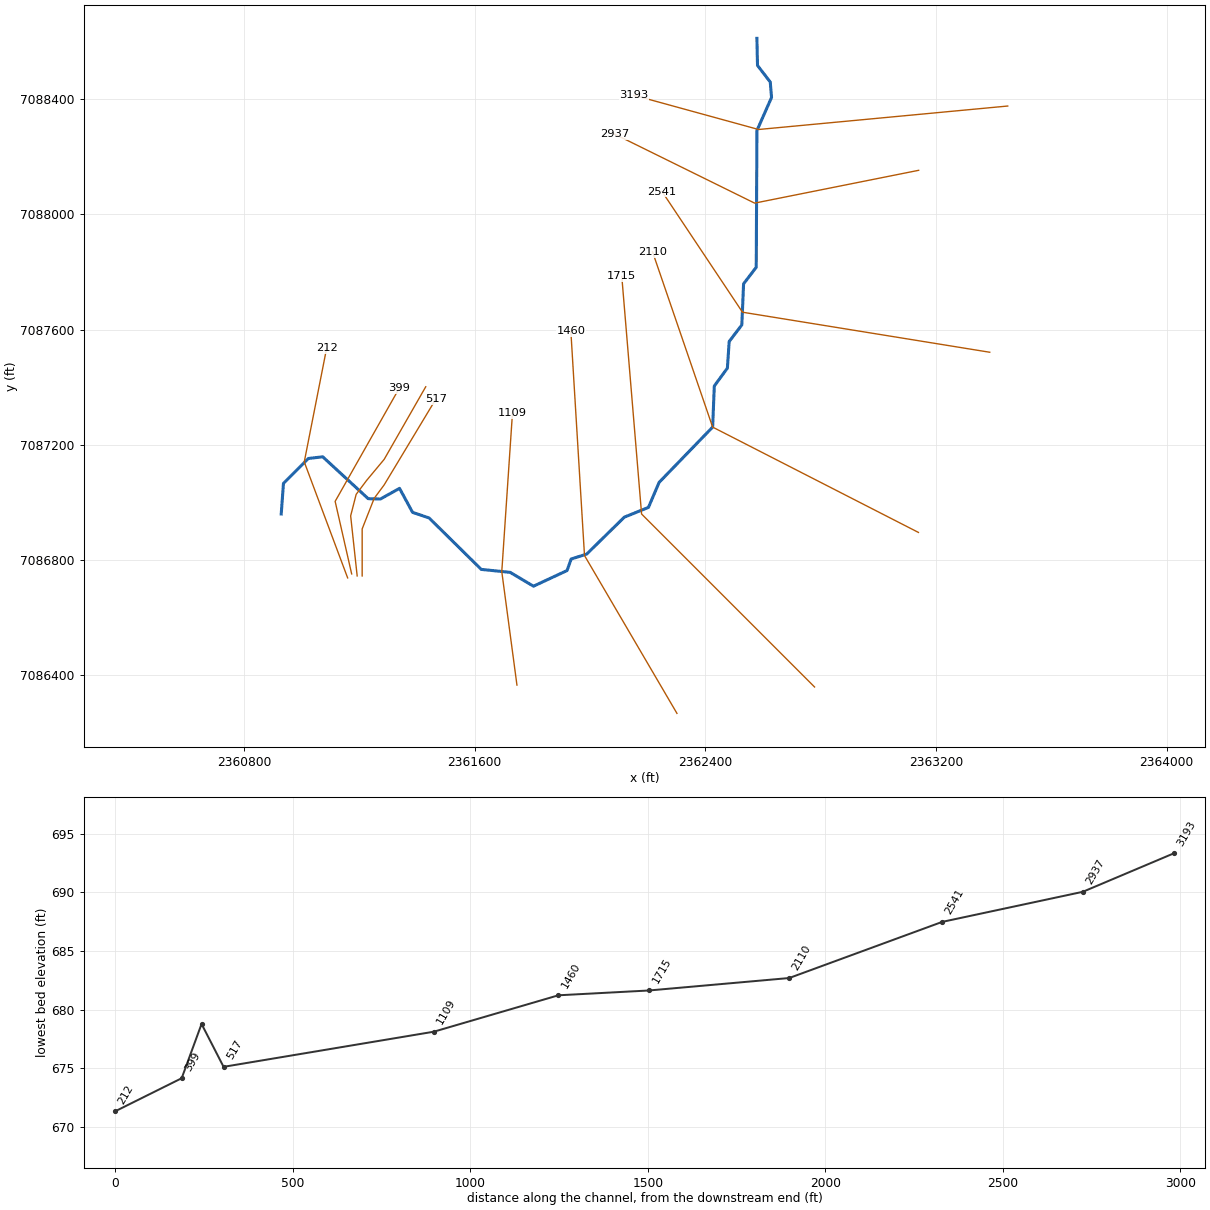
--- Graham Branch Tr 14.prj (project) ---

Proj Title=Graham Branch Tr 14 Base Level Engineering
Current Plan=p01
Default Exp/Contr=0.3,0.1
English Units
Geom File=g01
Flow File=f01
Plan File=p01
Y Axis Title=Elevation
X Axis Title(PF)=Main Channel Distance
X Axis Title(XS)=Station
BEGIN DESCRIPTION:
Graham Branch Tr 14
END DESCRIPTION:
DSS Export Rating Curves= 0
DSS Export Rating Curve Sorted= 0
DSS Export Volume Flow Curves= 0
DXF OffsetX= 0
DXF OffsetY= 0
DXF ScaleX= 1
DXF ScaleY= 10

--- Graham Branch Tr 14.p01 (plan) ---

Plan Title=Multiple Run
Short Identifier=Multiple
Geom File=g01
Flow File=f01
Subcritical Flow
K Sum by GR= 0
Std Step Tol= 0.01
Critical Tol= 0.01
Num of Std Step Trials= 20
Max Error Tol= 0.3
Flow Tol Ratio= 0.001
Split Flow NTrial= 30
Split Flow Tol= 0.02
Split Flow Ratio= 0.02
Log Output Level= 0
Friction Slope Method= 1
Unsteady Friction Slope Method= 2
Unsteady Bridges Friction Slope Method= 1
Parabolic Critical Depth
Global Vel Dist=  1 , 1 , 1
Global Log Level= 0
CheckData=True
Encroach Param= -1, 0, 0, 0
BEGIN DESCRIPTION:
Multiple Run
END DESCRIPTION:

--- Graham Branch Tr 14.f01 (steady flow) ---

Flow Title=Multiple
Program Version=4.10
Number of Profiles= 7
Profile Names=10-year,25-year,50-year,1pct_min,100-year,1pct_plu,500-year
River Rch & RM=Graham Branch Tr,Reach-1         ,3193
     185     235     273     159     317     633     426
River Rch & RM=Graham Branch Tr,Reach-1         ,2110
     447     604     733     443     884    1764    1285
River Rch & RM=Graham Branch Tr,Reach-1         ,1109
     457     618     750     453     904    1804    1314
Boundary for River Rch & Prof#=Graham Branch Tr,Reach-1         , 1
Up Type= 0
Dn Type= 3
Dn Slope=0.015
Boundary for River Rch & Prof#=Graham Branch Tr,Reach-1         , 2
Up Type= 0
Dn Type= 3
Dn Slope=0.015
Boundary for River Rch & Prof#=Graham Branch Tr,Reach-1         , 3
Up Type= 0
Dn Type= 3
Dn Slope=0.015
Boundary for River Rch & Prof#=Graham Branch Tr,Reach-1         , 4
Up Type= 0
Dn Type= 3
Dn Slope=0.015
Boundary for River Rch & Prof#=Graham Branch Tr,Reach-1         , 5
Up Type= 0
Dn Type= 3
Dn Slope=0.015
Boundary for River Rch & Prof#=Graham Branch Tr,Reach-1         , 6
Up Type= 0
Dn Type= 3
Dn Slope=0.015
Boundary for River Rch & Prof#=Graham Branch Tr,Reach-1         , 7
Up Type= 0
Dn Type= 3
Dn Slope=0.015
DSS Import GetInterval= 0
DSS Import GetPeak= 0
DSS Import FillOption= 0

--- Graham Branch Tr 14.g01 (geometry) ---

Geom Title=Existing Conditions
Program Version=4.10

River Reach=Graham Branch Tr,Reach-1
Reach XY= 30
        2362579.        7088610.      2362581.11      7088515.87
      2362625.33      7088458.42      2362629.81      7088404.97
      2362579.07      7088289.97      2362576.74      7087815.94
      2362532.79      7087758.43      2362526.73      7087615.94
      2362482.86       7087558.4      2362476.64      7087465.98
      2362431.27      7087404.06      2362425.46      7087261.47
      2362239.79      7087069.66      2362202.84      7086982.86
      2362119.34      7086949.21      2361988.43      7086820.85
      2361934.77      7086804.01      2361920.38      7086763.84
      2361804.01      7086709.58      2361723.03      7086757.62
      2361622.83      7086767.86      2361441.98      7086946.28
      2361384.62      7086965.68      2361339.35      7087048.96
      2361272.96      7087011.99      2361230.65      7087013.16
      2361072.95      7087158.42      2361022.93      7087152.55
      2360936.73      7087066.25        2360929.        7086960.

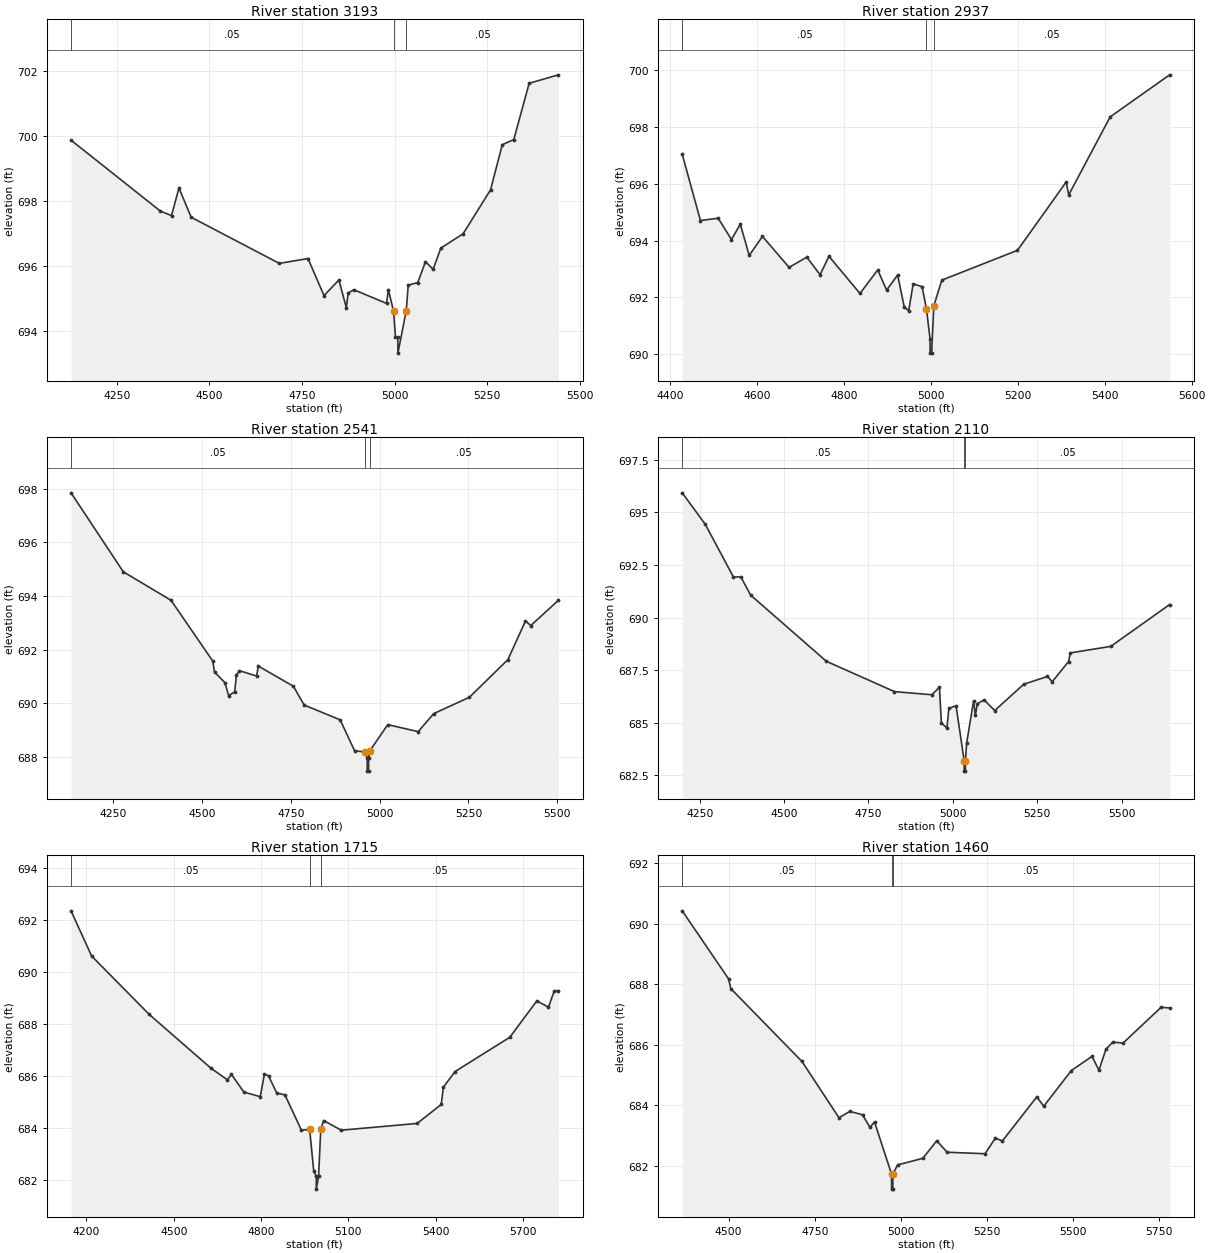
Type RM Length L Ch R = 1 ,3193    ,256,256,256
BEGIN DESCRIPTION:
Graham Branch Tr 14 8.0
END DESCRIPTION:
XS GIS Cut Line= 3
      2363449.07      7088375.19       2362584.7      7088293.78
      2362152.78      7088412.39
#Sta/Elev= 30
  4126.5  699.86  4367.6  697.68  4397.8  697.54  4417.9  698.39  4450.8  697.49
    4689  696.07  4766.4  696.22  4809.6  695.08  4849.8  695.56  4869.8  694.71
    4875  695.16  4889.9  695.26  4978.5  694.84  4983.5  695.26  4997.4   694.6
  5002.5  693.82    5009  693.81  5009.2  693.31  5031.7  694.62    5037   695.4
  5062.8  695.48  5083.6  696.12  5104.3  695.89    5125  696.54  5185.1  696.98
  5259.2  698.33    5291  699.72  5322.1  699.88  5363.6  701.61  5442.6  701.87
#Mann= 3 ,-1 , 0
  4126.5     .05       0  4997.4    .033       0  5031.7     .05       0
Bank Sta=4997.4,5031.7
XS Rating Curve= 0 ,0
Exp/Cntr=0.3,0.1

Type RM Length L Ch R = 1 ,2937    ,396,396,396
BEGIN DESCRIPTION:
Mapping XS 3d4e2cf9
END DESCRIPTION:
XS GIS Cut Line= 3
      2363140.09       7088152.2      2362571.06       7088038.4
      2362085.61      7088277.64
#Sta/Elev= 30
  4427.8  697.04  4469.7  694.71  4510.5  694.79  4541.1  694.04  4561.4  694.58
  4581.9  693.48  4612.4  694.15  4673.7  693.06  4714.4  693.42    4745   692.8
  4765.4  693.45  4836.8  692.14  4877.6  692.97    4898  692.26  4923.5  692.79
  4938.8  691.65    4949  691.54  4959.2  692.48  4979.6  692.38  4989.8   691.6
    4998  690.54  4998.2  690.04  5001.7  690.04  5006.6   691.7  5025.1  692.61
  5199.2  693.66  5311.4  696.07    5317  695.61  5412.5  698.36  5549.3  699.84
#Mann= 3 ,-1 , 0
  4427.8     .05       0  4989.8     .04       0  5006.6     .05       0
Bank Sta=4989.8,5006.6
XS Rating Curve= 0 ,0
Exp/Cntr=0.3,0.1

Type RM Length L Ch R = 1 ,2541    ,431,431,431
BEGIN DESCRIPTION:
Graham Branch Tr 14 7.0
END DESCRIPTION:
XS GIS Cut Line= 3
      2363386.76      7087521.08        2362529.        7087660.
      2362250.06      7088078.41
#Sta/Elev= 30
  4131.4  697.84  4278.5   694.9  4412.8  693.84  4530.2  691.58  4535.3  691.17
  4564.7  690.77  4574.9  690.29  4591.9  690.43    4597  691.06  4605.3  691.22
  4653.6  691.02  4658.6  691.39  4757.2  690.64  4787.6  689.94  4888.9  689.39
  4929.4  688.24  4959.8  688.19    4965  687.98  4965.2  687.48  4968.7  687.48
    4969  687.98    4972  688.23  5022.9  689.21  5108.5  688.95  5152.1  689.62
  5252.7  690.23  5360.9  691.63  5410.5  693.07  5425.5   692.9  5503.2  693.84
#Mann= 3 ,-1 , 0
  4131.4     .05       0  4959.8     .04       0    4972     .05       0
Bank Sta=4959.8,4972
XS Rating Curve= 0 ,0
Exp/Cntr=0.3,0.1

Type RM Length L Ch R = 1 ,2110    ,395,395,395
BEGIN DESCRIPTION:
Graham Branch Tr 14 6.0
END DESCRIPTION:
XS GIS Cut Line= 3
      2363139.29      7086896.11      2362425.46      7087261.47
      2362217.13      7087869.04
#Sta/Elev= 30
  4198.1  695.93  4266.5  694.43  4349.7  691.93  4371.9  691.93  4400.6  691.07
  4625.3  687.92    4827  686.48  4938.1  686.33  4960.3  686.69  4965.9  684.99
  4982.5  684.75  4988.1  685.68  5009.4  685.81  5033.4   683.2  5033.6   682.7
  5037.1   682.7  5037.4   683.2  5040.7  684.02  5061.4  686.04  5066.7  685.35
  5072.4   685.9  5092.6  686.09  5123.9  685.58  5209.9  686.83  5280.3   687.2
  5294.5  686.95  5342.8  687.91  5348.1  688.32  5467.9  688.63  5642.3  690.62
#Mann= 3 ,-1 , 0
  4198.1     .05       0  5033.4     .04       0  5037.4     .05       0
Bank Sta=5033.4,5037.4
XS Rating Curve= 0 ,0
Exp/Cntr=0.3,0.1

Type RM Length L Ch R = 1 ,1715    ,255,255,255
BEGIN DESCRIPTION:
Graham Branch Tr 14 5.0
END DESCRIPTION:
XS GIS Cut Line= 3
      2362778.98      7086360.02        2362179.        7086960.
      2362110.33      7087784.05
#Sta/Elev= 30
  4147.1  692.36  4217.8  690.62  4415.8  688.37  4627.9   686.3  4684.5  685.85
  4698.6  686.06    4741  685.38  4797.6   685.2  4811.7  686.06  4825.9  686.01
  4854.2  685.34  4882.5  685.27    4939  683.91  4967.3  683.94  4981.5  682.33
  4990.1  682.14  4990.3  681.64  4998.1  682.14  5005.6  683.97  5015.7  684.28
  5075.9  683.91  5336.8  684.17  5419.6   684.9  5427.1  685.57  5467.2  686.17
  5655.4  687.49  5748.2  688.89  5788.3  688.65  5808.4  689.28  5822.5  689.28
#Mann= 3 ,-1 , 0
  4147.1     .05       0  4967.3     .04       0  5005.6     .05       0
Bank Sta=4967.3,5005.6
XS Rating Curve= 0 ,0
Exp/Cntr=0.3,0.1

Type RM Length L Ch R = 1 ,1460    ,351,351,351
BEGIN DESCRIPTION:
Graham Branch Tr 14 4.0
END DESCRIPTION:
XS GIS Cut Line= 3
      2362301.65      7086268.43      2361980.98      7086815.94
       2361933.6       7087594.8
#Sta/Elev= 30
  4365.5  690.43    4500  688.18  4506.4  687.86  4713.1  685.45  4820.5  683.59
  4851.9   683.8  4888.8  683.69  4910.5  683.27  4923.6  683.45    4973  681.73
  4973.2  681.23  4976.7  681.23    4977  681.73  4990.7  682.03  5064.2  682.25
  5104.3  682.83  5134.3  682.45  5244.5   682.4  5274.6  682.92  5294.6  682.82
  5394.8  684.28  5414.8  683.97    5495  685.15  5555.1  685.62  5575.1  685.16
  5595.2  685.85  5615.2  686.09  5645.3  686.06  5755.5  687.24  5780.3  687.22
#Mann= 3 ,-1 , 0
  4365.5     .05       0    4973     .04       0    4977     .05       0
Bank Sta=4973,4977
XS Rating Curve= 0 ,0
Exp/Cntr=0.3,0.1

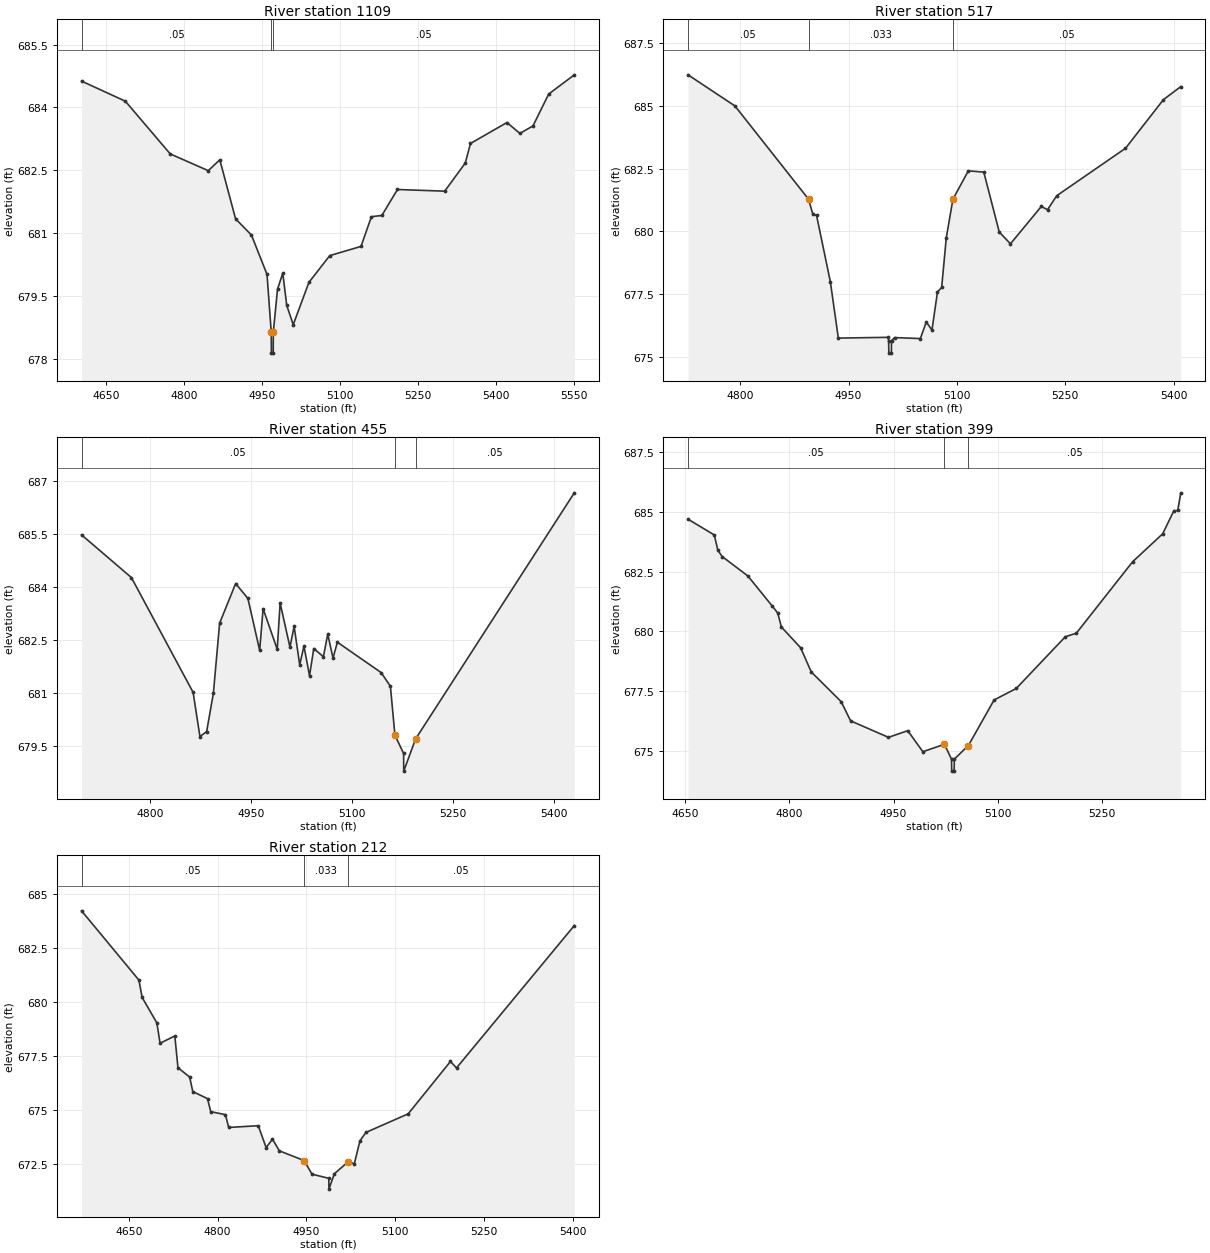
Type RM Length L Ch R = 1 ,1109    ,592,592,592
BEGIN DESCRIPTION:
Graham Branch Tr 14 3.0
END DESCRIPTION:
XS GIS Cut Line= 3
      2361746.67      7086366.53      2361694.06      7086760.13
      2361731.05      7087309.18
#Sta/Elev= 30
  4602.9  684.63  4687.1  684.15  4773.4  682.89  4846.5  682.49  4868.7  682.75
    4899  681.34  4929.6  680.95  4959.5  680.01  4967.6  678.63  4967.9  678.13
  4971.4  678.13  4971.6  678.63  4979.7  679.66  4989.8  680.04  4997.4  679.27
  5009.9  678.81    5040  679.82  5080.1  680.46  5140.2  680.68  5160.2  681.39
  5180.3  681.42  5210.3  682.04  5301.1     682  5340.6  682.67  5350.7  683.14
  5420.8  683.64  5445.7  683.38  5470.9  683.56    5501  684.32  5550.3  684.78
#Mann= 3 ,-1 , 0
  4602.9     .05       0  4967.6    .033       0  4971.6     .05       0
Bank Sta=4967.6,4971.6
XS Rating Curve= 0 ,0
Exp/Cntr=0.3,0.1

Type RM Length L Ch R = 1 ,517     ,62,62,62
BEGIN DESCRIPTION:
Mapping XS 62698447
END DESCRIPTION:
XS GIS Cut Line= 5
      2361209.77      7086745.13      2361209.77      7086908.35
      2361251.44      7087014.25      2361286.16      7087061.13
      2361464.97      7087357.98
#Sta/Elev= 30
  4727.9  686.24  4792.8     685  4894.7  681.28  4900.5  680.69  4905.8  680.63
  4924.9  677.98  4935.9  675.74  5004.9  675.77  5005.5  675.64  5005.8  675.14
  5009.3  675.14  5009.5  675.64  5013.8  675.76  5049.4  675.72  5057.6  676.38
  5065.5  676.06  5073.1  677.58  5078.9  677.76  5085.3  679.74  5094.5  681.28
  5115.8  682.41  5137.2  682.36  5158.6  679.97  5174.1   679.5  5216.8  680.99
  5225.4  680.86  5238.2  681.42  5333.3  683.31  5385.8  685.25  5409.8  685.77
#Mann= 3 ,-1 , 0
  4727.9     .05       0  4894.7    .033       0  5094.5     .05       0
Bank Sta=4894.7,5094.5
XS Rating Curve= 0 ,0
Exp/Cntr=0.3,0.1

Type RM Length L Ch R = 1 ,455     ,56,56,56
BEGIN DESCRIPTION:
Mapping XS 7ba8cd39
END DESCRIPTION:
XS GIS Cut Line= 6
      2361192.41       7086745.2      2361169.84      7086953.49
      2361188.94      7087028.14       2361225.4      7087076.75
      2361286.16      7087149.67      2361430.26       7087401.4
#Sta/Elev= 30
  4698.3  685.48  4772.4  684.27  4864.1  681.02  4874.2  679.77  4884.2  679.91
  4894.2  680.99  4903.5  682.98  4927.3   684.1  4945.5  683.68    4963  682.21
  4968.1  683.39  4989.1  682.24  4993.4  683.55    5008   682.3  5014.2  682.89
  5022.5   681.8  5028.8  682.33  5037.1  681.49  5043.4  682.26  5057.7  682.03
  5064.2  682.67    5072  681.99  5078.5  682.44  5143.6  681.58  5157.3  681.19
    5164  679.81  5176.9  679.29  5177.1  678.79  5194.7   679.7  5430.6  686.67
#Mann= 3 ,-1 , 0
  4698.3     .05       0    5164    .033       0  5194.7     .05       0
Bank Sta=5164,5194.7
XS Rating Curve= 0 ,0
Exp/Cntr=0.3,0.1

Type RM Length L Ch R = 1 ,399     ,187,187,187
BEGIN DESCRIPTION:
Mapping XS 897ce2ef
END DESCRIPTION:
XS GIS Cut Line= 3
      2361173.31      7086752.14      2361116.02      7087003.84
      2361337.93      7087395.63
#Sta/Elev= 30
  4654.5  684.69  4692.3  684.03  4697.4  683.39  4703.6  683.13  4740.5  682.32
  4775.4  681.07  4783.5  680.77  4788.7  680.19  4816.4  679.32  4831.7  678.31
  4874.7  677.07  4888.2  676.27  4942.7  675.58  4970.4  675.86  4992.1  674.98
  5023.1  675.29  5033.3  674.67  5033.6  674.17  5037.1  674.17  5037.3  674.67
  5057.6  675.24  5094.5  677.14  5126.3  677.62  5196.9  679.78  5212.8  679.93
  5293.6  682.91  5336.9  684.08  5352.8  685.03  5358.6  685.06  5362.9  685.79
#Mann= 3 ,-1 , 0
  4654.5     .05       0  5023.1    .033       0  5057.6     .05       0
Bank Sta=5023.1,5057.6
XS Rating Curve= 0 ,0
Exp/Cntr=0.3,0.1

Type RM Length L Ch R = 1 ,212     ,0,0,0
BEGIN DESCRIPTION:
Graham Branch Tr 14 1.0
END DESCRIPTION:
XS GIS Cut Line= 3
      2361159.41      7086738.25      2361008.87       7087140.6
       2361086.5      7087535.04
#Sta/Elev= 30
  4570.4  684.22  4667.2  681.02  4672.6  680.22  4697.5  679.04  4702.9   678.1
  4727.8  678.44  4733.1  676.97  4752.8  676.54  4758.1  675.87    4783  675.54
  4788.4  674.94  4813.3   674.8  4818.7  674.21  4868.6  674.29  4881.9  673.28
  4892.6  673.67  4904.2  673.13    4946  672.68  4959.4  672.05  4987.7  671.86
  4987.9  671.36    4997  672.07  5019.8  672.61  5030.8  672.54  5040.2  673.59
  5050.3  673.98  5121.7  674.84    5193  677.26  5203.2  676.96    5402  683.54
#Mann= 3 ,-1 , 0
  4570.4     .05       0    4946    .033       0  5019.8     .05       0
Bank Sta=4946,5019.8
XS Rating Curve= 0 ,0
Exp/Cntr=0.3,0.1

Chan Stop Cuts=-1
Use User Specified Reach Order=0
Composite Channel Slope=5