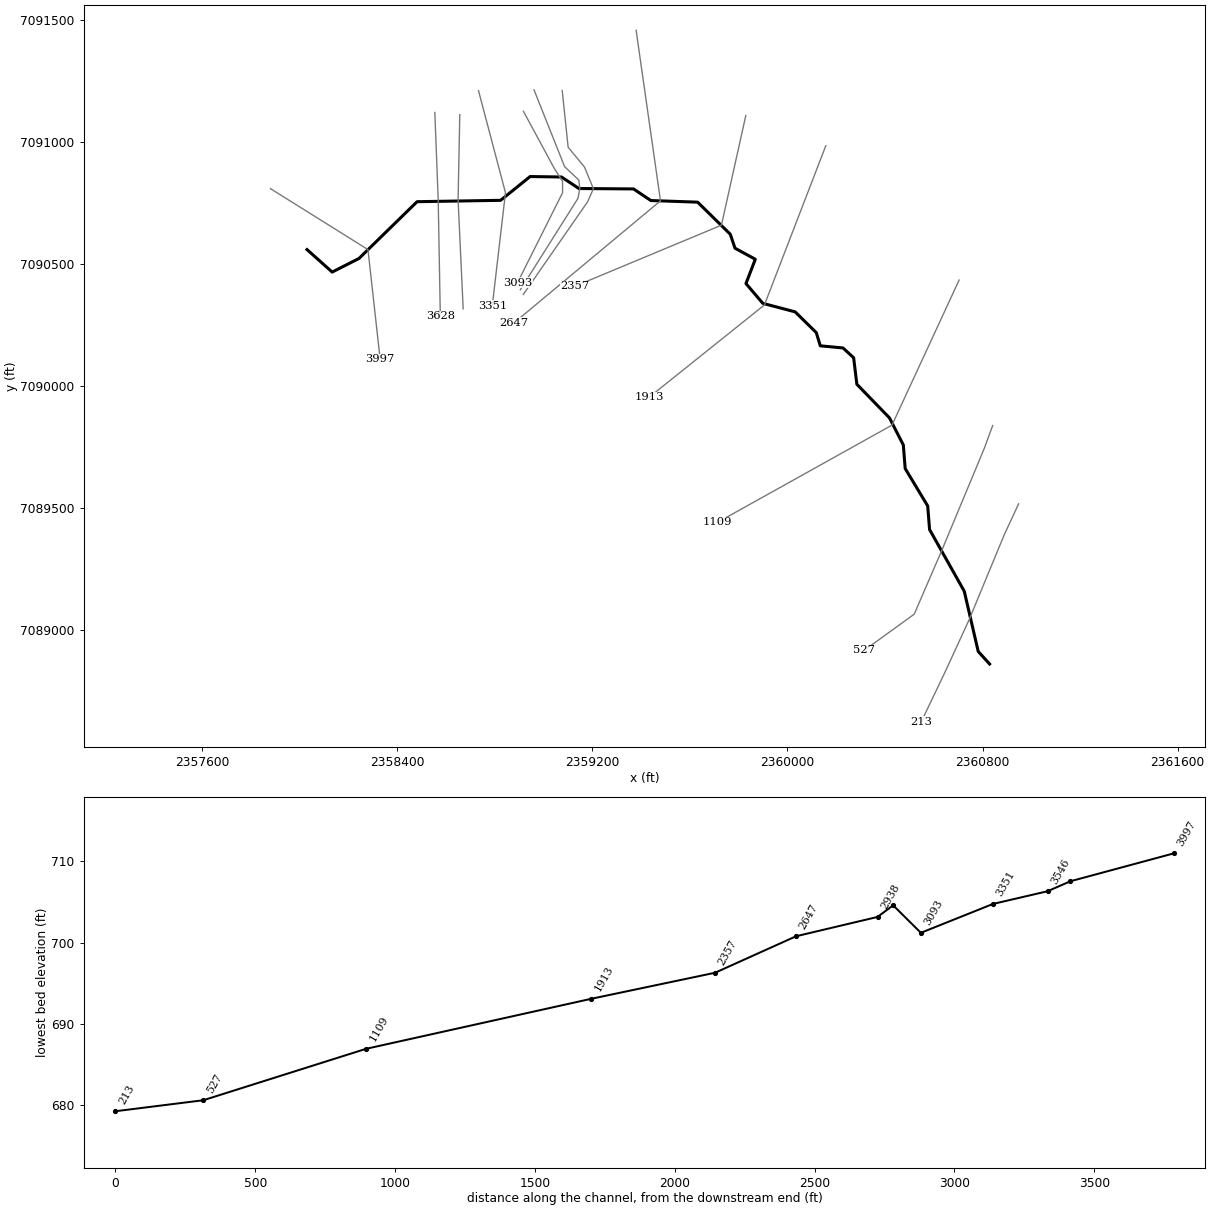
--- Graham Branch Tr 15.prj (project) ---

Proj Title=Graham Branch Tr 15 Base Level Engineering
Current Plan=p01
Default Exp/Contr=0.3,0.1
English Units
Geom File=g01
Flow File=f01
Plan File=p01
Y Axis Title=Elevation
X Axis Title(PF)=Main Channel Distance
X Axis Title(XS)=Station
BEGIN DESCRIPTION:
Graham Branch Tr 15
END DESCRIPTION:
DSS Export Rating Curves= 0
DSS Export Rating Curve Sorted= 0
DSS Export Volume Flow Curves= 0
DXF OffsetX= 0
DXF OffsetY= 0
DXF ScaleX= 1
DXF ScaleY= 10

--- Graham Branch Tr 15.p01 (plan) ---

Plan Title=Multiple Run
Short Identifier=Multiple
Geom File=g01
Flow File=f01
Subcritical Flow
K Sum by GR= 0
Std Step Tol= 0.01
Critical Tol= 0.01
Num of Std Step Trials= 20
Max Error Tol= 0.3
Flow Tol Ratio= 0.001
Split Flow NTrial= 30
Split Flow Tol= 0.02
Split Flow Ratio= 0.02
Log Output Level= 0
Friction Slope Method= 1
Unsteady Friction Slope Method= 2
Unsteady Bridges Friction Slope Method= 1
Parabolic Critical Depth
Global Vel Dist=  1 , 1 , 1
Global Log Level= 0
CheckData=True
Encroach Param= -1, 0, 0, 0
BEGIN DESCRIPTION:
Multiple Run
END DESCRIPTION:

--- Graham Branch Tr 15.f01 (steady flow) ---

Flow Title=Multiple
Program Version=4.10
Number of Profiles= 7
Profile Names=10-year,25-year,50-year,1pct_min,100-year,1pct_plu,500-year
River Rch & RM=Graham Branch Tr,Reach-1         ,3997
     316     414     492     291     581    1159     810
Boundary for River Rch & Prof#=Graham Branch Tr,Reach-1         , 1
Up Type= 0
Dn Type= 3
Dn Slope=0.00815
Boundary for River Rch & Prof#=Graham Branch Tr,Reach-1         , 2
Up Type= 0
Dn Type= 3
Dn Slope=0.00815
Boundary for River Rch & Prof#=Graham Branch Tr,Reach-1         , 3
Up Type= 0
Dn Type= 3
Dn Slope=0.00815
Boundary for River Rch & Prof#=Graham Branch Tr,Reach-1         , 4
Up Type= 0
Dn Type= 3
Dn Slope=0.00815
Boundary for River Rch & Prof#=Graham Branch Tr,Reach-1         , 5
Up Type= 0
Dn Type= 3
Dn Slope=0.00815
Boundary for River Rch & Prof#=Graham Branch Tr,Reach-1         , 6
Up Type= 0
Dn Type= 3
Dn Slope=0.00815
Boundary for River Rch & Prof#=Graham Branch Tr,Reach-1         , 7
Up Type= 0
Dn Type= 3
Dn Slope=0.00815
DSS Import GetInterval= 0
DSS Import GetPeak= 0
DSS Import FillOption= 0

--- Graham Branch Tr 15.g01 (geometry) ---

Geom Title=Existing Conditions
Program Version=4.10

River Reach=Graham Branch Tr,Reach-1
Reach XY= 30
        2358029.        7090560.      2358132.23      7090467.77
      2358242.21       7090523.6      2358480.46      7090756.46
      2358823.14      7090762.07      2358944.17      7090859.63
      2359073.06      7090857.75      2359144.22      7090810.52
       2359368.5      7090808.78      2359439.51      7090761.22
      2359631.45      7090754.54      2359765.28      7090622.98
      2359784.68      7090565.62      2359867.96      7090520.35
      2359829.64      7090420.64      2359898.71      7090339.49
      2360031.44      7090304.48      2360118.11       7090219.4
      2360134.48      7090165.26      2360227.67      7090156.46
      2360271.27       7090116.5      2360284.53      7090007.58
      2360418.24      7089869.68      2360475.17      7089758.42
      2360482.83      7089661.58      2360575.17      7089508.42
      2360582.83      7089411.58      2360725.17      7089158.42
      2360782.39       7088911.4        2360829.        7088860.

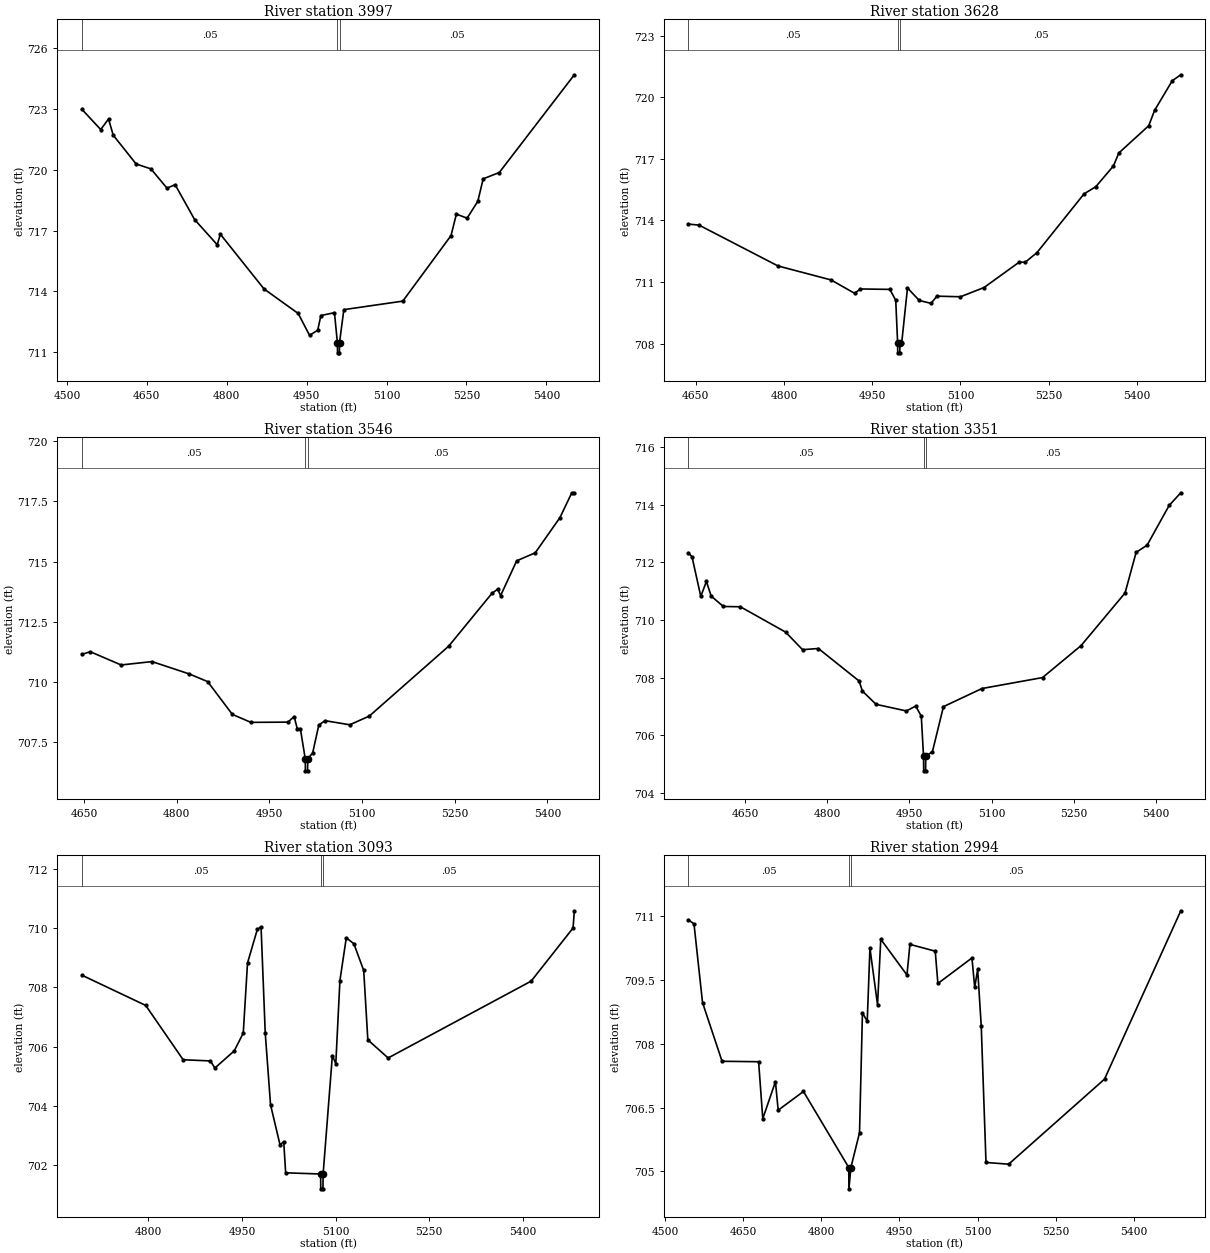
Type RM Length L Ch R = 1 ,3997    ,369,369,369
BEGIN DESCRIPTION:
Graham Branch Tr 15 10.0
END DESCRIPTION:
XS GIS Cut Line= 3
      2357879.01      7090809.99        2358279.        7090560.
        2358329.      7090109.96
#Sta/Elev= 30
    4528  722.98  4563.4  721.98  4578.1   722.5  4586.9   721.7    4630  720.28
  4657.7  720.04  4687.8  719.09  4703.1  719.26  4739.7  717.54  4782.1   716.3
    4788  716.82    4870  714.12  4934.2  712.91  4955.5  711.83  4970.8  712.09
  4976.7  712.81  5002.2  712.95  5007.7  711.47    5008  710.97  5011.5  710.97
  5011.7  711.47  5019.8   713.1  5130.5  713.52    5221  716.75  5231.1  717.81
  5251.2  717.61  5271.3  718.44  5281.4  719.55  5311.6  719.86  5452.5  724.68
#Mann= 3 ,-1 , 0
    4528     .05       0  5007.7     .04       0  5011.7     .05       0
Bank Sta=5007.7,5011.7
XS Rating Curve= 0 ,0
Exp/Cntr=0.3,0.1

Type RM Length L Ch R = 1 ,3628    ,82,82,82
BEGIN DESCRIPTION:
Mapping XS a1d0ab47
END DESCRIPTION:
XS GIS Cut Line= 3
      2358553.27      7091122.37      2358567.15      7090764.71
      2358575.84      7090285.52
#Sta/Elev= 30
  4637.5  713.82  4655.7  713.77    4790  711.78  4880.1   711.1  4920.1  710.45
  4930.1  710.66  4980.1  710.64  4990.1  710.11  4993.3  708.05  4993.5  707.55
    4997  707.55  4997.3  708.05  5000.3  708.05  5010.1  710.71  5030.1   710.1
  5050.1  709.96  5060.2  710.31  5100.2  710.28  5140.2  710.73  5200.2  711.97
  5210.2  711.96  5230.2  712.43  5310.2  715.29  5330.2  715.64  5360.2  716.65
  5369.3  717.28  5420.2  718.61  5430.2  719.36  5460.2   720.8  5474.7  721.09
#Mann= 3 ,-1 , 0
  4637.5     .05       0  4993.3     .04       0  4997.3     .05       0
Bank Sta=4993.3,4997.3
XS Rating Curve= 0 ,0
Exp/Cntr=0.3,0.1

Type RM Length L Ch R = 1 ,3546    ,195,195,195
BEGIN DESCRIPTION:
Mapping XS 612ee4ba
END DESCRIPTION:
XS GIS Cut Line= 3
       2358655.7      7091113.62      2358648.75      7090764.71
      2358669.59      7090316.77
#Sta/Elev= 30
  4646.3  711.15  4659.9  711.26  4709.9  710.71  4759.9  710.85    4820  710.34
    4850  710.02    4890  708.66    4920  708.33    4980  708.34    4990  708.57
  4995.1  708.07  5000.1  708.07    5008  706.82  5008.3  706.32  5011.8  706.32
    5012  706.82    5020  707.06    5030  708.22    5040   708.4  5080.1  708.23
  5111.7  708.59  5240.3  711.49  5310.3  713.68  5319.4  713.85  5324.4  713.59
  5350.4  715.03  5380.4  715.36  5420.4  716.82  5439.6  717.85  5443.7  717.85
#Mann= 3 ,-1 , 0
  4646.3     .05       0    5008     .04       0    5012     .05       0
Bank Sta=5008,5012
XS Rating Curve= 0 ,0
Exp/Cntr=0.3,0.1

Type RM Length L Ch R = 1 ,3351    ,258,258,258
BEGIN DESCRIPTION:
Mapping XS 13d8ac4f
END DESCRIPTION:
XS GIS Cut Line= 3
      2358732.44        7091212.      2358843.11      7090793.21
      2358788.86      7090328.83
#Sta/Elev= 30
  4545.5  712.33  4552.2   712.2  4568.3  710.82  4578.6  711.34  4587.3  710.83
  4609.6  710.47  4640.7  710.46  4723.4  709.58  4754.4  708.97  4783.4  709.01
  4857.9  707.88  4863.9  707.53  4888.9  707.07  4944.4  706.84  4961.3  707.01
  4971.6  706.66  4975.7  705.26    4976  704.76  4979.5  704.76  4979.7  705.26
    4992  705.43  5012.1  706.99  5082.6  707.62  5193.3     708  5263.8  709.11
  5344.3  710.94  5364.5  712.35  5384.6   712.6  5424.9  713.98  5446.2  714.42
#Mann= 3 ,-1 , 0
  4545.5     .05       0  4975.7    .033       0  4979.7     .05       0
Bank Sta=4975.7,4979.7
XS Rating Curve= 0 ,0
Exp/Cntr=0.3,0.1

Type RM Length L Ch R = 1 ,3093    ,99,99,99
BEGIN DESCRIPTION:
Mapping XS eca47b1e
END DESCRIPTION:
XS GIS Cut Line= 5
      2358916.66      7091127.36      2359043.41      7090892.96
      2359077.27      7090840.01      2359077.27      7090793.14
      2358892.53      7090424.31
#Sta/Elev= 30
  4693.6  708.41  4795.9  707.39  4855.8  705.56  4899.6  705.52  4906.6  705.28
  4937.7  705.86  4952.1  706.46  4958.9  708.82  4974.6  709.95  4980.6  710.04
  4987.3  706.46  4995.8  704.04    5011  702.69  5016.9   702.8    5020  701.75
    5076  701.71  5076.2  701.21  5079.7  701.21    5080  701.71  5094.8   705.7
  5100.3  705.43  5106.9  708.23  5117.1  709.67  5129.2  709.47    5145  708.57
  5151.6  706.23  5184.1  705.62  5413.2  708.21  5480.3     710  5482.3  710.58
#Mann= 3 ,-1 , 0
  4693.6     .05       0    5076    .033       0    5080     .05       0
Bank Sta=5076,5080
XS Rating Curve= 0 ,0
Exp/Cntr=0.3,0.1

Type RM Length L Ch R = 1 ,2994    ,56,56,56
BEGIN DESCRIPTION:
Mapping XS aae9efa6
END DESCRIPTION:
XS GIS Cut Line= 6
       2358960.1       7091215.4      2359085.73      7090900.12
      2359143.89      7090845.44      2359148.23      7090810.71
      2359140.42      7090769.91      2358903.97        7090395.
#Sta/Elev= 30
  4544.5  710.92  4555.4  710.82  4571.8  708.97  4609.3  707.59  4679.5  707.58
  4687.5  706.24  4711.8  707.11  4717.1  706.44  4765.6  706.88  4852.7  705.09
  4852.9  704.59  4856.7  705.09  4873.3  705.91  4878.9  708.73  4888.1  708.53
  4893.3  710.25  4907.9  708.92  4914.1  710.46  4964.4  709.62  4970.1  710.34
  5018.7  710.18  5023.8  709.42  5089.2  710.02  5094.5  709.33  5100.2  709.75
  5107.1  708.41  5116.2  705.21  5159.7  705.17  5343.8  707.17  5490.3  711.13
#Mann= 3 ,-1 , 0
  4544.5     .05       0  4852.7    .033       0  4856.7     .05       0
Bank Sta=4852.7,4856.7
XS Rating Curve= 0 ,0
Exp/Cntr=0.3,0.1

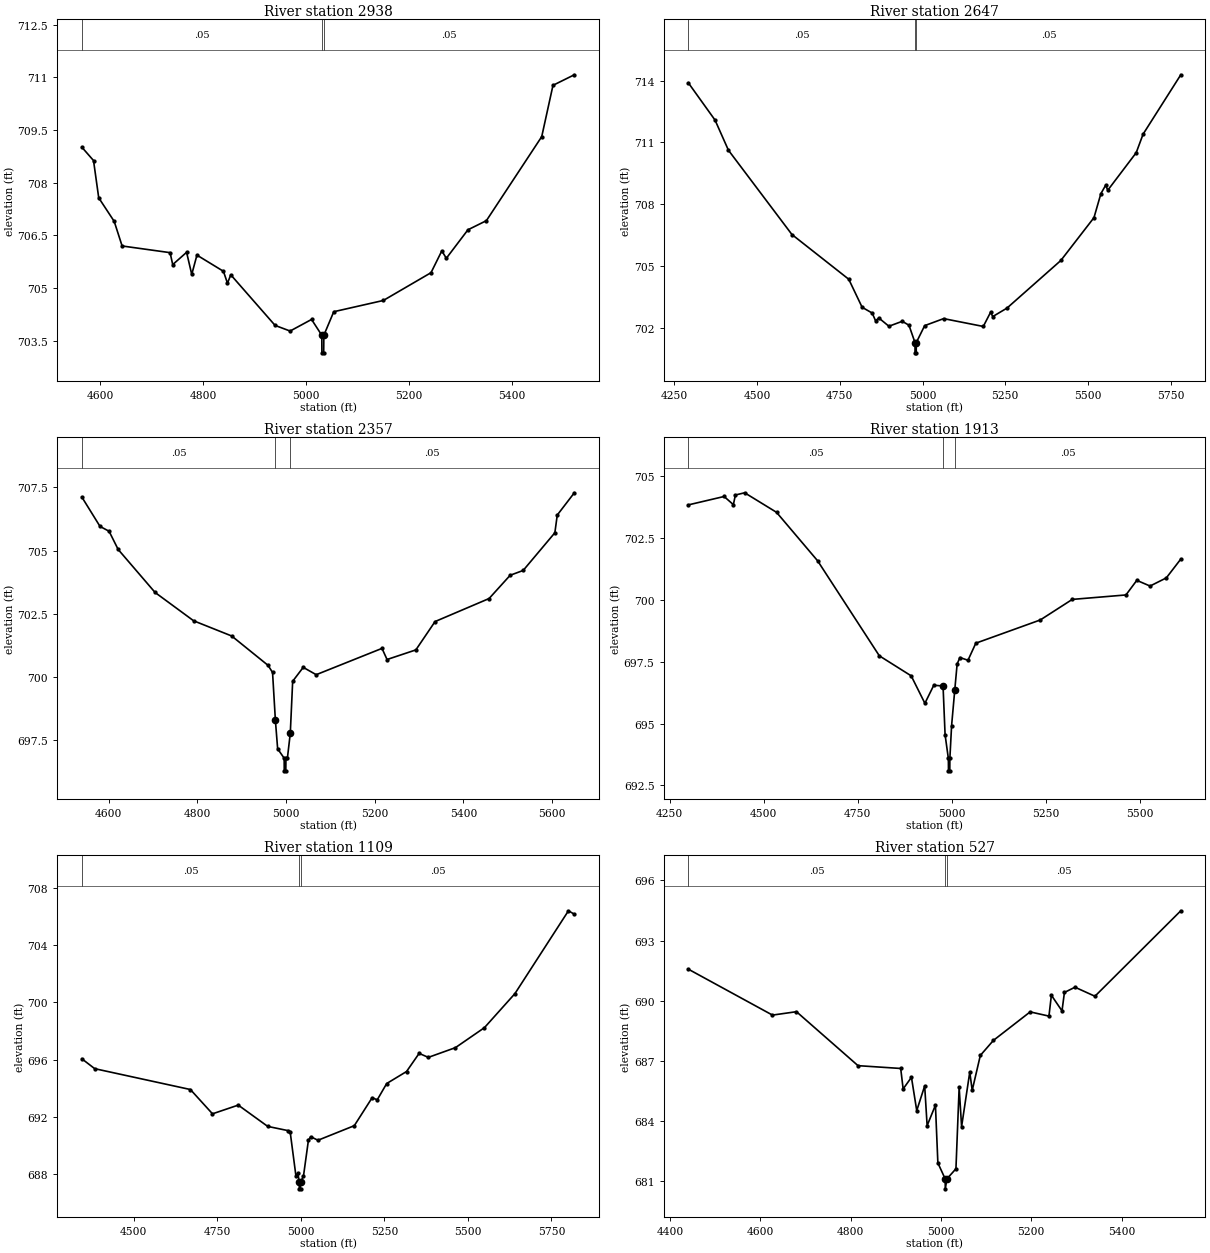
Type RM Length L Ch R = 1 ,2938    ,291,291,291
BEGIN DESCRIPTION:
Mapping XS 90ef695a
END DESCRIPTION:
XS GIS Cut Line= 6
      2359075.84      7091212.58      2359100.14      7090979.98
      2359167.33      7090898.39      2359203.78      7090809.79
        2359180.      7090756.03      2358916.09      7090375.78
#Sta/Elev= 30
    4564  709.01  4586.7  708.63  4596.8  707.57  4626.9   706.9  4642.3   706.2
  4735.6  706.01  4740.7  705.67  4767.7  706.02  4777.7  705.39  4787.8  705.94
  4839.3  705.48  4847.2  705.14  4853.6  705.38  4939.8  703.94    4969  703.78
  5010.7  704.11  5030.6  703.66  5030.8  703.16  5034.3  703.16  5034.6  703.66
  5053.9  704.33  5150.3  704.65    5243  705.44    5264  706.06  5272.8  705.85
  5314.8  706.66  5350.7  706.92  5458.3  709.31  5480.2  710.77  5521.7  711.07
#Mann= 3 ,-1 , 0
    4564     .05       0  5030.6    .033       0  5034.6     .05       0
Bank Sta=5030.6,5034.6
XS Rating Curve= 0 ,0
Exp/Cntr=0.3,0.1

Type RM Length L Ch R = 1 ,2647    ,290,290,290
BEGIN DESCRIPTION:
Graham Branch Tr 15 5.0
END DESCRIPTION:
XS GIS Cut Line= 3
        2359379.      7091459.97        2359479.        7090760.
        2358879.        7090260.
#Sta/Elev= 30
  4292.3  713.89  4373.1  712.08  4413.5  710.62  4605.4  706.53  4777.1  704.36
  4817.5     703  4847.9  702.72    4858  702.35  4868.1  702.48  4898.4  702.08
  4938.8  702.32    4959  702.13  4977.2  701.29  4977.4  700.79  4980.9  700.79
  4981.2  701.29  5006.5  702.11  5063.8  702.45  5183.6  702.07  5205.7  702.76
  5212.2  702.55  5255.2  702.96  5417.9  705.27  5518.1  707.35  5538.9  708.51
  5553.3  708.92  5559.8  708.68  5645.7   710.5  5666.5   711.4  5780.4  714.28
#Mann= 3 ,-1 , 0
  4292.3     .05       0  4977.2    .033       0  4981.2     .05       0
Bank Sta=4977.2,4981.2
XS Rating Curve= 0 ,0
Exp/Cntr=0.3,0.1

Type RM Length L Ch R = 1 ,2357    ,444,444,444
BEGIN DESCRIPTION:
Graham Branch Tr 15 4.0
END DESCRIPTION:
XS GIS Cut Line= 3
      2359828.99      7091109.98        2359729.        7090660.
      2359128.96      7090409.98
#Sta/Elev= 30
  4539.3  707.12  4580.3  705.96  4600.7  705.77  4621.2  705.05  4704.5  703.35
  4791.5  702.23  4877.3  701.63  4959.3  700.47  4969.5  700.19  4975.9   698.3
    4981  697.17  4995.7   696.8  4995.9   696.3  4999.4   696.3  4999.7   696.8
    5003   696.8  5009.5  697.78  5014.9  699.84  5038.7  700.39    5068   700.1
  5216.4  701.14  5227.8   700.7  5292.8  701.08  5336.1   702.2    5458  703.11
  5505.6  704.03  5534.9  704.22  5606.4  705.71  5611.8  706.41  5650.3  707.29
#Mann= 3 ,-1 , 0
  4539.3     .05       0  4975.9    .033       0  5009.5     .05       0
Bank Sta=4975.9,5009.5
XS Rating Curve= 0 ,0
Exp/Cntr=0.3,0.1

Type RM Length L Ch R = 1 ,1913    ,804,804,804
BEGIN DESCRIPTION:
Graham Branch Tr 15 3.0
END DESCRIPTION:
XS GIS Cut Line= 3
      2360157.19      7090986.12      2359905.42      7090332.86
      2359431.18      7089953.34
#Sta/Elev= 30
  4299.9  703.84  4394.9  704.18  4419.5  703.85  4424.9  704.24  4449.5  704.33
  4534.1  703.54  4643.2  701.58    4807  697.74  4891.6  696.93    4928  695.82
  4951.6  696.55  4976.2  696.52  4981.6  694.55  4990.3  693.59  4990.6  693.09
  4994.1  693.09  4994.3  693.59  4998.9  694.92  5007.2  696.34  5013.6  697.41
    5021  697.67  5042.4  697.56  5063.2  698.25  5234.5  699.19  5319.3  700.02
  5461.8   700.2  5490.6  700.79  5525.8  700.56    5569  700.89  5607.4  701.65
#Mann= 3 ,-1 , 0
  4299.9     .05       0  4976.2    .033       0  5007.2     .05       0
Bank Sta=4976.2,5007.2
XS Rating Curve= 0 ,0
Exp/Cntr=0.3,0.1

Type RM Length L Ch R = 1 ,1109    ,582,582,582
BEGIN DESCRIPTION:
Graham Branch Tr 15 2.0
END DESCRIPTION:
XS GIS Cut Line= 3
      2360703.99      7090434.98      2360428.69      7089839.87
      2359713.63      7089441.37
#Sta/Elev= 30
  4344.3  696.05  4382.8  695.36  4669.3   693.9  4735.4   692.2  4812.5  692.81
  4900.7  691.32  4962.4  691.02  4967.9  690.94  4985.3  687.83  4990.8  688.05
  4995.2  687.45  4995.4  686.95  4998.9  686.95  4999.2  687.45  5007.7  687.83
  5022.5  690.34  5029.4   690.6  5051.1  690.35  5159.9  691.37  5213.4  693.33
  5228.6  693.18  5256.9  694.32  5316.3  695.16    5354  696.43  5381.5  696.15
  5462.6  696.83  5549.5  698.23  5640.7  700.61    5801  706.41  5818.6  706.17
#Mann= 3 ,-1 , 0
  4344.3     .05       0  4995.2    .033       0  4999.2     .05       0
Bank Sta=4995.2,4999.2
XS Rating Curve= 0 ,0
Exp/Cntr=0.3,0.1

Type RM Length L Ch R = 1 ,527     ,314,314,314
BEGIN DESCRIPTION:
Mapping XS d45b396d
END DESCRIPTION:
XS GIS Cut Line= 5
       2360841.8      7089838.32      2360807.29      7089744.61
      2360631.51      7089322.52      2360519.75      7089064.27
      2360315.72      7088916.68
#Sta/Elev= 30
  4440.8  691.58  4627.1  689.29  4680.2  689.46  4816.5  686.77    4911  686.63
  4916.4  685.61  4934.8  686.19  4946.5  684.53  4964.1  685.76  4969.5  683.78
  4987.9   684.8  4993.3  681.92  5009.4  681.13  5009.7  680.63  5013.4  681.13
  5033.3  681.63  5040.4  685.69  5045.8  683.73  5063.9  686.45  5069.3  685.54
  5087.3  687.28  5116.3  688.03  5197.6  689.45  5239.2  689.24  5244.6  690.28
  5268.1   689.5  5273.5  690.42  5296.9  690.68    5341  690.23  5531.1  694.49
#Mann= 3 ,-1 , 0
  4440.8     .05       0  5009.4    .033       0  5013.4     .05       0
Bank Sta=5009.4,5013.4
XS Rating Curve= 0 ,0
Exp/Cntr=0.3,0.1

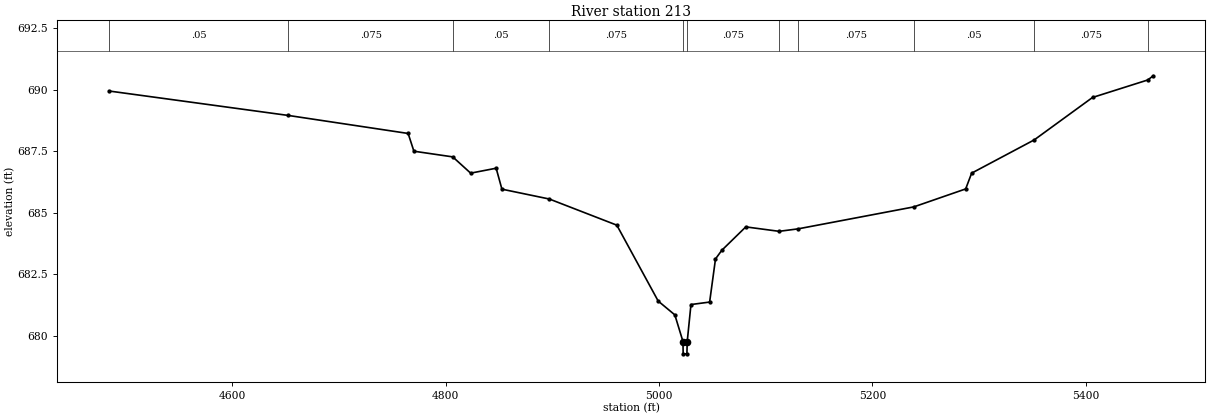
Type RM Length L Ch R = 1 ,213     ,0,0,0
BEGIN DESCRIPTION:
Graham Branch Tr 15 1.0
END DESCRIPTION:
XS GIS Cut Line= 5
      2360948.15      7089517.18      2360888.87      7089389.52
      2360745.91      7089043.43       2360646.7      7088827.73
       2360549.3      7088624.04
#Sta/Elev= 30
  4484.8  689.94  4652.6  688.95  4764.8  688.22  4770.2   687.5  4806.6  687.27
  4823.4  686.61  4847.3  686.81  4852.7  685.96  4897.2  685.56  4960.4   684.5
  4999.2  681.42  5014.8  680.86  5022.4  679.78  5022.6  679.28  5026.1  679.28
  5026.4  679.78  5029.9  681.28  5047.4  681.38  5052.9  683.13  5058.8  683.48
  5081.3  684.43  5112.5  684.25  5130.3  684.35  5238.7  685.24  5287.4  685.97
    5293  686.61  5351.7  687.96  5406.3  689.68  5458.1  690.39  5463.2  690.56
#Mann= 11 ,-1 , 0
  4484.8     .05       0  4652.6    .075       0  4806.6     .05       0
  4897.2    .075       0  5022.4     .07       0  5026.4    .075       0
  5112.5     .05       0  5130.3    .075       0  5238.7     .05       0
  5351.7    .075       0  5458.1     .05       0
Bank Sta=5022.4,5026.4
XS Rating Curve= 0 ,0
Exp/Cntr=0.3,0.1

Chan Stop Cuts=-1
Use User Specified Reach Order=0
Composite Channel Slope=5