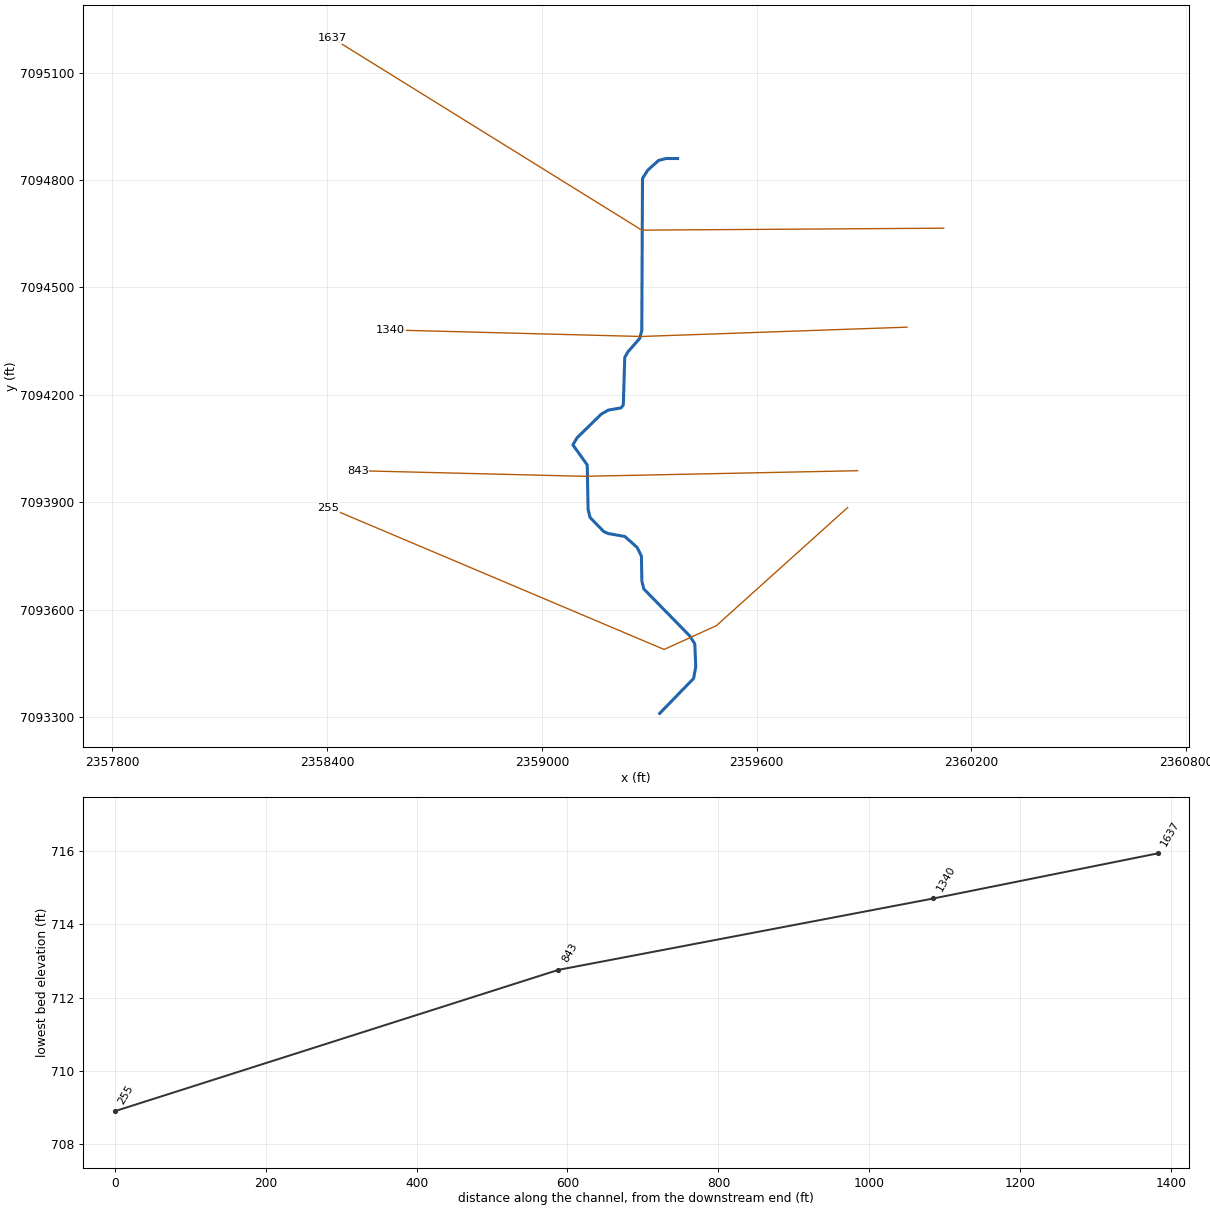
--- Graham Branch Tr 16.prj (project) ---

Proj Title=Graham Branch Tr 16 Base Level Engineering
Current Plan=p01
Default Exp/Contr=0.3,0.1
English Units
Geom File=g01
Flow File=f01
Plan File=p01
BEGIN DESCRIPTION:
Graham Branch Tr 16
END DESCRIPTION:

--- Graham Branch Tr 16.p01 (plan) ---

Plan Title=Multiple Run
Short Identifier=Multiple
Geom File=g01
Flow File=f01
Subcritical Flow
K Sum by GR= 0
Std Step Tol= 0.01
Critical Tol= 0.01
Num of Std Step Trials= 20
Max Error Tol= 0.3
Flow Tol Ratio= 0.001
Split Flow NTrial= 30
Split Flow Tol= 0.02
Split Flow Ratio= 0.02
Log Output Level= 0
Friction Slope Method= 1
Unsteady Friction Slope Method= 2
Unsteady Bridges Friction Slope Method= 1
Parabolic Critical Depth
Global Vel Dist=  1 , 1 , 1
Global Log Level= 0
CheckData=True
Encroach Param= -1, 0, 0, 0
BEGIN DESCRIPTION:
Multiple Run
END DESCRIPTION:

--- Graham Branch Tr 16.f01 (steady flow) ---

Flow Title=Multiple
Number of Profiles=7
Profile Names=10-year,25-year,50-year,1pct_min,100-year,1pct_plu,500-year
River Rch & RM= Graham Branch Tr,Reach-1,1637
     168     211     243     140     279     556     366
Boundary for River Rch & Prof#=Graham Branch Tr,Reach-1,1
Up Type=0
Dn Type=3
Dn Slope=0.005
Boundary for River Rch & Prof#=Graham Branch Tr,Reach-1,2
Up Type=0
Dn Type=3
Dn Slope=0.005
Boundary for River Rch & Prof#=Graham Branch Tr,Reach-1,3
Up Type=0
Dn Type=3
Dn Slope=0.005
Boundary for River Rch & Prof#=Graham Branch Tr,Reach-1,4
Up Type=0
Dn Type=3
Dn Slope=0.005
Boundary for River Rch & Prof#=Graham Branch Tr,Reach-1,5
Up Type=0
Dn Type=3
Dn Slope=0.005
Boundary for River Rch & Prof#=Graham Branch Tr,Reach-1,6
Up Type=0
Dn Type=3
Dn Slope=0.005
Boundary for River Rch & Prof#=Graham Branch Tr,Reach-1,7
Up Type=0
Dn Type=3
Dn Slope=0.005

--- Graham Branch Tr 16.g01 (geometry) ---

Geom Title=Existing Conditions

River Reach=Graham Branch Tr,Reach-1
Reach XY= 30
      2359379.00      7094860.00      2359346.92      7094860.16
      2359326.05      7094854.87      2359295.12      7094827.14
      2359280.93      7094804.31      2359278.93      7094380.03
      2359273.25      7094357.67      2359239.86      7094319.64
      2359231.28      7094304.05      2359227.36      7094171.83
      2359220.89      7094163.39      2359185.51      7094157.27
      2359165.99      7094146.26      2359098.28      7094080.07
      2359086.31      7094060.11      2359126.52      7094004.14
      2359128.93      7093879.89      2359134.36      7093857.30
      2359172.64      7093818.03      2359184.88      7093812.47
      2359231.55      7093804.25      2359265.74      7093773.65
      2359277.90      7093749.67      2359279.14      7093680.06
      2359284.53      7093657.58      2359412.60      7093526.75
      2359427.04      7093504.11      2359429.69      7093439.93
      2359423.67      7093407.55      2359329.00      7093310.00

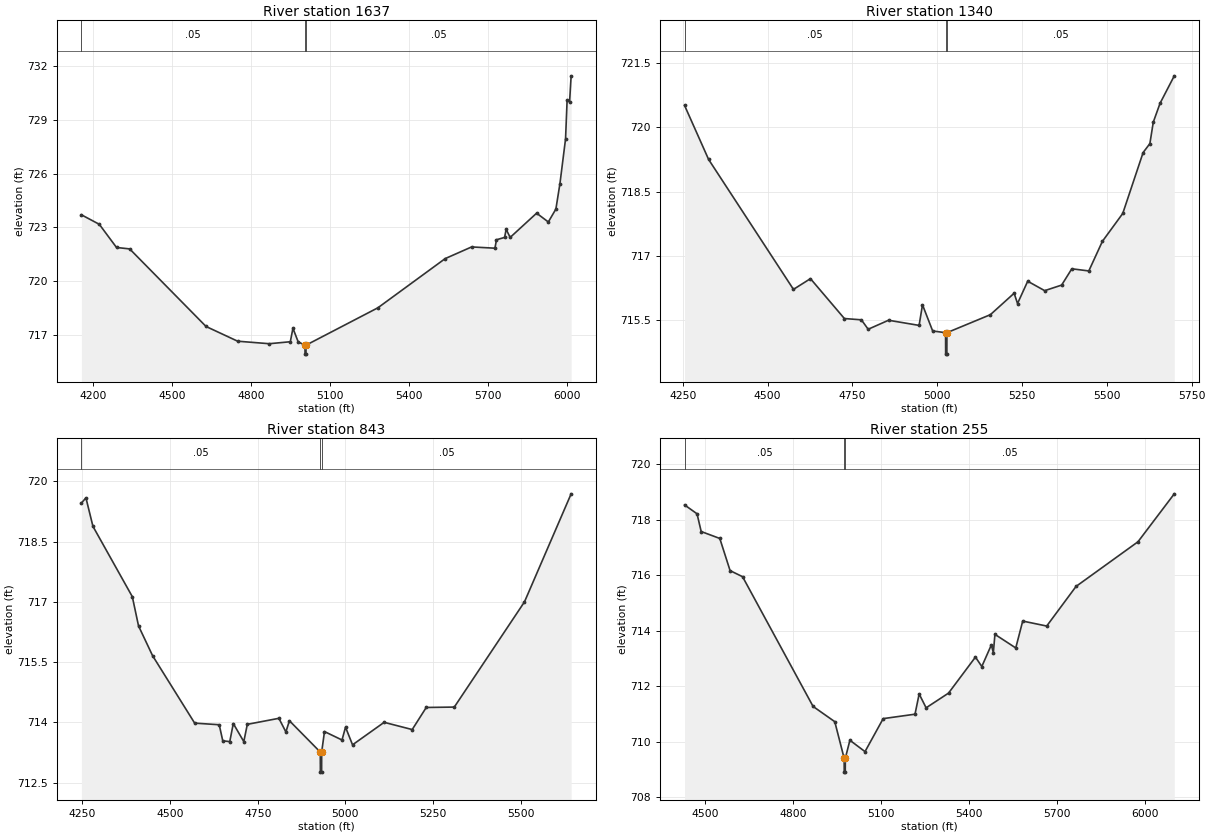
Type RM Length L Ch R = 1,1637,297,297,297
BEGIN DESCRIPTION:
Graham Branch Tr 16 3.0
END DESCRIPTION:
XS GIS Cut Line= 3
      2360122.33      7094665.44      2359279.00      7094660.00
      2358415.37      7095195.83
#Sta/Elev= 30
  4156.6  723.70  4224.6  723.17  4289.9  721.88  4339.9  721.80  4629.9  717.48
  4749.9  716.66  4869.9  716.52  4949.9  716.63  4959.9  717.38  4979.9  716.62
  5005.6  716.44  5005.9  715.94  5009.4  715.94  5009.6  716.44  5282.4  718.52
  5538.0  721.26  5638.3  721.91  5727.0  721.84  5732.8  722.31  5763.6  722.44
  5769.5  722.89  5784.8  722.44  5885.2  723.79  5929.7  723.30  5958.4  724.02
  5973.8  725.44  5995.1  727.93  6001.0  730.08  6010.4  729.99  6016.3  731.44
#Mann=3,-1,0
  4156.6    0.05       0  5005.6   0.033       0  5009.6    0.05       0
Bank Sta=5005.6,5009.6
Exp/Cntr=0.3,0.1

Type RM Length L Ch R = 1,1340,497,497,497
BEGIN DESCRIPTION:
Mapping XS c08b34a1
END DESCRIPTION:
XS GIS Cut Line= 3
      2360019.85      7094388.95      2359277.67      7094362.91
      2358577.14      7094381.14
#Sta/Elev= 30
  4255.4  720.51  4326.3  719.25  4576.4  716.22  4626.5  716.47  4726.5  715.54
  4776.6  715.51  4796.6  715.29  4856.6  715.50  4946.7  715.38  4956.7  715.86
  4986.7  715.25  5024.7  715.21  5025.0  714.71  5028.5  714.71  5028.7  715.21
  5156.8  715.63  5226.8  716.13  5236.8  715.89  5266.8  716.41  5316.8  716.19
  5366.8  716.32  5396.8  716.70  5446.9  716.65  5486.9  717.34  5546.9  717.99
  5606.9  719.41  5626.9  719.62  5636.9  720.12  5656.9  720.56  5698.8  721.20
#Mann=3,-1,0
  4255.4    0.05       0  5024.7   0.033       0  5028.7    0.05       0
Bank Sta=5024.7,5028.7
Exp/Cntr=0.3,0.1

Type RM Length L Ch R = 1,843,588,588,588
BEGIN DESCRIPTION:
Mapping XS e159d625
END DESCRIPTION:
XS GIS Cut Line= 3
      2359881.87      7093987.91      2359118.82      7093972.29
      2358486.02      7093987.91
#Sta/Elev= 30
  4247.3  719.46  4260.2  719.59  4280.2  718.88  4392.4  717.13  4410.2  716.40
  4450.2  715.66  4570.2  713.98  4640.2  713.94  4650.3  713.54  4670.3  713.52
  4680.3  713.97  4710.3  713.52  4720.3  713.95  4810.3  714.10  4830.3  713.76
  4840.3  714.04  4928.3  713.26  4928.6  712.76  4932.1  712.76  4932.3  713.26
  4940.3  713.77  4990.3  713.56  5000.3  713.88  5020.3  713.44  5110.4  714.00
  5190.4  713.82  5230.4  714.37  5310.4  714.38  5510.5  717.00  5643.5  719.69
#Mann=3,-1,0
  4247.3    0.05       0  4928.3   0.033       0  4932.3    0.05       0
Bank Sta=4928.3,4932.3
Exp/Cntr=0.3,0.1

Type RM Length L Ch R = 1,255,0,0,0
BEGIN DESCRIPTION:
Graham Branch Tr 16 1.0
END DESCRIPTION:
XS GIS Cut Line= 4
      2359853.98      7093884.98      2359487.18      7093554.97
      2359341.35      7093488.56      2358403.99      7093885.01
#Sta/Elev= 30
  4428.6  718.54  4471.2  718.22  4485.4  717.58  4548.9  717.33  4584.0  716.17
  4626.6  715.95  4867.3  711.27  4941.3  710.72  4973.3  709.40  4973.6  708.90
  4977.1  708.90  4977.3  709.40  4992.9  710.05  5044.5  709.64  5106.5  710.83
  5215.1  710.99  5229.3  711.72  5253.0  711.22  5329.5  711.75  5421.4  713.05
  5443.1  712.71  5475.7  713.49  5482.5  713.21  5487.9  713.87  5559.0  713.38
  5582.7  714.35  5664.6  714.17  5764.8  715.60  5976.1  717.21  6100.0  718.94
#Mann=3,-1,0
  4428.6    0.05       0  4973.3   0.033       0  4977.3    0.05       0
Bank Sta=4973.3,4977.3
Exp/Cntr=0.3,0.1

Chan Stop Cuts=-1