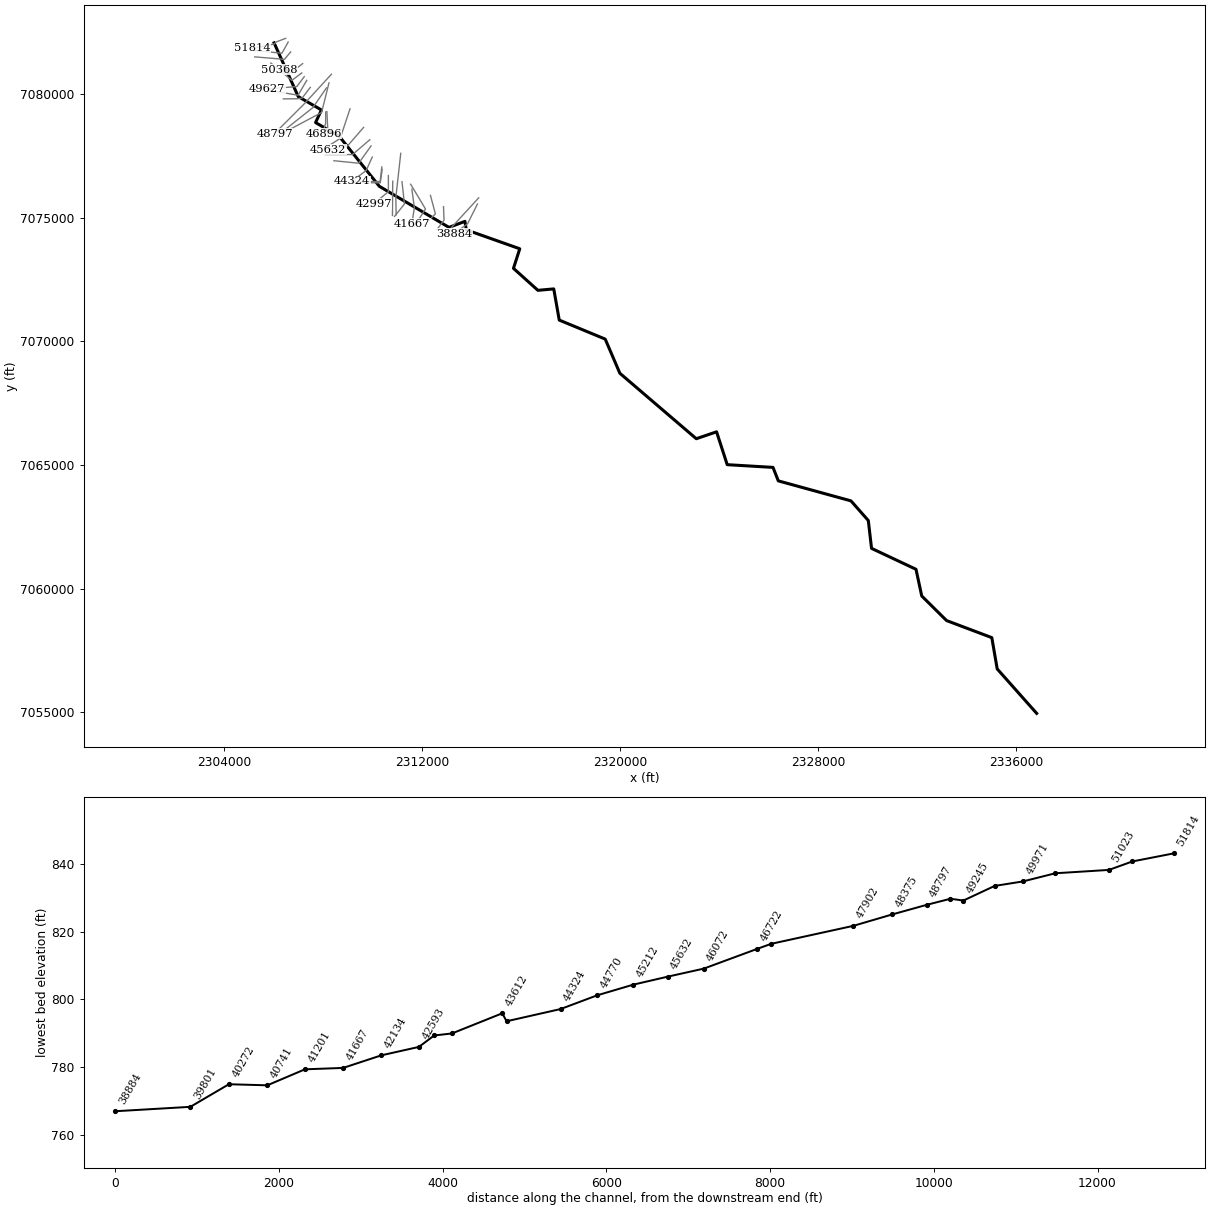
--- Harriet Creek.prj (project) ---

Proj Title=Harriet Creek Base Level Engineering
Current Plan=p01
Default Exp/Contr=0.3,0.1
English Units
Geom File=g01
Flow File=f01
Plan File=p01
BEGIN DESCRIPTION:
Harriet Creek
END DESCRIPTION:

--- Harriet Creek.p01 (plan) ---

Plan Title=Multiple Run
Short Identifier=Multiple
Geom File=g01
Flow File=f01
Subcritical Flow
K Sum by GR= 0
Std Step Tol= 0.01
Critical Tol= 0.01
Num of Std Step Trials= 20
Max Error Tol= 0.3
Flow Tol Ratio= 0.001
Split Flow NTrial= 30
Split Flow Tol= 0.02
Split Flow Ratio= 0.02
Log Output Level= 0
Friction Slope Method= 0
Unsteady Friction Slope Method= 2
Unsteady Bridges Friction Slope Method= 1
Parabolic Critical Depth
Global Vel Dist=  1 , 1 , 1
Global Log Level= 0
CheckData=True
Encroach Param= -1, 0, 0, 0
BEGIN DESCRIPTION:
Multiple Run
END DESCRIPTION:

--- Harriet Creek.f01 (steady flow) ---

Flow Title=Multiple
Number of Profiles=7
Profile Names=10-year,25-year,50-year,1pct_min,100-year,1pct_plu,500-year
River Rch & RM= Harriet Creek,Reach-1,51814
     325     427     507     300     599    1190     835
River Rch & RM= Harriet Creek,Reach-1,50368
     554     753     916     553    1100    2200    1600
River Rch & RM= Harriet Creek,Reach-1,48797
     738    1020    1250     764    1520    3040    2260
River Rch & RM= Harriet Creek,Reach-1,44324
     915    1280    1580     973    1940    3870    2920
River Rch & RM= Harriet Creek,Reach-1,41201
     962    1350    1670    1030    2050    4090    3090
River Rch & RM= Harriet Creek,Reach-1,38884
    1300    1840    2300    1430    2850    5680    4360
River Rch & RM= Harriet Creek,Reach-1,33527
    1310    1860    2330    1450    2880    5750    4420
River Rch & RM= Harriet Creek,Reach-1,32371
    1620    2330    2940    1830    3650    7280    5670
River Rch & RM= Harriet Creek,Reach-1,28620
    1640    2360    2970    1850    3700    7370    5740
River Rch & RM= Harriet Creek,Reach-1,28047
    3020    4440    5690    3600    7180   14300   11500
River Rch & RM= Harriet Creek,Reach-1,24237
    3060    4490    5760    3650    7280   14500   11600
River Rch & RM= Harriet Creek,Reach-1,23673
    3150    4640    5950    3770    7510   15000   12000
River Rch & RM= Harriet Creek,Reach-1,22060
    3160    4650    5960    3780    7530   15000   12100
River Rch & RM= Harriet Creek,Reach-1,20954
    3220    4750    6090    3860    7700   15400   12300
River Rch & RM= Harriet Creek,Reach-1,18773
    3290    4850    6230    3940    7870   15700   12600
River Rch & RM= Harriet Creek,Reach-1,14841
    3300    4860    6240    3950    7880   15700   12600
River Rch & RM= Harriet Creek,Reach-1,14289
    3480    5140    6600    4180    8350   16700   13400
River Rch & RM= Harriet Creek,Reach-1,9857
    3560    5260    6750    4280    8550   17100   13700
River Rch & RM= Harriet Creek,Reach-1,8195
    3640    5370    6910    4380    8740   17400   14100
River Rch & RM= Harriet Creek,Reach-1,4310
    3700    5470    7040    4470    8920   17800   14400
Boundary for River Rch & Prof#=Harriet Creek,Reach-1,1
Up Type=0
Dn Type=3
Dn Slope=0.005
Boundary for River Rch & Prof#=Harriet Creek,Reach-1,2
Up Type=0
Dn Type=3
Dn Slope=0.005
Boundary for River Rch & Prof#=Harriet Creek,Reach-1,3
Up Type=0
Dn Type=3
Dn Slope=0.005
Boundary for River Rch & Prof#=Harriet Creek,Reach-1,4
Up Type=0
Dn Type=3
Dn Slope=0.005
Boundary for River Rch & Prof#=Harriet Creek,Reach-1,5
Up Type=0
Dn Type=3
Dn Slope=0.005
Boundary for River Rch & Prof#=Harriet Creek,Reach-1,6
Up Type=0
Dn Type=3
Dn Slope=0.005
Boundary for River Rch & Prof#=Harriet Creek,Reach-1,7
Up Type=0
Dn Type=3
Dn Slope=0.005

--- Harriet Creek.g01 (geometry) ---

Geom Title=Existing Conditions

River Reach=Harriet Creek,Reach-1
Reach XY= 30
      2306009.98      7082076.68      2306986.88      7079903.87
      2307923.58      7079362.67      2307686.76      7078853.83
      2308649.51      7078290.26      2310262.29      7076276.64
      2313080.25      7074613.45      2313723.24      7074858.15
      2313775.97      7074515.47      2315938.81      7073749.49
      2315684.46      7072957.55      2316671.94      7072068.97
      2317312.37      7072126.68      2317534.61      7070865.59
      2319392.28      7070096.59      2319984.11      7068715.11
      2323072.81      7066067.81      2323892.67      7066346.78
      2324322.94      7065018.14      2326173.15      7064907.94
      2326387.31      7064363.15      2329323.39      7063554.41
      2330025.25      7062758.45      2330155.48      7061632.87
      2331952.47      7060786.99      2332184.46      7059707.55
      2333187.44      7058713.40      2335015.96      7058023.02
      2335234.47      7056757.55      2336829.00      7054960.00

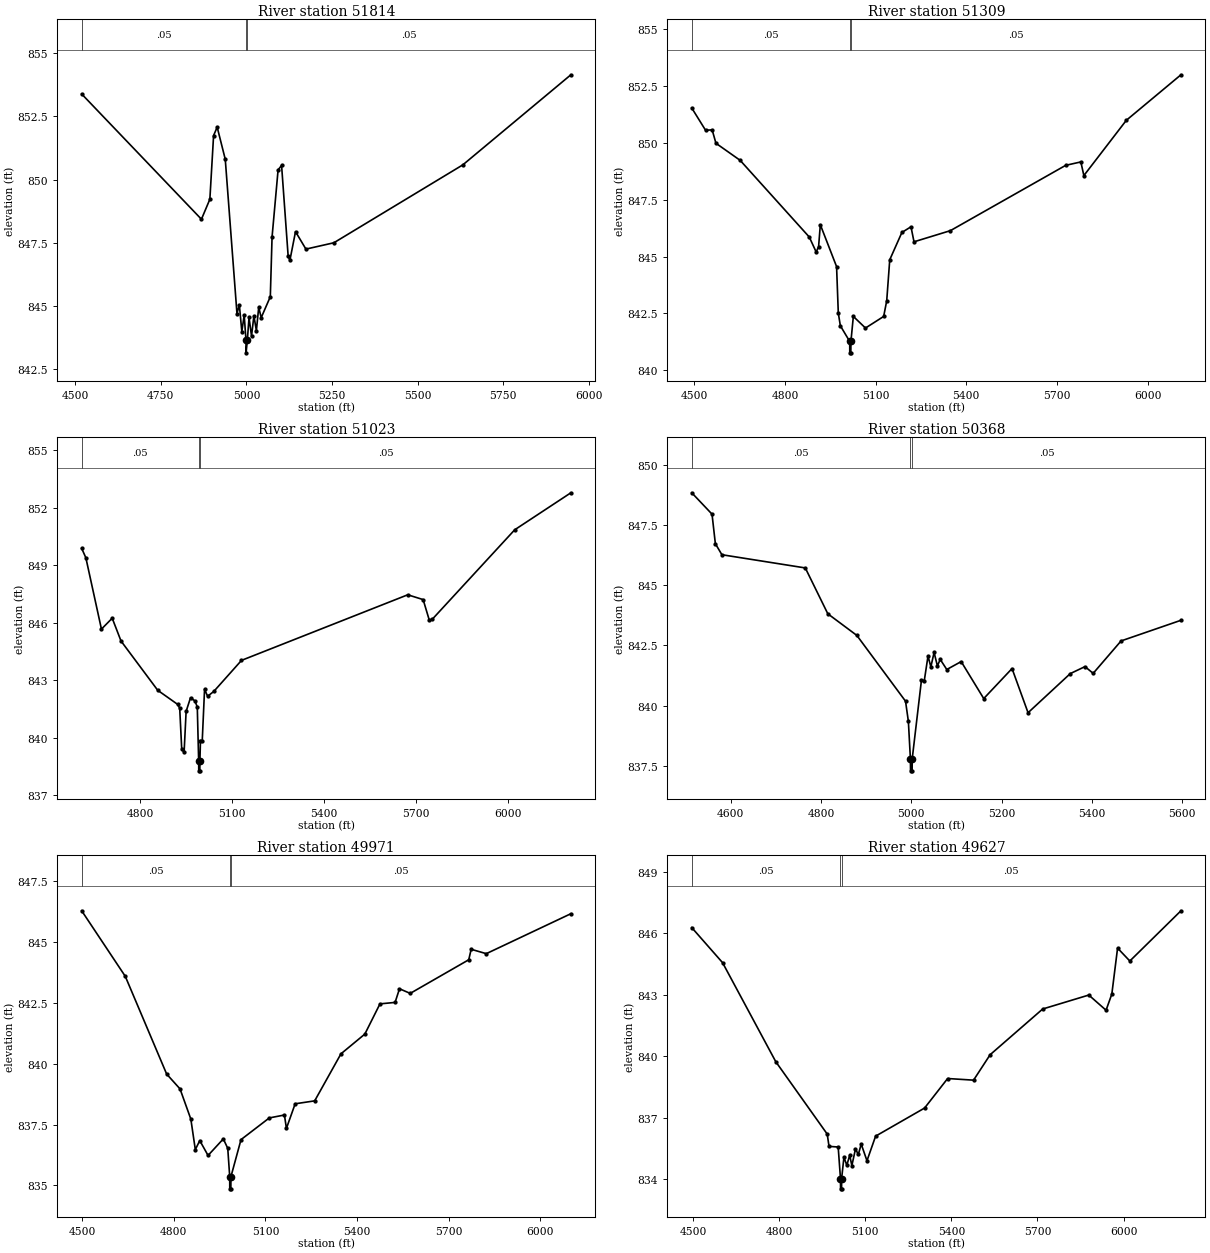
Type RM Length L Ch R = 1,51814,505,505,505
BEGIN DESCRIPTION:
Harriet Creek 95.0
END DESCRIPTION:
XS GIS Cut Line= 4
      2306479.00      7082260.00      2306092.04      7082113.02
      2306013.50      7082029.79      2305129.02      7081860.00
#Sta/Elev= 30
  4518.7  853.38  4868.5  848.43  4893.1  849.22  4904.0  851.74  4914.5  852.07
  4938.1  850.80  4972.3  844.70  4979.2  845.05  4986.5  843.99  4993.4  844.64
  4998.6  843.65  4998.9  843.15  5002.6  843.65  5007.5  844.55  5014.8  843.81
  5021.7  844.61  5029.0  844.03  5035.8  844.95  5043.1  844.54  5069.7  845.37
  5074.8  847.73  5092.4  850.38  5102.6  850.56  5121.7  846.99  5126.8  846.80
  5143.3  847.94  5173.7  847.25  5255.3  847.50  5632.1  850.58  5947.7  854.14
#Mann=3,-1,0
  4518.7    0.05       0  4998.6   0.033       0  5002.6    0.05       0
Bank Sta=4998.6,5002.6
Exp/Cntr=0.3,0.1

Type RM Length L Ch R = 1,51309,286,286,286
BEGIN DESCRIPTION:
Harriet Creek 94.0
END DESCRIPTION:
XS GIS Cut Line= 3
      2306579.02      7082110.04      2306329.00      7081660.00
      2305228.96      7081760.00
#Sta/Elev= 30
  4491.3  851.53  4537.1  850.55  4558.8  850.57  4571.4  849.98  4651.5  849.23
  4880.3  845.86  4903.2  845.20  4911.2  845.44  4916.9  846.40  4970.7  844.56
  4976.4  842.52  4983.2  841.96  5014.2  841.27  5014.4  840.77  5017.9  840.77
  5018.2  841.27  5026.2  842.37  5066.4  841.86  5126.6  842.37  5136.7  843.06
  5146.7  844.86  5186.9  846.06  5217.0  846.31  5227.0  845.65  5347.5  846.14
  5729.1  849.01  5779.3  849.16  5789.3  848.56  5929.9  850.99  6110.7  852.99
#Mann=3,-1,0
  4491.3    0.05       0  5014.2   0.033       0  5018.2    0.05       0
Bank Sta=5014.2,5018.2
Exp/Cntr=0.3,0.1

Type RM Length L Ch R = 1,51023,655,655,655
BEGIN DESCRIPTION:
Harriet Creek 93.0
END DESCRIPTION:
XS GIS Cut Line= 3
      2306678.97      7081709.97      2306429.00      7081410.00
      2305229.03      7081510.00
#Sta/Elev= 30
  4609.2  849.87  4622.8  849.38  4673.6  845.66  4708.7  846.23  4737.4  845.04
  4857.1  842.47  4921.6  841.74  4928.7  841.54  4935.2  839.42  4943.0  839.23
  4949.6  841.37  4963.9  842.08  4978.2  841.92  4986.0  841.60  4990.5  838.77
  4990.8  838.27  4994.3  838.27  4994.5  838.77  4996.4  839.85  5002.2  839.85
  5009.7  842.52  5019.7  842.16  5039.8  842.41  5130.1  844.03  5672.0  847.45
  5722.2  847.20  5742.2  846.13  5752.3  846.18  6020.7  850.84  6203.8  852.77
#Mann=3,-1,0
  4609.2    0.05       0  4990.5   0.033       0  4994.5    0.05       0
Bank Sta=4990.5,4994.5
Exp/Cntr=0.3,0.1

Type RM Length L Ch R = 1,50368,397,397,397
BEGIN DESCRIPTION:
Harriet Creek 92.5
END DESCRIPTION:
XS GIS Cut Line= 5
      2307164.56      7081237.59      2306701.05      7080880.85
      2306578.66      7080878.24      2306346.89      7080917.30
      2306227.07      7080992.84
#Sta/Elev= 30
  4513.5  848.86  4558.4  847.97  4565.8  846.74  4580.3  846.28  4765.1  845.73
  4815.0  843.82  4879.3  842.92  4987.2  840.18  4993.5  839.34  4998.0  837.78
  4998.3  837.28  5001.8  837.28  5002.0  837.78  5022.5  841.06  5028.8  841.04
  5037.0  842.06  5043.3  841.61  5050.5  842.21  5057.8  841.65  5064.1  841.92
  5078.6  841.50  5110.5  841.83  5160.5  840.29  5223.2  841.54  5258.7  839.70
  5352.3  841.33  5384.8  841.62  5403.0  841.34  5464.8  842.69  5597.5  843.55
#Mann=3,-1,0
  4513.5    0.05       0  4998.0   0.033       0  5002.0    0.05       0
Bank Sta=4998,5002
Exp/Cntr=0.3,0.1

Type RM Length L Ch R = 1,49971,344,344,344
BEGIN DESCRIPTION:
Harriet Creek 92.0
END DESCRIPTION:
XS GIS Cut Line= 3
      2307129.02      7080860.01      2306729.00      7080560.00
      2305878.97      7081260.03
#Sta/Elev= 30
  4498.7  846.27  4641.4  843.58  4776.8  839.57  4820.6  838.96  4856.0  837.72
  4870.6  836.47  4885.2  836.84  4912.3  836.23  4962.3  836.91  4976.8  836.52
  4983.2  835.36  4983.4  834.86  4986.9  834.86  4987.2  835.36  5020.2  836.88
  5112.8  837.77  5162.3  837.89  5168.8  837.34  5197.4  838.35  5261.3  838.47
  5347.3  840.40  5425.5  841.21  5475.0  842.45  5524.5  842.51  5538.9  843.07
  5574.0  842.88  5765.6  844.26  5773.5  844.69  5823.0  844.51  6099.9  846.15
#Mann=3,-1,0
  4498.7    0.05       0  4983.2   0.033       0  4987.2    0.05       0
Bank Sta=4983.2,4987.2
Exp/Cntr=0.3,0.1

Type RM Length L Ch R = 1,49627,382,382,382
BEGIN DESCRIPTION:
Harriet Creek 91.0
END DESCRIPTION:
XS GIS Cut Line= 3
      2307229.02      7080710.03      2306929.00      7080310.00
      2305729.00      7080210.00
#Sta/Elev= 30
  4495.6  846.28  4602.9  844.57  4788.3  839.74  4967.5  836.21  4973.8  835.61
  5005.7  835.58  5013.7  834.04  5014.0  833.54  5017.5  833.54  5017.7  834.04
  5025.7  835.08  5035.8  834.69  5045.8  835.18  5053.3  834.67  5065.9  835.48
  5075.9  835.22  5086.0  835.72  5106.0  834.91  5136.1  836.11  5306.7  837.48
  5387.0  838.92  5477.3  838.84  5535.0  840.08  5718.1  842.31  5878.7  842.99
  5938.9  842.25  5959.0  843.04  5979.0  845.28  6021.7  844.65  6199.8  847.10
#Mann=3,-1,0
  4495.6    0.05       0  5013.7   0.033       0  5017.7    0.05       0
Bank Sta=5013.7,5017.7
Exp/Cntr=0.3,0.1

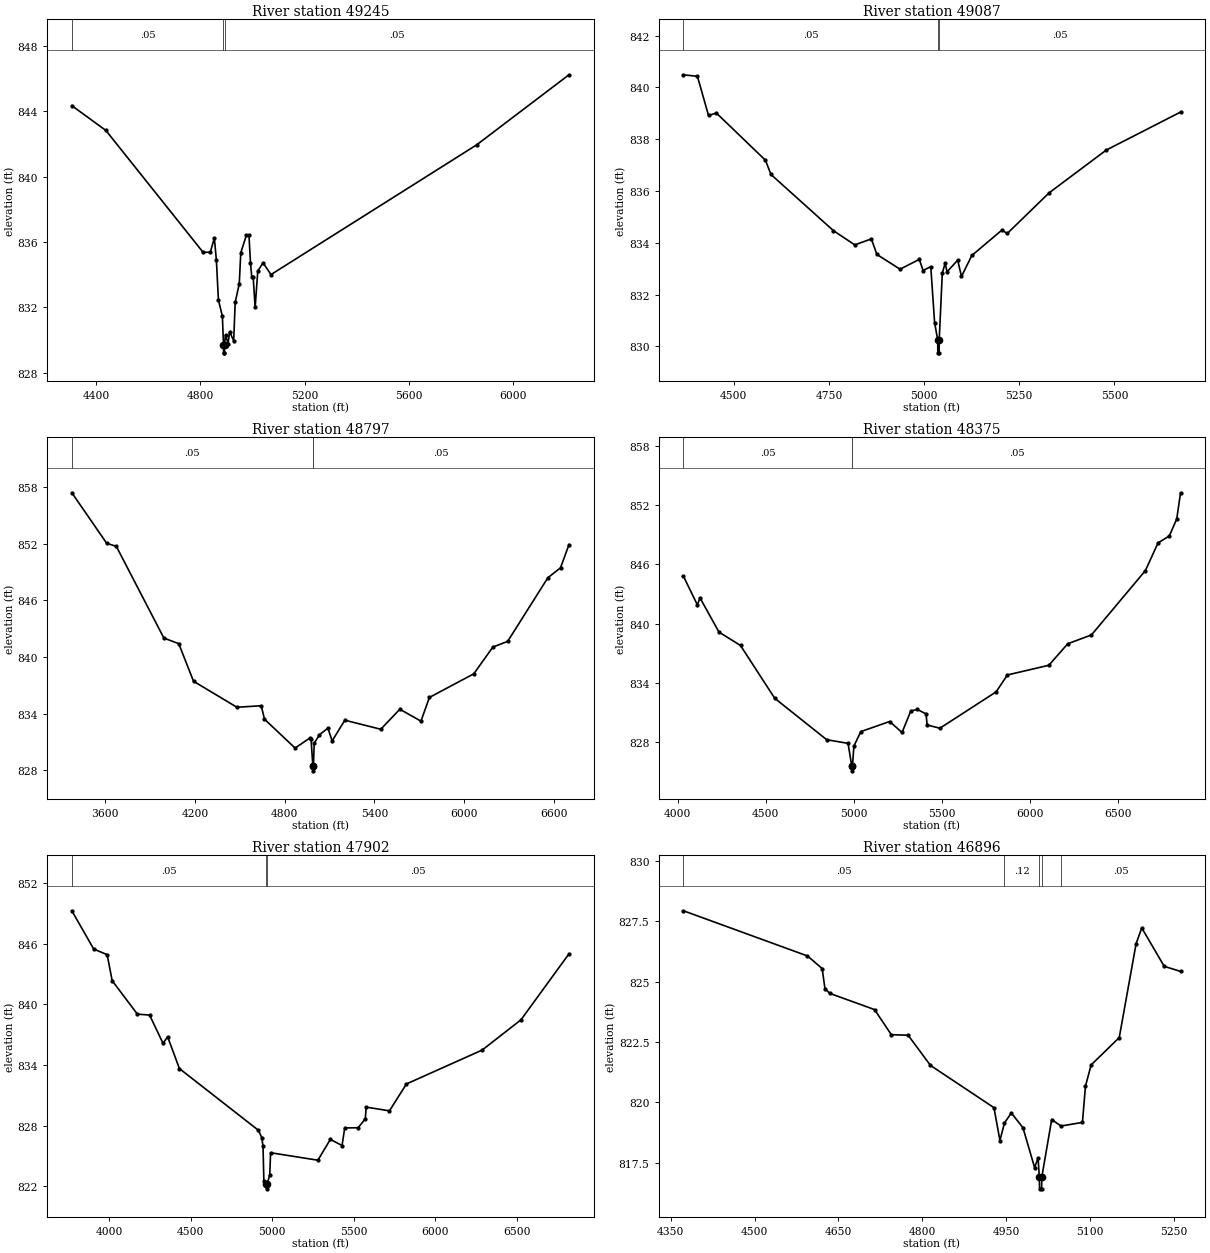
Type RM Length L Ch R = 1,49245,158,158,158
BEGIN DESCRIPTION:
Harriet Creek 90.0
END DESCRIPTION:
XS GIS Cut Line= 3
      2307328.99      7080559.98      2306979.00      7079960.00
      2305778.96      7080160.01
#Sta/Elev= 30
  4305.5  844.35  4436.5  842.83  4810.3  835.37  4838.0  835.38  4853.3  836.25
  4861.2  834.90  4869.0  832.46  4884.3  831.46  4888.5  829.72  4888.8  829.22
  4892.3  829.22  4892.5  829.72  4896.3  830.32  4906.2  829.79  4912.0  830.51
  4927.7  829.96  4933.5  832.31  4949.2  833.45  4955.0  835.35  4976.9  836.43
  4986.5  836.42  4992.2  834.74  4997.2  833.88  5002.6  833.88  5010.2  832.00
  5020.4  834.23  5040.7  834.73  5071.1  834.01  5861.8  841.95  6216.7  846.24
#Mann=3,-1,0
  4305.5    0.05       0  4888.5   0.033       0  4892.5    0.05       0
Bank Sta=4888.5,4892.5
Exp/Cntr=0.3,0.1

Type RM Length L Ch R = 1,49087,290,290,290
BEGIN DESCRIPTION:
Harriet Creek 89.5
END DESCRIPTION:
XS GIS Cut Line= 4
      2307474.51      7080276.70      2307143.76      7079844.39
      2306930.22      7079815.74      2306383.62      7079810.54
#Sta/Elev= 30
  4367.5  840.49  4404.3  840.43  4433.4  838.92  4454.2  839.01  4583.0  837.19
  4597.5  836.64  4761.6  834.47  4817.8  833.92  4861.4  834.15  4875.9  833.55
  4936.8  832.98  4987.4  833.36  4997.3  832.93  5017.5  833.08  5027.6  830.91
  5035.7  830.25  5036.0  829.75  5039.5  829.75  5039.7  830.25  5047.8  832.83
  5055.2  833.21  5060.3  832.88  5088.2  833.33  5098.2  832.70  5125.4  833.51
  5204.3  834.49  5218.5  834.36  5328.5  835.93  5478.5  837.58  5673.9  839.05
#Mann=3,-1,0
  4367.5    0.05       0  5035.7   0.033       0  5039.7    0.05       0
Bank Sta=5035.7,5039.7
Exp/Cntr=0.3,0.1

Type RM Length L Ch R = 1,48797,422,422,422
BEGIN DESCRIPTION:
Harriet Creek 89.0
END DESCRIPTION:
XS GIS Cut Line= 3
      2308328.99      7080809.99      2307229.00      7079610.00
      2306029.02      7078410.02
#Sta/Elev= 30
  3376.3  857.38  3609.7  852.03  3673.8  851.71  3992.0  842.00  4091.3  841.41
  4190.2  837.43  4480.3  834.68  4643.1  834.84  4664.7  833.42  4869.4  830.36
  4968.7  831.43  4976.1  831.34  4988.3  828.45  4988.5  827.95  4992.3  828.45
  4997.1  830.86  5032.5  831.77  5089.0  832.47  5117.3  831.12  5202.2  833.31
  5442.6  832.35  5569.9  834.47  5711.3  833.21  5767.8  835.72  6064.8  838.22
  6192.1  841.05  6291.1  841.65  6559.8  848.38  6644.7  849.44  6701.2  851.89
#Mann=3,-1,0
  3376.3    0.05       0  4988.3   0.033       0  4992.3    0.05       0
Bank Sta=4988.3,4992.3
Exp/Cntr=0.3,0.1

Type RM Length L Ch R = 1,48375,473,473,473
BEGIN DESCRIPTION:
Harriet Creek 88.0
END DESCRIPTION:
XS GIS Cut Line= 3
      2308128.99      7080259.98      2307579.00      7079460.00
      2306128.98      7078309.99
#Sta/Elev= 30
  4033.4  844.80  4112.5  841.90  4127.4  842.61  4235.0  839.15  4357.4  837.79
  4551.6  832.45  4846.4  828.26  4967.8  827.89  4988.7  825.61  4988.9  825.11
  4992.7  825.61  5001.2  827.63  5040.3  829.08  5203.7  830.10  5274.2  828.99
  5323.8  831.16  5360.7  831.32  5410.4  830.87  5416.8  829.75  5488.9  829.42
  5808.3  833.10  5872.1  834.81  6107.4  835.79  6214.8  837.97  6349.3  838.86
  6655.4  845.37  6727.2  848.17  6791.1  848.87  6833.2  850.59  6854.9  853.24
#Mann=3,-1,0
  4033.4    0.05       0  4988.7   0.033       0  4992.7    0.05       0
Bank Sta=4988.7,4992.7
Exp/Cntr=0.3,0.1

Type RM Length L Ch R = 1,47902,1006,1006,1006
BEGIN DESCRIPTION:
Harriet Creek 87.0
END DESCRIPTION:
XS GIS Cut Line= 3
      2308229.00      7080459.99      2307929.00      7079260.00
      2306328.99      7078410.00
#Sta/Elev= 30
  3771.5  849.24  3905.5  845.46  3988.0  844.90  4018.9  842.33  4173.5  839.02
  4248.2  838.93  4330.7  836.14  4359.0  836.78  4431.2  833.64  4915.7  827.54
  4936.3  826.81  4944.0  825.95  4949.2  822.49  4965.1  822.25  4965.4  821.75
  4969.3  822.25  4985.2  823.12  4990.4  825.32  5280.4  824.58  5357.0  826.64
  5428.6  826.03  5444.9  827.77  5527.1  827.79  5571.1  828.67  5576.8  829.83
  5719.3  829.46  5823.6  832.12  6288.0  835.47  6525.8  838.46  6820.2  844.98
#Mann=3,-1,0
  3771.5    0.05       0  4965.1   0.033       0  4969.3    0.05       0
Bank Sta=4965.1,4969.3
Exp/Cntr=0.3,0.1

Type RM Length L Ch R = 1,46896,174,174,174
BEGIN DESCRIPTION:
Harriet Creek 86.0
END DESCRIPTION:
XS GIS Cut Line= 4
      2308096.89      7079281.85      2308091.57      7078822.57
      2308042.20      7078646.47      2308013.78      7078401.02
#Sta/Elev= 30
  4372.7  827.93  4594.6  826.06  4620.9  825.54  4625.9  824.70  4634.6  824.51
  4714.6  823.84  4744.6  822.80  4774.6  822.78  4814.6  821.53  4928.2  819.78
  4938.9  818.42  4947.0  819.15  4959.3  819.56  4980.1  818.95  5000.9  817.30
  5007.1  817.70  5009.3  816.92  5009.8  816.42  5013.4  816.42  5013.9  816.92
  5031.5  819.29  5048.1  819.02  5086.5  819.17  5091.9  820.67  5102.0  821.55
  5152.3  822.68  5182.5  826.57  5192.6  827.22  5232.8  825.63  5262.0  825.42
#Mann=5,-1,0
  4372.7    0.05       0  4947.0    0.12       0  5009.3    0.07       0
  5013.9    0.12       0  5048.1    0.05       0
Bank Sta=5009.3,5013.9
Exp/Cntr=0.3,0.1

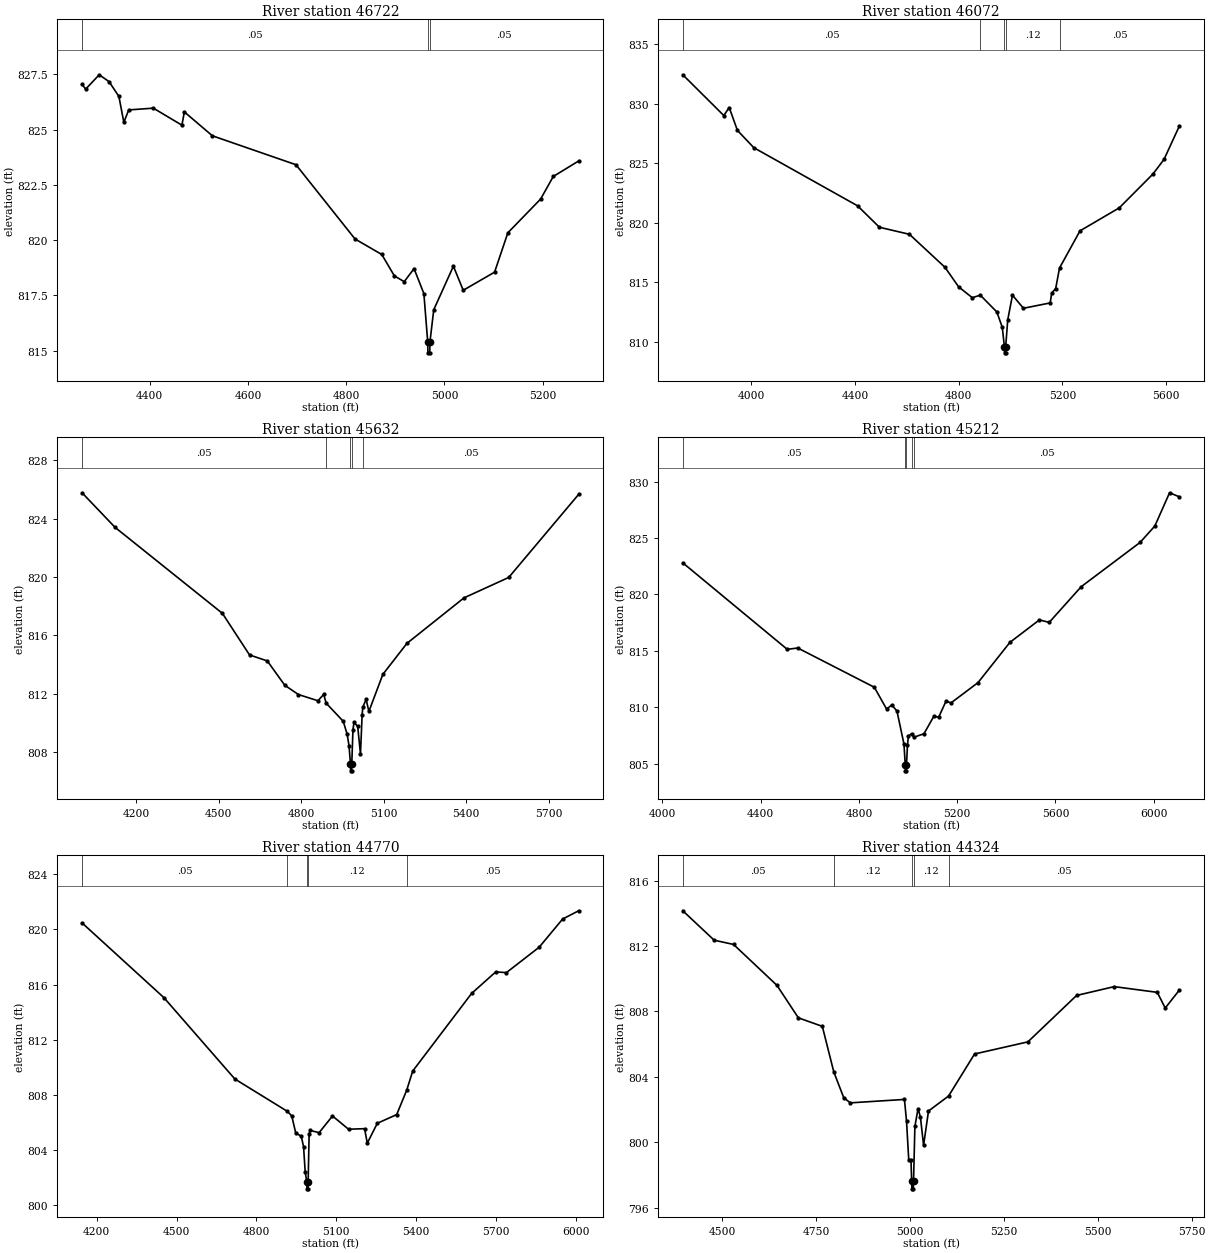
Type RM Length L Ch R = 1,46722,650,650,650
BEGIN DESCRIPTION:
Harriet Creek 85.0
END DESCRIPTION:
XS GIS Cut Line= 3
      2308143.76      7079294.89      2308185.43      7078456.37
      2308146.37      7078289.74
#Sta/Elev= 30
  4262.5  827.05  4269.8  826.83  4297.4  827.48  4317.5  827.17  4337.5  826.50
  4347.5  825.33  4357.5  825.89  4407.6  825.97  4465.7  825.20  4470.7  825.80
  4527.7  824.72  4697.9  823.41  4818.1  820.05  4872.5  819.35  4898.2  818.38
  4918.2  818.12  4938.2  818.71  4958.2  817.58  4966.0  815.40  4966.4  814.90
  4970.1  814.90  4970.6  815.40  4978.3  816.85  5018.3  818.82  5038.3  817.73
  5102.1  818.55  5129.1  820.33  5195.9  821.86  5221.6  822.88  5273.2  823.58
#Mann=3,-1,0
  4262.5    0.05       0  4966.0   0.033       0  4970.6    0.05       0
Bank Sta=4966,4970.6
Exp/Cntr=0.3,0.1

Type RM Length L Ch R = 1,46072,440,440,440
BEGIN DESCRIPTION:
Harriet Creek 84.0
END DESCRIPTION:
XS GIS Cut Line= 3
      2309079.01      7079410.04      2308679.00      7078210.00
      2308128.98      7077859.99
#Sta/Elev= 30
  3734.9  832.43  3893.1  829.01  3914.1  829.68  3945.8  827.76  4009.0  826.31
  4409.6  821.43  4493.9  819.63  4609.8  819.04  4746.9  816.27  4799.6  814.63
  4852.3  813.72  4883.4  813.93  4947.2  812.52  4968.2  811.23  4976.4  809.59
  4976.9  809.09  4980.6  809.09  4981.2  809.59  4989.3  811.87  5007.5  813.93
  5049.8  812.83  5153.1  813.28  5159.0  814.11  5174.3  814.49  5189.1  816.21
  5268.2  819.33  5419.8  821.26  5550.2  824.11  5592.5  825.33  5651.8  828.13
#Mann=5,-1,0
  3734.9    0.05       0  4883.4    0.12       0  4976.4    0.07       0
  4981.2    0.12       0  5189.1    0.05       0
Bank Sta=4976.4,4981.2
Exp/Cntr=0.3,0.1

Type RM Length L Ch R = 1,45632,420,420,420
BEGIN DESCRIPTION:
Harriet Creek 83.0
END DESCRIPTION:
XS GIS Cut Line= 3
      2309629.01      7078660.01      2308979.00      7077910.00
      2308179.02      7077760.00
#Sta/Elev= 30
  4003.1  825.77  4123.2  823.40  4513.6  817.51  4612.3  814.66  4677.0  814.25
  4740.6  812.58  4790.0  811.95  4861.2  811.52  4882.1  811.96  4891.0  811.36
  4953.3  810.11  4967.6  809.21  4974.2  808.45  4979.4  807.22  4980.0  806.72
  4983.7  806.72  4984.3  807.22  4988.5  809.52  4992.3  810.05  5005.8  809.76
  5015.9  807.87  5021.9  810.57  5024.6  811.09  5036.3  811.62  5046.5  810.79
  5097.3  813.33  5184.7  815.45  5392.4  818.57  5555.2  819.97  5809.5  825.66
#Mann=5,-1,0
  4003.1    0.05       0  4891.0    0.12       0  4979.4    0.07       0
  4984.3    0.12       0  5024.6    0.05       0
Bank Sta=4979.4,4984.3
Exp/Cntr=0.3,0.1

Type RM Length L Ch R = 1,45212,442,442,442
BEGIN DESCRIPTION:
Harriet Creek 82.0
END DESCRIPTION:
XS GIS Cut Line= 3
      2309879.00      7078160.00      2309179.00      7077560.00
      2308078.96      7077560.00
#Sta/Elev= 30
  4082.7  822.80  4508.0  815.13  4550.8  815.25  4862.5  811.77  4912.5  809.84
  4933.9  810.20  4954.7  809.66  4983.3  806.73  4988.5  804.86  4989.1  804.36
  4992.8  804.36  4993.4  804.86  4997.5  806.63  5001.4  807.44  5014.1  807.65
  5024.0  807.34  5064.7  807.65  5104.7  809.19  5124.7  809.12  5154.7  810.55
  5174.7  810.38  5284.7  812.18  5414.7  815.75  5534.7  817.74  5574.7  817.52
  5704.7  820.68  5944.7  824.61  6004.7  826.06  6064.7  829.01  6104.7  828.65
#Mann=5,-1,0
  4082.7    0.05       0  4988.5   0.035       0  4993.4    0.05       0
  5014.1    0.12       0  5024.0    0.05       0
Bank Sta=4988.5,4993.4
Exp/Cntr=0.3,0.1

Type RM Length L Ch R = 1,44770,446,446,446
BEGIN DESCRIPTION:
Harriet Creek 81.0
END DESCRIPTION:
XS GIS Cut Line= 3
      2309929.00      7077910.00      2309429.00      7077210.00
      2308429.01      7077310.00
#Sta/Elev= 30
  4145.1  820.47  4452.3  815.06  4719.0  809.16  4916.6  806.81  4932.8  806.48
  4947.6  805.25  4968.5  805.01  4977.1  804.25  4983.2  802.42  4989.3  801.70
  4990.0  801.20  4993.7  801.20  4994.3  801.70  4998.0  805.20  5002.3  805.43
  5035.5  805.27  5085.7  806.48  5146.0  805.52  5206.3  805.56  5216.4  804.51
  5254.1  805.95  5326.9  806.58  5364.5  808.35  5387.2  809.74  5608.3  815.36
  5698.8  816.92  5739.0  816.87  5862.1  818.71  5950.0  820.75  6010.3  821.35
#Mann=5,-1,0
  4145.1    0.05       0  4916.6    0.12       0  4989.3    0.07       0
  4994.3    0.12       0  5364.5    0.05       0
Bank Sta=4989.3,4994.3
Exp/Cntr=0.3,0.1

Type RM Length L Ch R = 1,44324,660,660,660
BEGIN DESCRIPTION:
Harriet Creek 80.0
END DESCRIPTION:
XS GIS Cut Line= 3
      2309979.01      7077460.03      2309729.00      7076910.00
      2309151.66      7076484.14
#Sta/Elev= 30
  4395.8  814.16  4479.3  812.36  4530.9  812.10  4646.3  809.60  4703.4  807.61
  4767.1  807.09  4797.7  804.30  4824.2  802.72  4841.8  802.41  4985.7  802.62
  4991.2  801.30  4997.2  798.90  5003.1  798.90  5004.8  797.65  5005.4  797.15
  5009.2  797.15  5009.9  797.65  5013.5  800.97  5021.9  802.06  5028.2  801.54
  5036.6  799.81  5049.7  801.91  5103.2  802.83  5172.3  805.40  5314.2  806.14
  5443.8  808.98  5544.0  809.52  5658.6  809.17  5679.7  808.21  5717.4  809.31
#Mann=5,-1,0
  4395.8    0.05       0  4797.7    0.12       0  5004.8    0.07       0
  5009.9    0.12       0  5103.2    0.05       0
Bank Sta=5004.8,5009.9
Exp/Cntr=0.3,0.1

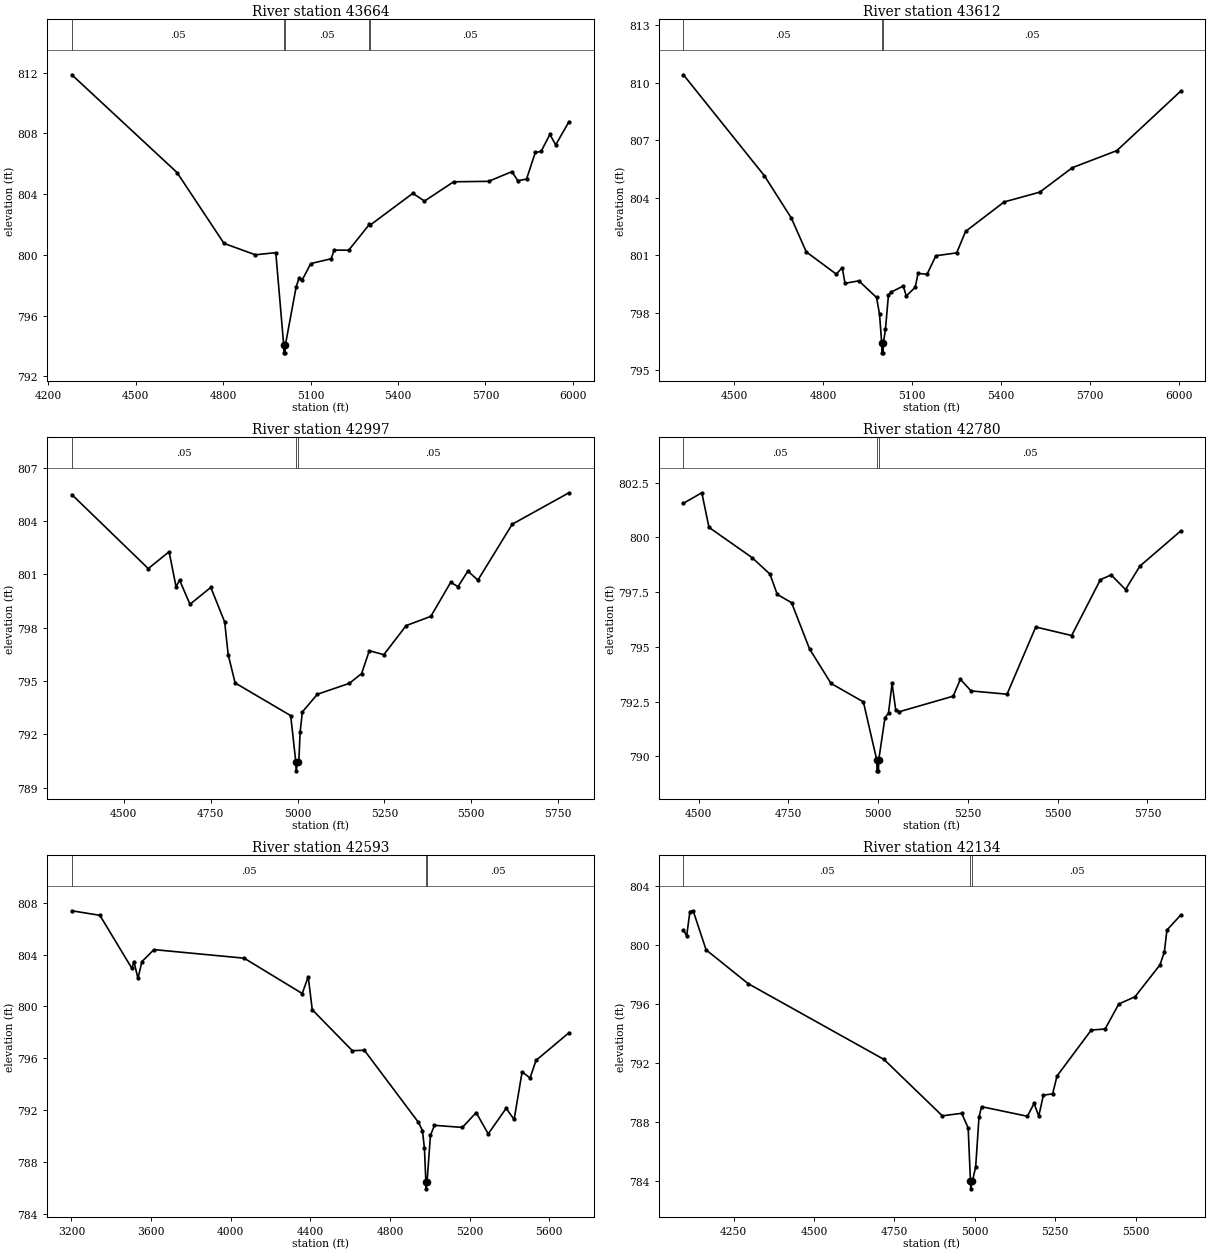
Type RM Length L Ch R = 1,43664,52,52,52
BEGIN DESCRIPTION:
Harriet Creek 79.0
END DESCRIPTION:
XS GIS Cut Line= 3
      2310363.60      7077058.36      2310294.15      7076468.09
      2309183.50      7076470.25
#Sta/Elev= 30
  4281.4  811.86  4642.2  805.42  4803.3  800.75  4910.9  800.00  4980.9  800.14
  5008.1  794.04  5008.9  793.54  5012.8  793.54  5013.6  794.04  5050.9  797.90
  5060.9  798.46  5070.9  798.32  5100.9  799.42  5170.9  799.74  5180.9  800.31
  5230.9  800.30  5301.8  802.00  5304.2  801.95  5450.9  804.05  5490.9  803.54
  5590.9  804.81  5710.9  804.84  5790.9  805.48  5810.9  804.88  5840.9  804.99
  5870.9  806.74  5890.9  806.81  5920.9  807.93  5940.9  807.24  5986.4  808.77
#Mann=5,-1,0
  4281.4    0.05       0  5008.1   0.033       0  5013.6    0.05       0
  5301.8    0.12       0  5304.2    0.05       0
Bank Sta=5008.1,5013.6
Exp/Cntr=0.3,0.1

Type RM Length L Ch R = 1,43612,615,615,615
BEGIN DESCRIPTION:
Harriet Creek 78.0
END DESCRIPTION:
XS GIS Cut Line= 3
      2310379.01      7076960.04      2310301.40      7076416.83
      2309174.35      7076422.51
#Sta/Elev= 30
  4329.0  810.42  4601.8  805.15  4692.7  802.94  4743.2  801.17  4844.2  800.01
  4864.4  800.35  4873.6  799.53  4920.1  799.66  4980.1  798.79  4990.1  797.91
  4997.4  796.40  4998.2  795.90  5002.1  795.90  5002.9  796.40  5010.1  797.14
  5020.1  798.92  5030.1  799.08  5070.1  799.39  5080.1  798.87  5110.1  799.32
  5120.1  800.05  5150.1  800.00  5180.1  800.97  5250.1  801.12  5280.1  802.24
  5410.1  803.78  5530.1  804.29  5640.1  805.57  5790.1  806.46  6004.8  809.56
#Mann=3,-1,0
  4329.0    0.05       0  4997.4   0.033       0  5002.9    0.05       0
Bank Sta=4997.4,5002.9
Exp/Cntr=0.3,0.1

Type RM Length L Ch R = 1,42997,217,217,217
BEGIN DESCRIPTION:
Harriet Creek 77.0
END DESCRIPTION:
XS GIS Cut Line= 3
      2310629.00      7076710.02      2310629.00      7076060.00
      2310029.04      7075560.03
#Sta/Elev= 30
  4350.3  805.50  4570.3  801.33  4630.3  802.28  4650.3  800.30  4660.3  800.69
  4690.3  799.32  4750.3  800.27  4790.3  798.32  4800.3  796.49  4820.3  794.89
  4980.3  793.05  4995.0  790.44  4995.9  789.94  5000.6  790.44  5003.6  790.44
  5007.5  792.14  5014.0  793.26  5056.9  794.25  5149.4  794.87  5184.5  795.42
  5206.6  796.71  5248.3  796.48  5312.7  798.12  5383.7  798.64  5441.0  800.56
  5461.8  800.31  5490.4  801.19  5519.1  800.68  5618.0  803.83  5781.3  805.60
#Mann=3,-1,0
  4350.3    0.05       0  4995.0   0.035       0  5000.6    0.05       0
Bank Sta=4995,5000.6
Exp/Cntr=0.3,0.1

Type RM Length L Ch R = 1,42780,187,187,187
BEGIN DESCRIPTION:
Harriet Creek 76.5
END DESCRIPTION:
XS GIS Cut Line= 2
      2310805.06      7076481.23      2310793.30      7075096.68
#Sta/Elev= 30
  4457.6  801.56  4508.8  802.04  4528.8  800.46  4648.8  799.08  4698.8  798.32
  4718.8  797.40  4758.8  797.02  4808.8  794.91  4868.8  793.33  4958.8  792.49
  4996.0  789.84  4996.9  789.34  5000.8  789.34  5001.6  789.84  5018.8  791.75
  5028.8  791.99  5038.8  793.34  5048.8  792.12  5058.8  792.04  5208.9  792.75
  5228.9  793.52  5258.9  792.99  5358.9  792.84  5438.9  795.91  5538.9  795.52
  5618.9  798.07  5648.9  798.29  5688.9  797.62  5728.9  798.69  5842.2  800.29
#Mann=3,-1,0
  4457.6    0.05       0  4996.0   0.033       0  5001.6    0.05       0
Bank Sta=4996,5001.6
Exp/Cntr=0.3,0.1

Type RM Length L Ch R = 1,42593,459,459,459
BEGIN DESCRIPTION:
Harriet Creek 76.0
END DESCRIPTION:
XS GIS Cut Line= 3
      2311129.00      7077609.97      2310929.00      7075810.00
      2310944.29      7075124.62
#Sta/Elev= 30
  3201.9  807.37  3342.7  807.02  3503.7  802.93  3513.8  803.46  3533.9  802.16
  3554.0  803.46  3614.4  804.38  4067.2  803.72  4358.9  801.00  4389.1  802.29
  4409.3  799.75  4610.5  796.60  4670.9  796.63  4942.5  791.08  4962.6  790.45
  4972.7  789.08  4979.9  786.46  4980.8  785.96  4985.6  786.46  5002.9  790.08
  5023.0  790.85  5163.0  790.69  5232.6  791.83  5293.0  790.19  5383.0  792.16
  5423.1  791.30  5463.1  794.96  5503.1  794.50  5533.1  795.85  5698.5  797.98
#Mann=3,-1,0
  3201.9    0.05       0  4979.9   0.033       0  4985.6    0.05       0
Bank Sta=4979.9,4985.6
Exp/Cntr=0.3,0.1

Type RM Length L Ch R = 1,42134,467,467,467
BEGIN DESCRIPTION:
Harriet Creek 75.0
END DESCRIPTION:
XS GIS Cut Line= 3
      2311179.00      7076460.03      2311279.00      7075560.00
      2310878.99      7075059.98
#Sta/Elev= 30
  4094.2  801.02  4104.3  800.62  4114.4  802.27  4124.4  802.32  4164.7  799.67
  4295.5  797.38  4718.0  792.24  4899.2  788.42  4959.5  788.59  4979.6  787.60
  4986.8  783.97  4987.7  783.47  4992.6  783.97  5003.0  784.96  5013.4  788.35
  5021.4  789.04  5163.8  788.39  5184.7  789.26  5199.1  788.40  5213.5  789.82
  5242.3  789.91  5255.9  791.12  5362.3  794.23  5405.6  794.31  5448.0  796.00
  5498.4  796.49  5576.0  798.65  5589.7  799.53  5597.7  801.01  5640.1  802.02
#Mann=3,-1,0
  4094.2    0.05       0  4986.8   0.033       0  4992.6    0.05       0
Bank Sta=4986.8,4992.6
Exp/Cntr=0.3,0.1

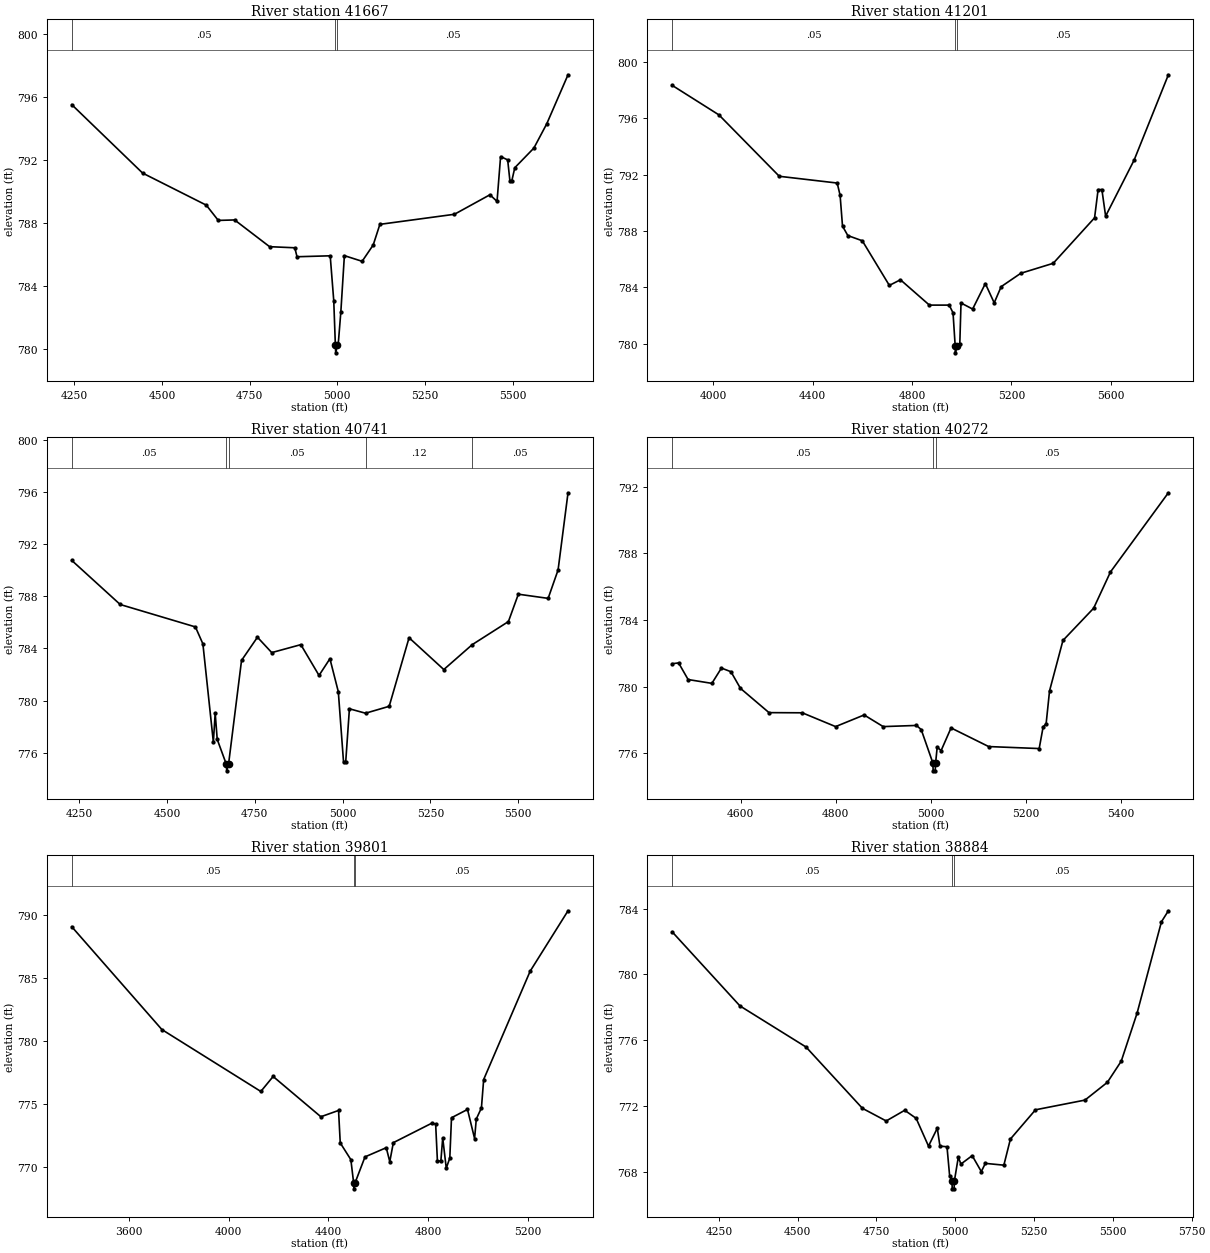
Type RM Length L Ch R = 1,41667,466,466,466
BEGIN DESCRIPTION:
Harriet Creek 74.0
END DESCRIPTION:
XS GIS Cut Line= 3
      2311578.99      7076160.05      2311679.00      7075410.00
      2311579.01      7074760.03
#Sta/Elev= 30
  4243.2  795.53  4445.0  791.18  4626.6  789.14  4660.7  788.17  4707.3  788.20
  4806.9  786.50  4878.8  786.43  4885.1  785.86  4979.7  785.92  4989.8  783.07
  4994.4  780.25  4995.4  779.75  5000.3  780.25  5002.4  780.25  5010.0  782.35
  5020.1  785.93  5070.7  785.57  5102.3  786.61  5121.3  787.92  5333.8  788.56
  5434.9  789.80  5455.2  789.38  5465.3  792.23  5485.5  792.02  5491.9  790.68
  5496.9  790.65  5505.8  791.52  5560.2  792.77  5596.8  794.31  5657.5  797.43
#Mann=3,-1,0
  4243.2    0.05       0  4994.4   0.033       0  5000.3    0.05       0
Bank Sta=4994.4,5000.3
Exp/Cntr=0.3,0.1

Type RM Length L Ch R = 1,41201,460,460,460
BEGIN DESCRIPTION:
Harriet Creek 73.0
END DESCRIPTION:
XS GIS Cut Line= 3
      2311528.99      7076360.01      2312129.00      7075360.00
      2311678.98      7074659.97
#Sta/Elev= 30
  3833.8  798.34  4022.3  796.24  4265.3  791.88  4498.5  791.40  4510.2  790.53
  4519.9  788.34  4541.3  787.67  4599.6  787.30  4708.5  784.13  4753.2  784.53
  4869.8  782.73  4949.5  782.73  4965.0  782.18  4973.6  779.84  4974.6  779.34
  4979.7  779.84  4992.2  779.95  4997.1  782.88  5043.9  782.45  5095.1  784.26
  5130.8  782.89  5158.8  784.04  5237.8  784.99  5368.5  785.70  5535.0  788.93
  5549.2  790.93  5564.4  790.94  5579.5  789.05  5694.5  793.04  5832.2  799.09
#Mann=3,-1,0
  3833.8    0.05       0  4973.6   0.033       0  4979.7    0.05       0
Bank Sta=4973.6,4979.7
Exp/Cntr=0.3,0.1

Type RM Length L Ch R = 1,40741,469,469,469
BEGIN DESCRIPTION:
Harriet Creek 72.0
END DESCRIPTION:
XS GIS Cut Line= 3
      2312329.00      7075910.00      2312529.00      7075160.00
      2312079.00      7074710.00
#Sta/Elev= 30
  4229.3  790.75  4367.1  787.37  4581.2  785.65  4602.5  784.35  4632.3  776.81
  4637.5  779.03  4643.3  777.02  4669.3  775.11  4670.3  774.61  4675.5  775.11
  4712.5  783.08  4757.8  784.86  4798.5  783.68  4881.3  784.29  4933.1  781.93
  4964.1  783.21  4988.0  780.68  5002.9  775.27  5009.0  775.27  5019.6  779.37
  5065.5  779.03  5132.8  779.56  5189.4  784.82  5288.3  782.38  5369.2  784.29
  5472.2  786.06  5500.5  788.16  5585.3  787.84  5613.6  790.02  5641.9  795.94
#Mann=5,-1,0
  4229.3    0.05       0  4669.3   0.033       0  4675.5    0.05       0
  5065.5    0.12       0  5369.2    0.05       0
Bank Sta=4669.3,4675.5
Exp/Cntr=0.3,0.1

Type RM Length L Ch R = 1,40272,471,471,471
BEGIN DESCRIPTION:
Harriet Creek 71.0
END DESCRIPTION:
XS GIS Cut Line= 3
      2312856.28      7075453.57      2312879.00      7074910.00
      2312579.03      7074510.04
#Sta/Elev= 30
  4456.0  781.37  4469.6  781.42  4489.6  780.42  4539.6  780.19  4559.7  781.11
  4579.7  780.89  4599.7  779.89  4659.8  778.43  4729.8  778.42  4799.9  777.59
  4859.9  778.29  4900.0  777.59  4970.0  777.66  4980.0  777.41  5004.2  775.43
  5005.3  774.93  5009.4  774.93  5010.4  775.43  5013.6  776.35  5021.9  776.15
  5042.8  777.51  5121.9  776.39  5228.2  776.27  5236.5  777.57  5242.8  777.76
  5250.0  779.74  5278.2  782.77  5342.8  784.71  5378.2  786.89  5500.0  791.65
#Mann=3,-1,0
  4456.0    0.05       0  5004.2   0.033       0  5010.4    0.05       0
Bank Sta=5004.2,5010.4
Exp/Cntr=0.3,0.1

Type RM Length L Ch R = 1,39801,917,917,917
BEGIN DESCRIPTION:
Harriet Creek 70.0
END DESCRIPTION:
XS GIS Cut Line= 3
      2314278.98      7075809.98      2313179.00      7074610.00
      2312979.00      7074310.01
#Sta/Elev= 30
  3371.9  789.08  3732.9  780.91  4129.4  775.99  4178.7  777.18  4369.9  773.98
  4440.8  774.48  4447.6  771.90  4490.1  770.57  4501.1  768.75  4502.1  768.25
  4507.4  768.75  4546.8  770.79  4631.9  771.52  4646.1  770.41  4660.3  771.92
  4815.7  773.48  4829.9  773.39  4837.0  770.45  4850.8  770.47  4858.2  772.30
  4872.4  769.89  4886.6  770.70  4893.4  773.90  4957.5  774.56  4985.9  772.25
  4992.7  773.80  5013.3  774.68  5022.3  776.94  5208.6  785.55  5360.3  790.35
#Mann=3,-1,0
  3371.9    0.05       0  4501.1   0.033       0  4507.4    0.05       0
Bank Sta=4501.1,4507.4
Exp/Cntr=0.3,0.1

Type RM Length L Ch R = 1,38884,418,418,418
BEGIN DESCRIPTION:
Harriet Creek 69.0
END DESCRIPTION:
XS GIS Cut Line= 3
      2314229.00      7075559.99      2313829.00      7074760.00
      2313278.99      7074359.99
#Sta/Elev= 30
  4101.6  782.59  4316.8  778.08  4526.4  775.58  4705.3  771.85  4780.8  771.08
  4839.5  771.73  4875.8  771.24  4915.0  769.55  4942.9  770.64  4951.3  769.55
  4973.7  769.51  4982.0  767.75  4989.2  767.45  4990.4  766.95  4996.1  766.95
  4997.3  767.45  5009.5  768.87  5018.0  768.46  5053.6  768.97  5082.6  768.00
  5095.3  768.50  5154.1  768.39  5174.9  769.98  5254.5  771.76  5411.4  772.35
  5482.5  773.43  5526.6  774.72  5576.8  777.64  5654.1  783.20  5676.1  783.87
#Mann=3,-1,0
  4101.6    0.05       0  4989.2   0.033       0  4997.3    0.05       0
Bank Sta=4989.2,4997.3
Exp/Cntr=0.3,0.1