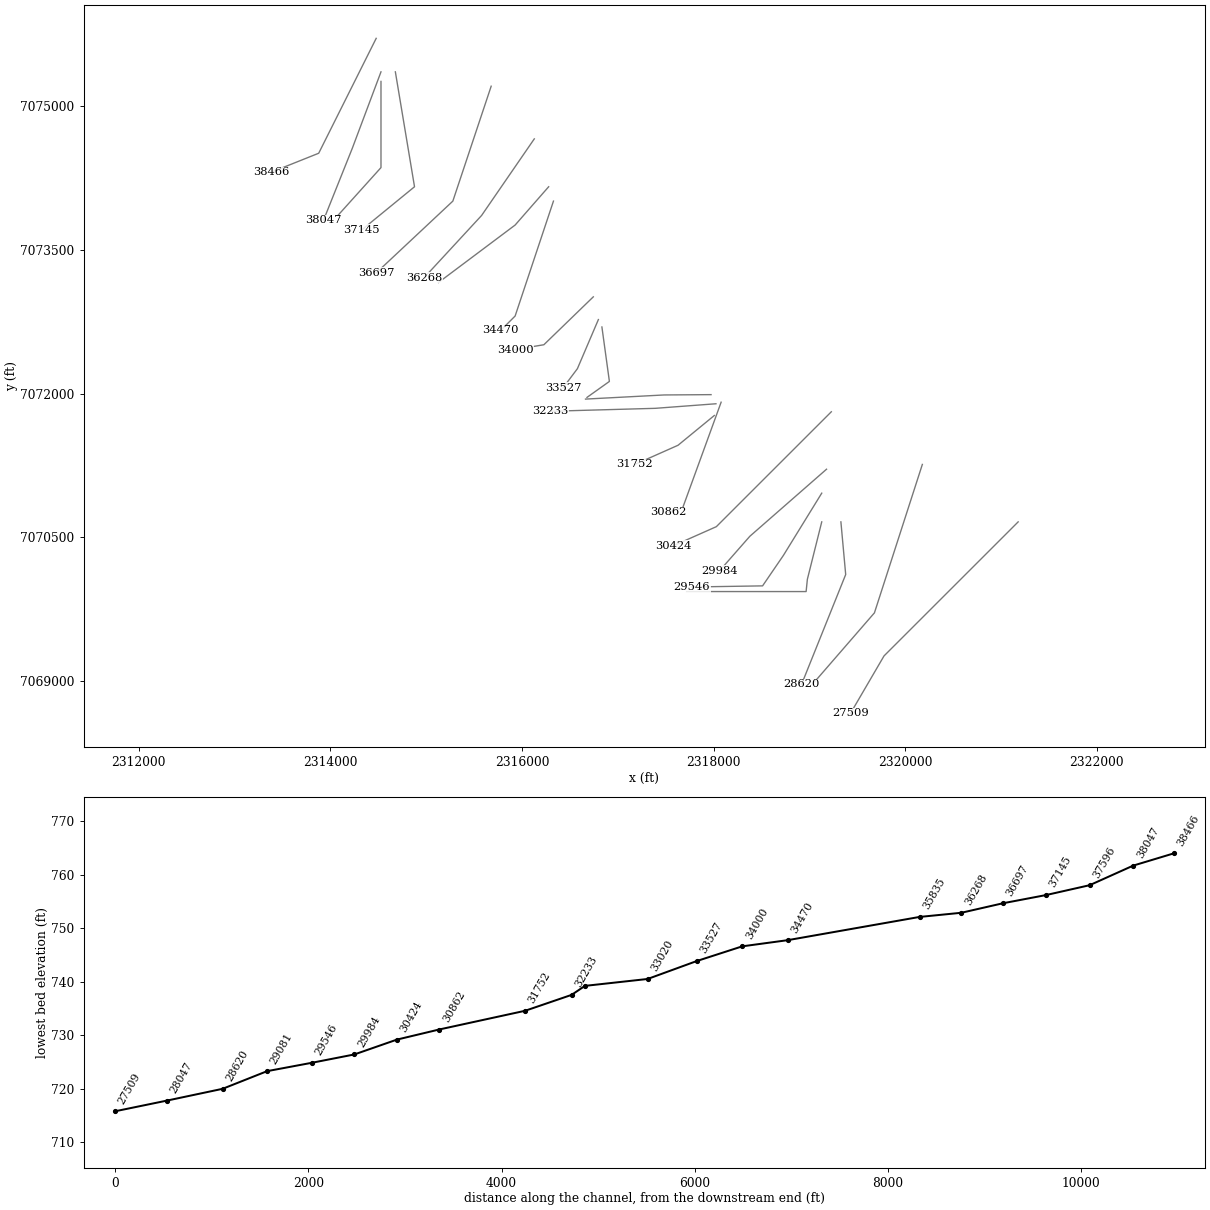
HEC-RAS study Harriet Creek.prj: Harriet Creek Base Level Engineering

--- Harriet Creek.g01 (geometry) --- (continued)

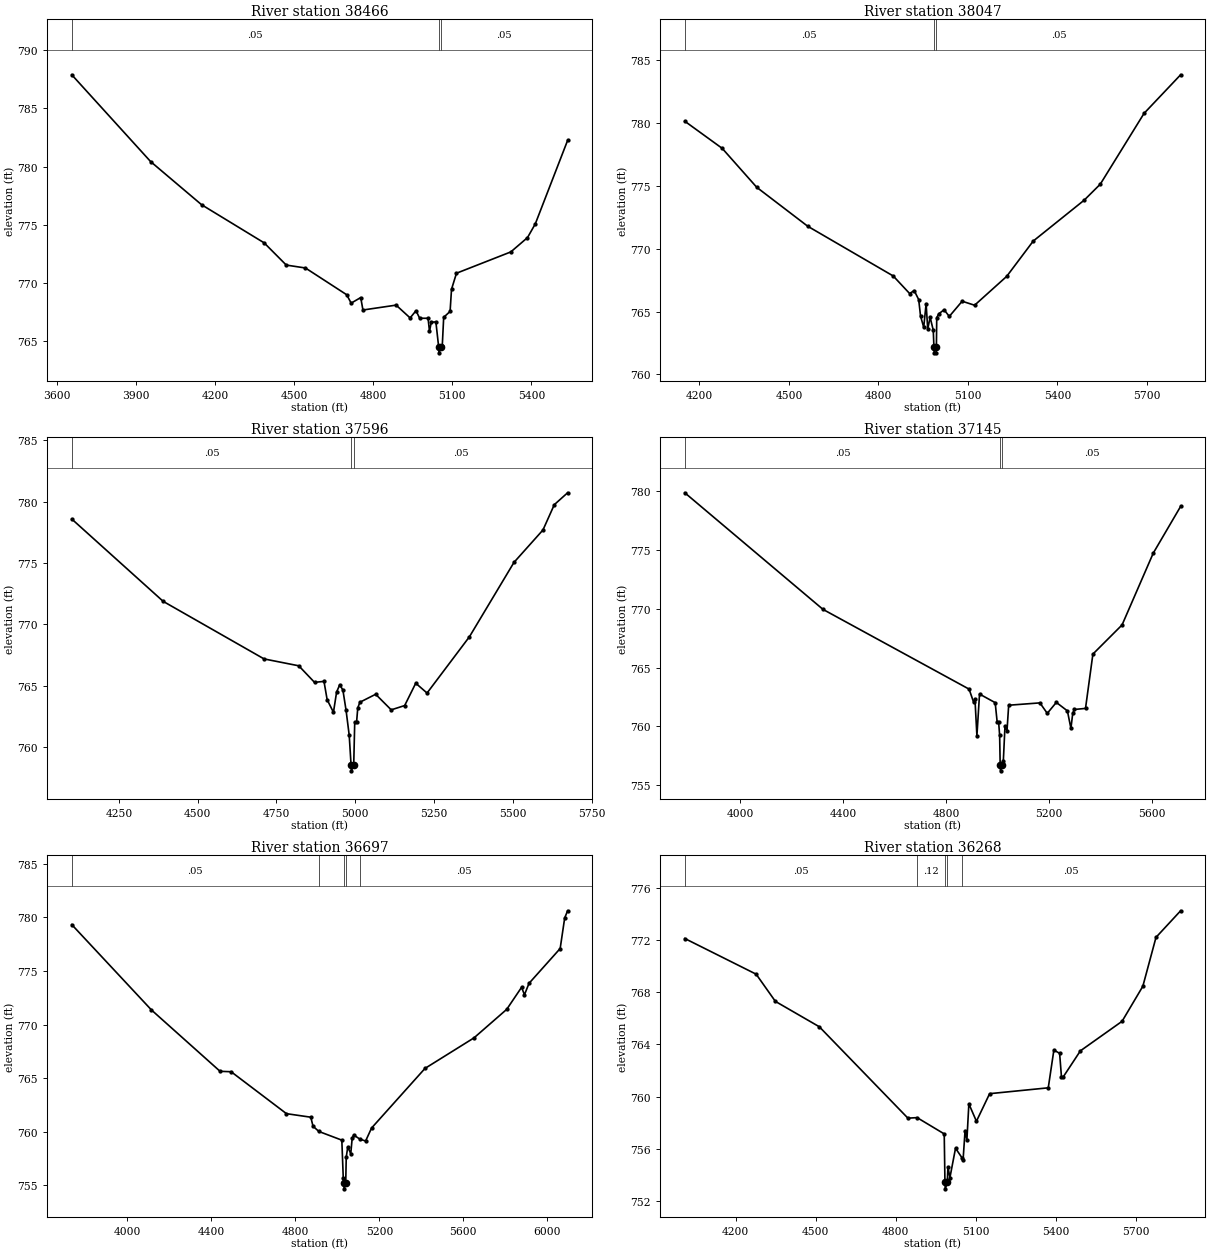
Type RM Length L Ch R = 1,38466,419,419,419
BEGIN DESCRIPTION:
Harriet Creek 68.0
END DESCRIPTION:
XS GIS Cut Line= 3
      2314479.01      7075710.03      2313879.00      7074510.00
      2313378.99      7074310.00
#Sta/Elev= 30
  3657.1  787.89  3956.2  780.43  4149.1  776.73  4386.6  773.45  4470.5  771.54
  4543.2  771.29  4699.7  768.99  4716.5  768.27  4752.8  768.75  4761.2  767.68
  4887.0  768.10  4940.1  767.00  4962.4  767.62  4976.4  766.97  5008.2  766.97
  5013.6  765.84  5020.3  766.63  5037.8  766.66  5048.4  764.50  5049.7  764.00
  5056.8  764.50  5062.0  764.59  5067.4  767.05  5091.7  767.56  5097.1  769.46
  5115.9  770.84  5321.9  772.67  5385.2  773.90  5414.8  775.08  5537.3  782.25
#Mann=3,-1,0
  3657.1    0.05       0  5048.4   0.033       0  5056.8    0.05       0
Bank Sta=5048.4,5056.8
Exp/Cntr=0.3,0.1

Type RM Length L Ch R = 1,38047,451,451,451
BEGIN DESCRIPTION:
Harriet Creek 67.0
END DESCRIPTION:
XS GIS Cut Line= 3
      2314529.00      7075360.01      2314229.00      7074560.00
      2313928.99      7073809.98
#Sta/Elev= 30
  4150.7  780.16  4276.2  778.00  4391.9  774.90  4562.8  771.80  4849.4  767.84
  4904.5  766.44  4919.7  766.68  4934.8  765.96  4941.0  764.65  4951.7  763.75
  4959.7  765.64  4965.1  763.61  4973.1  764.55  4983.7  763.52  4985.8  762.22
  4987.0  761.72  4993.0  761.72  4994.2  762.22  4995.3  764.52  5002.4  764.83
  5019.9  765.15  5037.4  764.62  5080.5  765.83  5122.2  765.51  5229.9  767.81
  5318.8  770.62  5489.8  773.88  5543.6  775.15  5690.4  780.79  5812.9  783.86
#Mann=3,-1,0
  4150.7    0.05       0  4985.8   0.033       0  4994.2    0.05       0
Bank Sta=4985.8,4994.2
Exp/Cntr=0.3,0.1

Type RM Length L Ch R = 1,37596,451,451,451
BEGIN DESCRIPTION:
Harriet Creek 66.0
END DESCRIPTION:
XS GIS Cut Line= 3
      2314529.00      7075260.01      2314529.00      7074360.00
      2314079.00      7073860.00
#Sta/Elev= 30
  4100.7  778.58  4390.7  771.87  4710.7  767.18  4820.7  766.62  4870.7  765.27
  4900.7  765.35  4910.7  763.86  4930.7  762.83  4940.7  764.48  4950.7  765.08
  4960.7  764.64  4970.7  763.00  4980.7  760.96  4986.5  758.56  4987.7  758.06
  4995.0  758.56  4998.2  762.03  5004.1  762.03  5007.8  763.18  5014.5  763.65
  5064.6  764.30  5113.9  763.03  5156.6  763.38  5191.7  765.20  5227.6  764.40
  5362.1  768.99  5503.4  775.05  5595.3  777.69  5631.2  779.75  5673.4  780.72
#Mann=3,-1,0
  4100.7    0.05       0  4986.5   0.033       0  4995.0    0.05       0
Bank Sta=4986.5,4995
Exp/Cntr=0.3,0.1

Type RM Length L Ch R = 1,37145,448,448,448
BEGIN DESCRIPTION:
Harriet Creek 65.0
END DESCRIPTION:
XS GIS Cut Line= 3
      2314679.01      7075359.97      2314879.00      7074160.00
      2314328.96      7073709.97
#Sta/Elev= 30
  3783.8  779.87  4321.1  769.95  4888.8  763.17  4906.5  762.05  4911.6  762.34
  4919.2  759.20  4929.4  762.75  4990.2  762.02  4997.8  760.40  5003.5  760.40
  5007.5  759.26  5009.7  756.72  5010.9  756.22  5018.3  756.72  5021.9  757.06
  5028.3  760.01  5036.2  759.64  5042.7  761.80  5164.0  762.00  5192.7  761.11
  5227.9  762.04  5270.9  761.32  5284.6  759.83  5291.7  761.12  5298.2  761.44
  5341.3  761.53  5370.0  766.15  5483.4  768.63  5604.7  774.74  5711.0  778.71
#Mann=3,-1,0
  3783.8    0.05       0  5009.7   0.033       0  5018.3    0.05       0
Bank Sta=5009.7,5018.3
Exp/Cntr=0.3,0.1

Type RM Length L Ch R = 1,36697,429,429,429
BEGIN DESCRIPTION:
Harriet Creek 64.0
END DESCRIPTION:
XS GIS Cut Line= 3
      2315679.01      7075210.02      2315279.00      7074010.00
      2314479.01      7073260.01
#Sta/Elev= 30
  3735.1  779.32  4114.6  771.36  4441.4  765.64  4494.1  765.60  4757.6  761.69
  4873.5  761.36  4884.1  760.52  4912.0  760.03  5021.3  759.22  5028.1  755.71
  5031.0  755.18  5032.3  754.68  5039.8  755.18  5042.3  757.63  5049.6  758.59
  5063.8  757.95  5070.6  759.40  5077.9  759.70  5107.7  759.31  5134.6  759.14
  5162.9  760.35  5417.4  765.91  5650.9  768.76  5806.7  771.42  5877.3  773.47
  5891.2  772.78  5912.7  773.84  6061.2  777.09  6082.7  779.94  6096.6  780.61
#Mann=5,-1,0
  3735.1    0.05       0  4912.0    0.12       0  5031.0    0.07       0
  5039.8    0.12       0  5107.7    0.05       0
Bank Sta=5031,5039.8
Exp/Cntr=0.3,0.1

Type RM Length L Ch R = 1,36268,433,433,433
BEGIN DESCRIPTION:
Harriet Creek 63.0
END DESCRIPTION:
XS GIS Cut Line= 3
      2316129.01      7074660.01      2315579.00      7073860.00
      2314979.02      7073210.02
#Sta/Elev= 30
  4010.2  772.14  4277.2  769.40  4349.2  767.31  4513.6  765.36  4845.1  758.34
  4879.5  758.38  4981.0  757.13  4983.7  753.41  4985.0  752.91  4992.5  753.41
  4994.9  754.60  5002.3  753.77  5023.3  756.03  5047.6  755.29  5051.6  755.15
  5059.0  757.38  5065.8  756.65  5073.2  759.44  5101.5  758.10  5150.9  760.22
  5370.3  760.67  5391.3  763.57  5412.8  763.32  5419.7  761.51  5427.0  761.53
  5490.5  763.51  5646.5  765.78  5724.2  768.47  5773.5  772.23  5865.6  774.27
#Mann=5,-1,0
  4010.2    0.05       0  4879.5    0.12       0  4983.7    0.07       0
  4992.5    0.12       0  5047.6    0.05       0
Bank Sta=4983.7,4992.5
Exp/Cntr=0.3,0.1

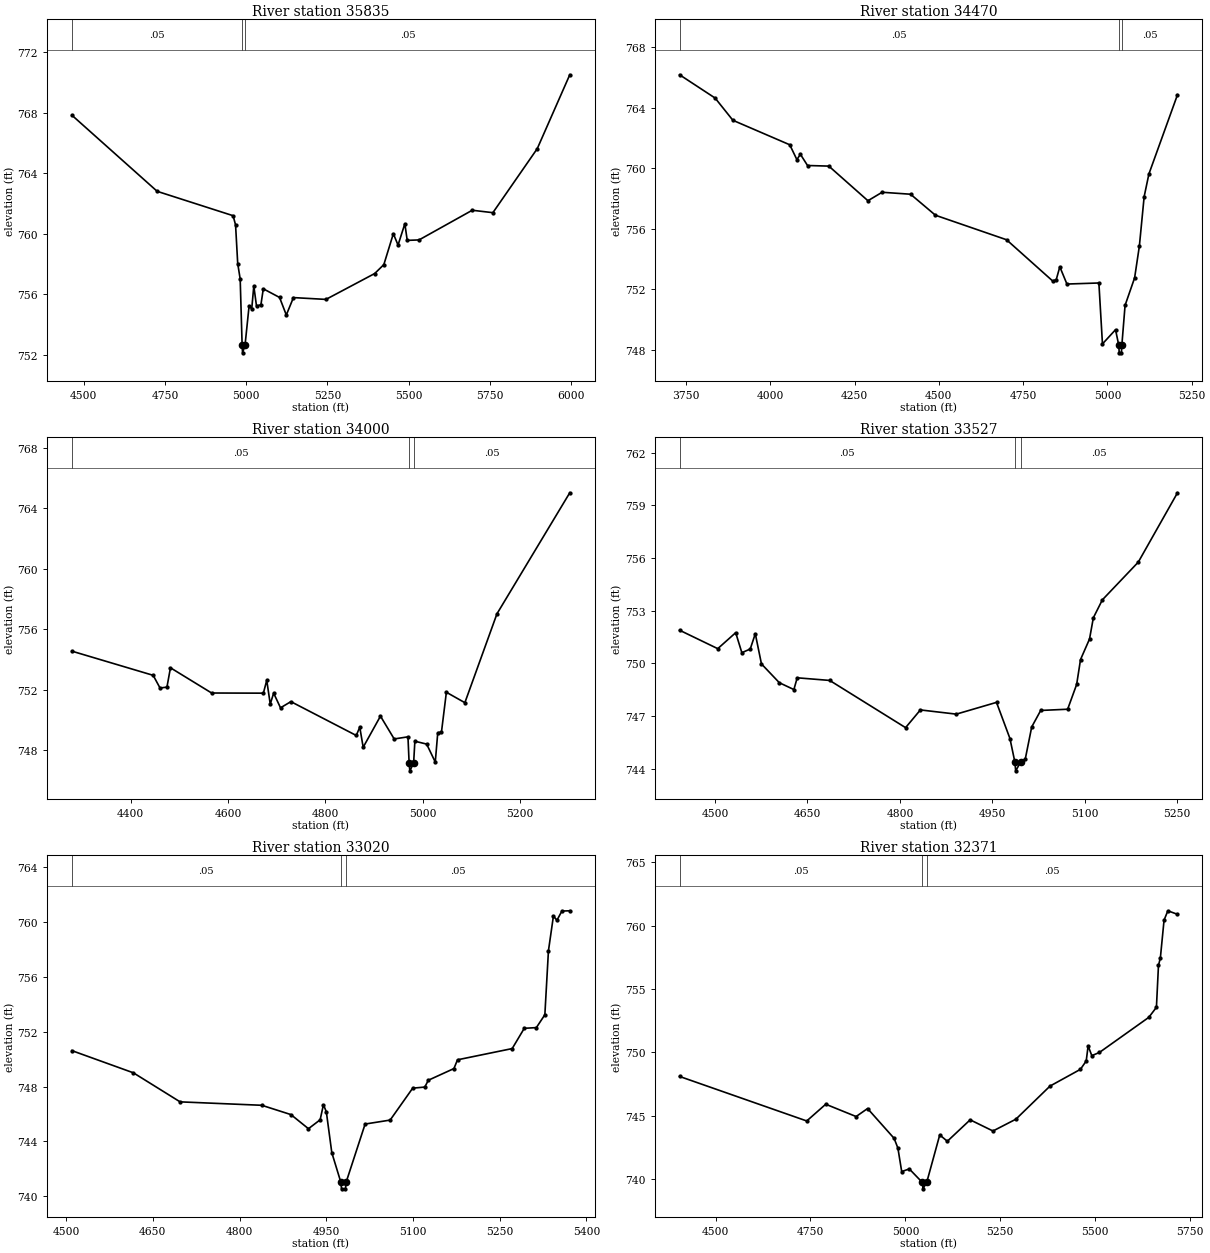
Type RM Length L Ch R = 1,35835,1365,1365,1365
BEGIN DESCRIPTION:
Harriet Creek 62.0
END DESCRIPTION:
XS GIS Cut Line= 3
      2316278.97      7074159.96      2315929.00      7073760.00
      2315128.97      7073159.98
#Sta/Elev= 30
  4463.8  767.83  4726.2  762.80  4959.7  761.19  4967.3  760.58  4973.9  758.03
  4981.5  757.01  4987.5  752.63  4988.8  752.13  4996.4  752.63  5008.8  755.21
  5017.1  755.05  5023.4  756.55  5031.7  755.22  5045.3  755.31  5052.6  756.36
  5102.6  755.79  5123.4  754.63  5145.3  755.78  5245.3  755.66  5395.3  757.37
  5423.4  757.96  5452.6  760.00  5467.1  759.25  5488.0  760.66  5495.3  759.56
  5531.7  759.59  5695.3  761.55  5758.8  761.39  5895.3  765.62  5995.3  770.50
#Mann=3,-1,0
  4463.8    0.05       0  4987.5   0.033       0  4996.4    0.05       0
Bank Sta=4987.5,4996.4
Exp/Cntr=0.3,0.1

Type RM Length L Ch R = 1,34470,470,470,470
BEGIN DESCRIPTION:
Harriet Creek 61.0
END DESCRIPTION:
XS GIS Cut Line= 3
      2316329.00      7074010.00      2315929.00      7072810.00
      2315779.03      7072660.03
#Sta/Elev= 30
  3730.9  766.18  3836.3  764.64  3889.0  763.17  4057.7  761.55  4078.8  760.57
  4089.3  760.92  4110.4  760.18  4173.6  760.14  4289.6  757.85  4331.7  758.41
  4416.1  758.28  4489.9  756.89  4700.7  755.27  4837.7  752.54  4848.2  752.63
  4858.8  753.48  4879.9  752.34  4974.7  752.41  4985.3  748.38  5024.1  749.32
  5033.7  748.29  5035.0  747.79  5041.5  747.79  5042.8  748.29  5052.4  750.93
  5080.7  752.75  5094.8  754.85  5109.0  758.12  5123.1  759.62  5207.9  764.86
#Mann=3,-1,0
  3730.9    0.05       0  5033.7   0.033       0  5042.8    0.05       0
Bank Sta=5033.7,5042.8
Exp/Cntr=0.3,0.1

Type RM Length L Ch R = 1,34000,473,473,473
BEGIN DESCRIPTION:
Harriet Creek 60.0
END DESCRIPTION:
XS GIS Cut Line= 3
      2316744.96      7073010.21      2316229.00      7072510.00
      2315928.97      7072459.99
#Sta/Elev= 30
  4279.3  754.56  4446.3  752.96  4460.4  752.12  4474.6  752.18  4481.8  753.46
  4566.4  751.79  4672.7  751.78  4679.6  752.63  4686.8  751.06  4693.8  751.78
  4707.9  750.81  4729.2  751.22  4863.5  748.98  4870.7  749.53  4877.7  748.20
  4913.2  750.26  4941.4  748.75  4969.7  748.89  4972.1  747.14  4973.5  746.64
  4981.3  747.14  4983.9  748.60  5008.1  748.41  5025.8  747.22  5030.9  749.16
  5038.5  749.20  5048.6  751.84  5086.6  751.15  5152.5  757.03  5302.1  765.04
#Mann=3,-1,0
  4279.3    0.05       0  4972.1   0.033       0  4981.3    0.05       0
Bank Sta=4972.1,4981.3
Exp/Cntr=0.3,0.1

Type RM Length L Ch R = 1,33527,507,507,507
BEGIN DESCRIPTION:
Harriet Creek 59.0
END DESCRIPTION:
XS GIS Cut Line= 3
      2316797.90      7072772.91      2316579.00      7072260.00
      2316428.98      7072059.97
#Sta/Elev= 30
  4442.6  751.89  4504.5  750.84  4533.6  751.75  4543.6  750.61  4557.2  750.82
  4565.4  751.69  4575.4  749.97  4604.4  748.90  4628.0  748.51  4633.4  749.18
  4686.1  749.03  4809.2  746.34  4833.2  747.35  4891.5  747.11  4956.7  747.78
  4978.5  745.72  4986.5  744.38  4987.8  743.88  4995.9  744.38  5003.4  744.56
  5013.8  746.38  5028.4  747.32  5072.1  747.39  5086.7  748.80  5093.0  750.22
  5107.6  751.39  5113.8  752.60  5128.4  753.62  5186.7  755.77  5250.3  759.72
#Mann=3,-1,0
  4442.6    0.05       0  4986.5   0.033       0  4995.9    0.05       0
Bank Sta=4986.5,4995.9
Exp/Cntr=0.3,0.1

Type RM Length L Ch R = 1,33020,649,649,649
BEGIN DESCRIPTION:
Harriet Creek 58.0
END DESCRIPTION:
XS GIS Cut Line= 3
      2316834.69      7072695.41      2316912.81      7072126.83
      2316678.96      7071959.97
#Sta/Elev= 30
  4509.9  750.63  4616.3  749.01  4697.1  746.89  4838.4  746.64  4888.8  745.96
  4919.1  744.93  4939.3  745.58  4945.0  746.68  4950.0  746.17  4959.5  743.18
  4975.0  741.04  4976.3  740.54  4983.0  740.54  4984.4  741.04  5017.1  745.27
  5060.4  745.56  5099.4  747.89  5120.3  747.97  5126.5  748.47  5170.7  749.32
  5176.9  749.96  5271.5  750.78  5292.4  752.26  5313.3  752.31  5328.0  753.25
  5334.2  757.92  5342.8  760.45  5348.9  760.15  5357.5  760.82  5371.1  760.84
#Mann=3,-1,0
  4509.9    0.05       0  4975.0   0.033       0  4984.4    0.05       0
Bank Sta=4975,4984.4
Exp/Cntr=0.3,0.1

Type RM Length L Ch R = 1,32371,138,138,138
BEGIN DESCRIPTION:
Harriet Creek 57.0
END DESCRIPTION:
XS GIS Cut Line= 3
      2317973.88      7071988.92      2317483.57      7071985.52
      2316663.62      7071942.38
#Sta/Elev= 30
  4405.3  748.11  4740.2  744.60  4790.2  745.92  4870.2  744.95  4900.4  745.58
  4970.3  743.23  4980.3  742.46  4990.3  740.61  5010.3  740.82  5044.8  739.75
  5046.3  739.25  5056.1  739.75  5090.5  743.50  5110.5  743.00  5170.6  744.69
  5230.7  743.81  5291.0  744.74  5380.9  747.35  5461.0  748.67  5476.3  749.33
  5481.3  750.52  5491.0  749.75  5511.0  750.00  5641.2  752.77  5661.2  753.56
  5666.6  756.86  5671.6  757.46  5681.3  760.43  5691.3  761.17  5716.7  760.89
#Mann=3,-1,0
  4405.3    0.05       0  5044.8   0.033       0  5056.1    0.05       0
Bank Sta=5044.8,5056.1
Exp/Cntr=0.3,0.1

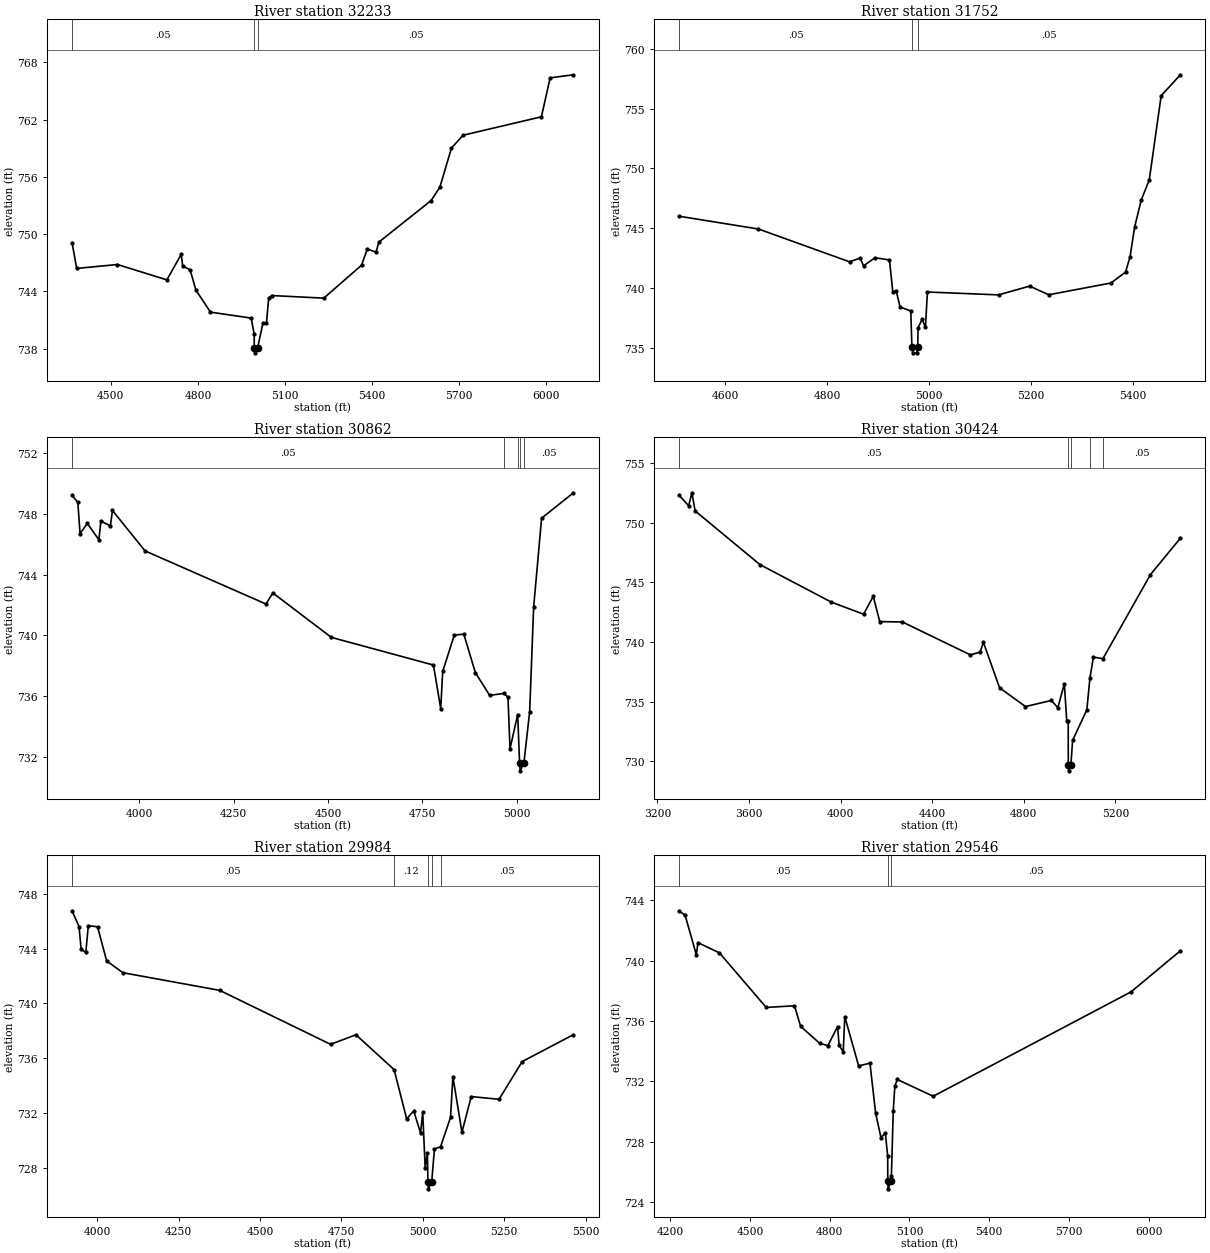
Type RM Length L Ch R = 1,32233,481,481,481
BEGIN DESCRIPTION:
Harriet Creek 56.0
END DESCRIPTION:
XS GIS Cut Line= 3
      2318024.98      7071893.58      2317391.64      7071845.91
      2316298.60      7071815.27
#Sta/Elev= 30
  4366.2  749.11  4382.2  746.41  4522.6  746.82  4693.1  745.21  4742.6  747.88
  4747.6  746.68  4773.3  746.25  4793.4  744.13  4843.5  741.83  4983.9  741.21
  4994.0  739.53  4994.5  738.07  4996.0  737.57  5005.8  738.07  5024.0  740.66
  5036.4  740.68  5044.0  743.28  5054.0  743.57  5234.1  743.30  5364.1  746.74
  5384.1  748.44  5414.1  748.12  5424.1  749.17  5604.2  753.52  5634.2  754.91
  5674.2  759.01  5714.3  760.36  5984.4  762.29  6014.4  766.37  6094.8  766.69
#Mann=3,-1,0
  4366.2    0.05       0  4994.5    0.04       0  5005.8    0.05       0
Bank Sta=4994.5,5005.8
Exp/Cntr=0.3,0.1

Type RM Length L Ch R = 1,31752,890,890,890
BEGIN DESCRIPTION:
Harriet Creek 55.0
END DESCRIPTION:
XS GIS Cut Line= 3
      2318007.95      7071771.02      2317629.00      7071460.00
      2317178.99      7071259.99
#Sta/Elev= 30
  4509.9  746.01  4665.8  744.94  4844.4  742.20  4865.2  742.52  4871.7  741.86
  4893.9  742.54  4922.5  742.36  4929.1  739.66  4935.6  739.79  4943.4  738.42
  4964.3  738.10  4966.5  735.10  4968.0  734.60  4976.2  734.60  4977.8  735.10
  4978.6  736.70  4986.5  737.40  4993.0  736.74  4996.9  739.68  5136.2  739.44
  5197.1  740.17  5234.7  739.45  5356.5  740.43  5385.2  741.34  5394.1  742.64
  5403.0  745.10  5416.0  747.37  5431.7  749.04  5455.0  756.07  5492.6  757.82
#Mann=3,-1,0
  4509.9    0.05       0  4966.5   0.033       0  4977.8    0.05       0
Bank Sta=4966.5,4977.8
Exp/Cntr=0.3,0.1

Type RM Length L Ch R = 1,30862,438,438,438
BEGIN DESCRIPTION:
Harriet Creek 54.0
END DESCRIPTION:
XS GIS Cut Line= 3
      2318078.99      7071909.97      2317679.00      7070810.00
      2317528.95      7070759.98
#Sta/Elev= 30
  3821.9  749.20  3837.2  748.74  3843.1  746.69  3862.4  747.36  3893.0  746.28
  3898.3  747.50  3923.6  747.20  3928.9  748.21  4015.4  745.55  4335.9  742.06
  4353.9  742.79  4508.9  739.87  4779.5  738.05  4798.8  735.19  4804.1  737.63
  4834.7  740.02  4860.0  740.08  4890.6  737.55  4928.5  736.06  4967.3  736.19
  4977.0  735.92  4982.4  732.55  5002.7  734.80  5007.8  731.60  5009.3  731.10
  5019.1  731.60  5034.5  734.99  5045.0  741.85  5066.1  747.70  5150.5  749.37
#Mann=5,-1,0
  3821.9    0.05       0  4967.3    0.12       0  5002.7    0.05       0
  5007.8    0.07       0  5019.1    0.05       0
Bank Sta=5007.8,5019.1
Exp/Cntr=0.3,0.1

Type RM Length L Ch R = 1,30424,440,440,440
BEGIN DESCRIPTION:
Harriet Creek 53.0
END DESCRIPTION:
XS GIS Cut Line= 3
      2319229.01      7071810.01      2318029.00      7070610.00
      2317579.01      7070410.01
#Sta/Elev= 30
  3294.3  752.33  3336.7  751.43  3350.9  752.52  3365.0  751.00  3647.9  746.50
  3959.0  743.36  4100.4  742.34  4142.8  743.84  4171.1  741.72  4270.1  741.69
  4567.1  738.93  4609.5  739.17  4623.7  739.99  4694.4  736.17  4807.5  734.60
  4920.7  735.11  4948.9  734.50  4977.2  736.51  4987.8  733.39  4994.1  733.39
  4994.6  729.71  4996.2  729.21  5005.9  729.71  5013.3  731.76  5075.5  734.33
  5089.1  737.02  5104.2  738.74  5146.0  738.62  5353.2  745.66  5483.8  748.71
#Mann=5,-1,0
  3294.3    0.05       0  4994.6   0.033       0  5005.9    0.05       0
  5089.1    0.12       0  5146.0    0.05       0
Bank Sta=4994.6,5005.9
Exp/Cntr=0.3,0.1

Type RM Length L Ch R = 1,29984,438,438,438
BEGIN DESCRIPTION:
Harriet Creek 52.0
END DESCRIPTION:
XS GIS Cut Line= 3
      2319179.03      7071210.03      2318379.00      7070510.00
      2318064.70      7070151.67
#Sta/Elev= 30
  3923.0  746.78  3944.4  745.63  3951.0  743.95  3965.3  743.74  3972.9  745.69
  4001.3  745.61  4029.3  743.11  4079.2  742.25  4376.2  740.96  4717.0  737.01
  4794.8  737.71  4912.0  735.16  4950.5  731.56  4972.3  732.14  4993.2  730.52
  4999.8  732.04  5007.4  727.98  5014.1  729.06  5015.9  726.94  5017.5  726.44
  5027.3  726.94  5035.9  729.35  5054.6  729.52  5085.2  731.67  5092.5  734.64
  5120.3  730.58  5148.8  733.19  5234.2  732.99  5305.3  735.75  5462.7  737.72
#Mann=5,-1,0
  3923.0    0.05       0  4912.0    0.12       0  5015.9    0.07       0
  5027.3    0.12       0  5054.6    0.05       0
Bank Sta=5015.9,5027.3
Exp/Cntr=0.3,0.1

Type RM Length L Ch R = 1,29546,465,465,465
BEGIN DESCRIPTION:
Harriet Creek 51.0
END DESCRIPTION:
XS GIS Cut Line= 4
      2319128.98      7070959.97      2318729.00      7070310.00
      2318511.58      7069991.65      2317773.46      7069980.00
#Sta/Elev= 30
  4232.5  743.30  4255.6  743.01  4298.1  740.38  4304.0  741.19  4385.1  740.51
  4560.9  736.90  4667.3  737.01  4690.4  735.65  4761.9  734.53  4792.8  734.37
  4829.5  735.63  4835.3  734.39  4850.7  733.96  4856.6  736.29  4908.7  733.03
  4951.3  733.21  4972.6  729.91  4992.7  728.28  5009.2  728.59  5018.1  727.05
  5018.4  725.39  5020.0  724.89  5029.8  725.39  5032.0  725.74  5039.0  730.07
  5045.1  731.70  5054.0  732.13  5189.4  731.02  5933.8  737.93  6119.4  740.65
#Mann=3,-1,0
  4232.5    0.05       0  5018.4   0.033       0  5029.8    0.05       0
Bank Sta=5018.4,5029.8
Exp/Cntr=0.3,0.1

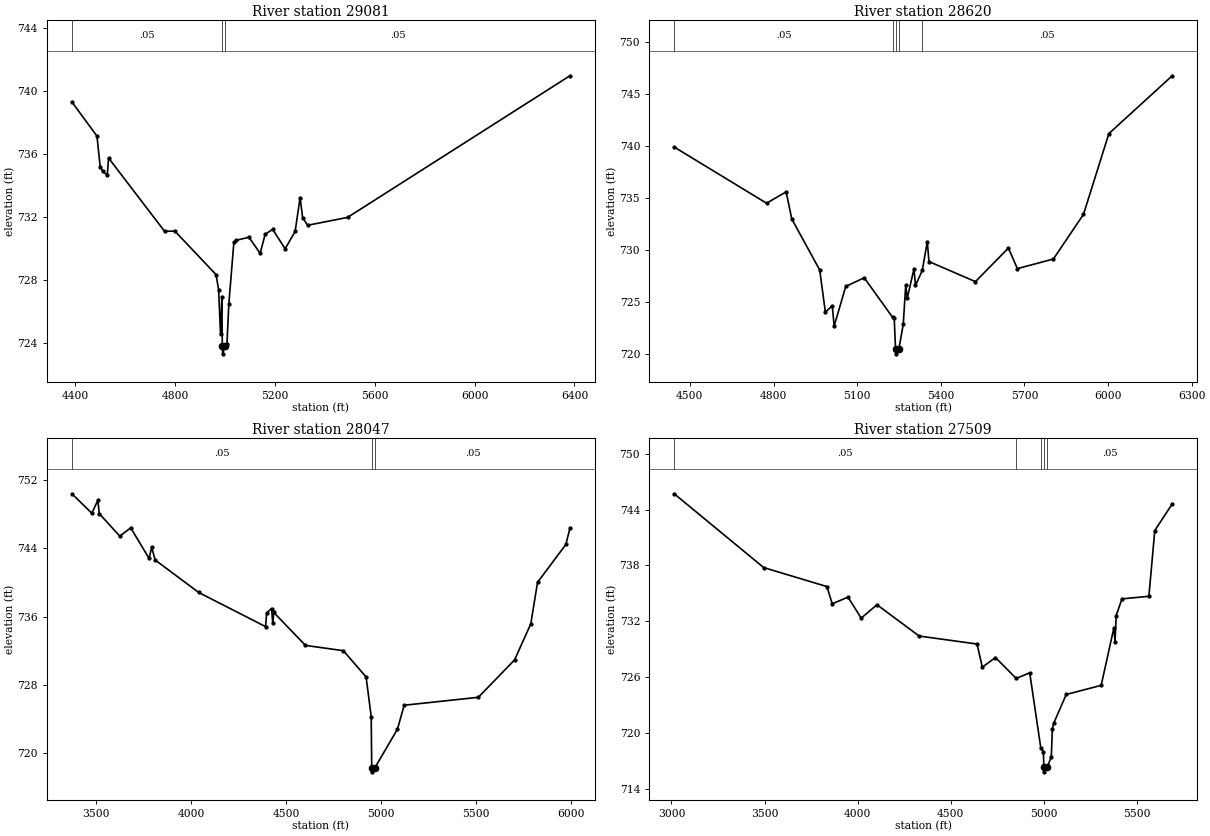
Type RM Length L Ch R = 1,29081,461,461,461
BEGIN DESCRIPTION:
Harriet Creek 50.0
END DESCRIPTION:
XS GIS Cut Line= 4
      2319129.01      7070660.04      2318979.00      7070060.00
      2318965.93      7069932.14      2317718.56      7069932.32
#Sta/Elev= 30
  4387.4  739.31  4487.9  737.14  4500.8  735.18  4511.1  734.91  4529.2  734.66
  4534.3  735.75  4758.5  731.10  4799.7  731.11  4964.7  728.35  4975.0  727.39
  4982.7  724.56  4987.9  726.90  4989.9  723.82  4991.4  723.32  5001.3  723.82
  5008.4  723.96  5016.0  726.50  5036.1  730.40  5046.1  730.53  5096.4  730.72
  5141.4  729.70  5161.4  730.91  5191.4  731.22  5241.4  729.99  5281.4  731.09
  5301.4  733.24  5311.4  731.97  5331.4  731.48  5491.4  731.98  6381.8  740.97
#Mann=3,-1,0
  4387.4    0.05       0  4989.9   0.033       0  5001.3    0.05       0
Bank Sta=4989.9,5001.3
Exp/Cntr=0.3,0.1

Type RM Length L Ch R = 1,28620,573,573,573
BEGIN DESCRIPTION:
Harriet Creek 49.0
END DESCRIPTION:
XS GIS Cut Line= 3
      2319329.00      7070659.97      2319379.00      7070110.00
      2318919.06      7068964.63
#Sta/Elev= 30
  4443.8  739.90  4775.1  734.50  4845.4  735.59  4865.5  732.99  4965.9  728.07
  4986.0  724.03  5010.8  724.64  5017.6  722.69  5059.2  726.50  5125.4  727.33
  5227.2  723.53  5233.1  723.42  5237.7  720.52  5239.4  720.02  5250.0  720.52
  5265.4  722.86  5274.3  726.63  5279.7  725.37  5303.9  728.18  5309.3  726.59
  5333.7  728.04  5351.7  730.81  5357.7  728.89  5524.4  726.96  5642.6  730.19
  5674.9  728.21  5804.2  729.14  5912.0  733.43  6003.0  741.19  6230.3  746.75
#Mann=5,-1,0
  4443.8    0.05       0  5227.2    0.12       0  5237.7   0.033       0
  5250.0    0.12       0  5333.7    0.05       0
Bank Sta=5237.7,5250
Exp/Cntr=0.3,0.1

Type RM Length L Ch R = 1,28047,538,538,538
BEGIN DESCRIPTION:
Harriet Creek 48.0
END DESCRIPTION:
XS GIS Cut Line= 3
      2320179.01      7071260.05      2319679.00      7069710.00
      2319028.98      7068959.98
#Sta/Elev= 30
  3371.6  750.40  3476.7  748.12  3508.2  749.63  3515.9  748.07  3623.8  745.44
  3681.4  746.41  3777.5  742.84  3791.9  744.13  3809.5  742.65  4039.1  738.84
  4390.9  734.84  4396.9  736.44  4422.4  736.96  4429.0  735.21  4434.2  736.50
  4601.0  732.64  4800.7  732.02  4920.2  728.94  4947.0  724.29  4949.7  718.33
  4951.7  717.83  4966.9  718.33  5085.3  722.83  5120.4  725.63  5510.8  726.56
  5701.6  730.94  5787.1  735.17  5822.3  740.02  5971.4  744.46  5992.8  746.35
#Mann=3,-1,0
  3371.6    0.05       0  4949.7   0.033       0  4966.9    0.05       0
Bank Sta=4949.7,4966.9
Exp/Cntr=0.3,0.1

Type RM Length L Ch R = 1,27509,540,540,540
BEGIN DESCRIPTION:
Harriet Creek 47.0
END DESCRIPTION:
XS GIS Cut Line= 3
      2321179.00      7070660.00      2319779.00      7069260.00
      2319429.01      7068660.02
#Sta/Elev= 30
  3014.7  745.70  3495.5  737.77  3835.0  735.73  3863.2  733.88  3948.1  734.60
  4018.8  732.34  4103.7  733.78  4329.9  730.42  4641.1  729.56  4669.3  727.07
  4740.0  728.11  4851.5  725.86  4923.9  726.47  4983.6  718.37  4997.5  718.01
  4999.6  716.33  5001.6  715.83  5016.8  716.33  5039.7  717.40  5045.5  720.43
  5052.5  721.04  5119.9  724.14  5307.6  725.12  5376.2  731.32  5382.0  729.77
  5388.2  732.61  5419.2  734.41  5563.9  734.69  5595.4  741.75  5689.2  744.61
#Mann=5,-1,0
  3014.7    0.05       0  4851.5    0.12       0  4983.6    0.05       0
  4999.6   0.033       0  5016.8    0.05       0
Bank Sta=4999.6,5016.8
Exp/Cntr=0.3,0.1