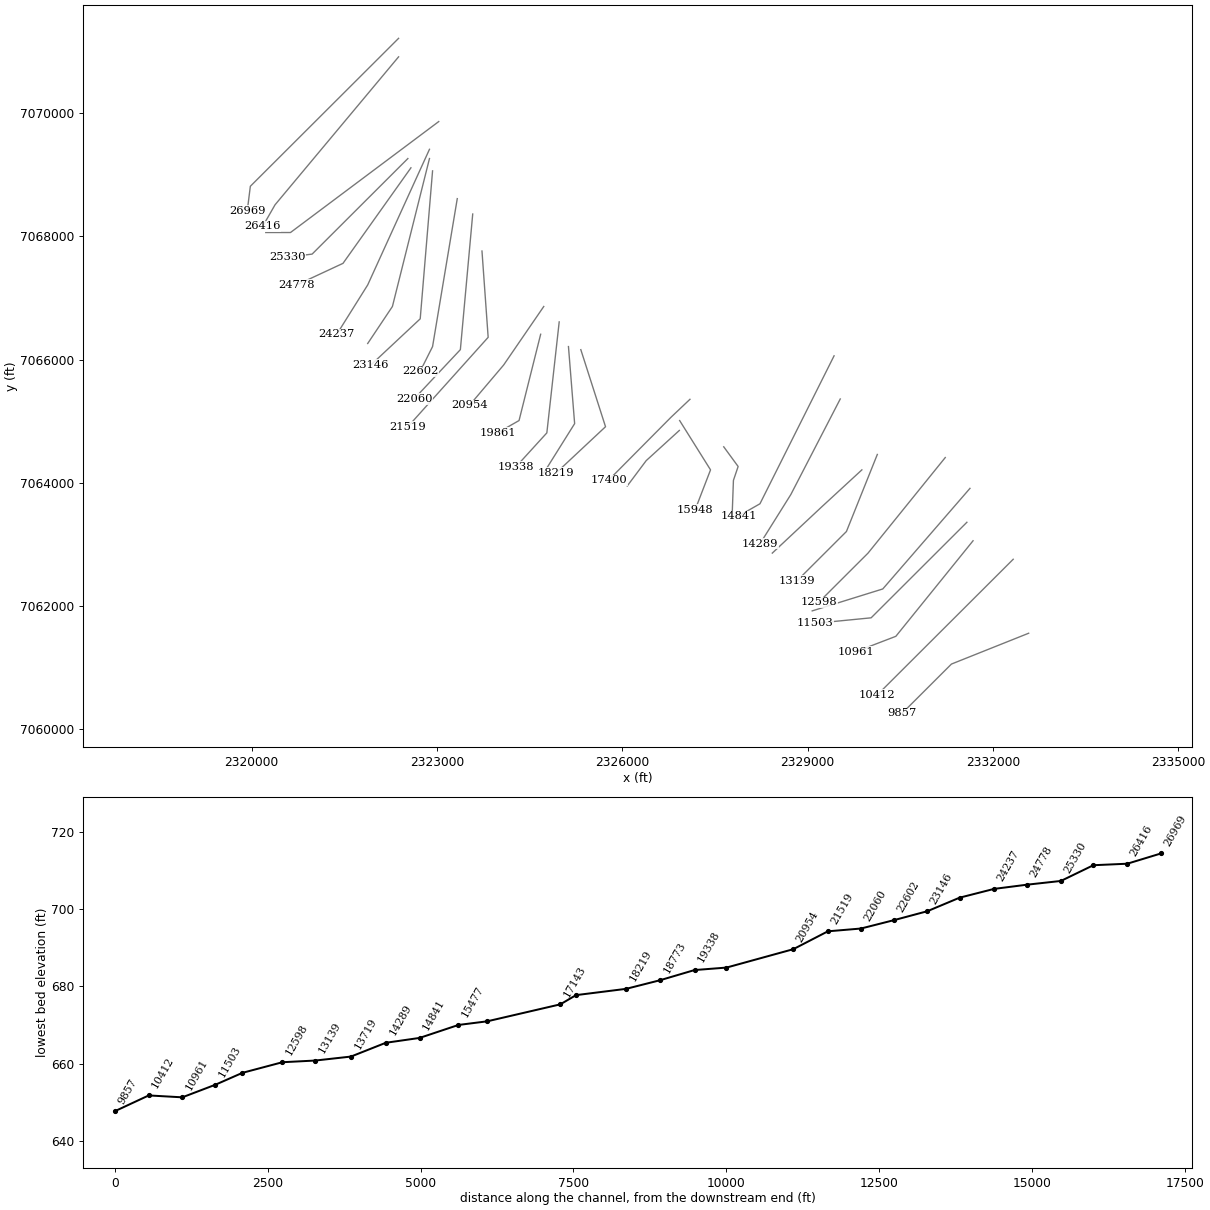
HEC-RAS study Harriet Creek.prj: Harriet Creek Base Level Engineering

--- Harriet Creek.g01 (geometry) --- (continued)

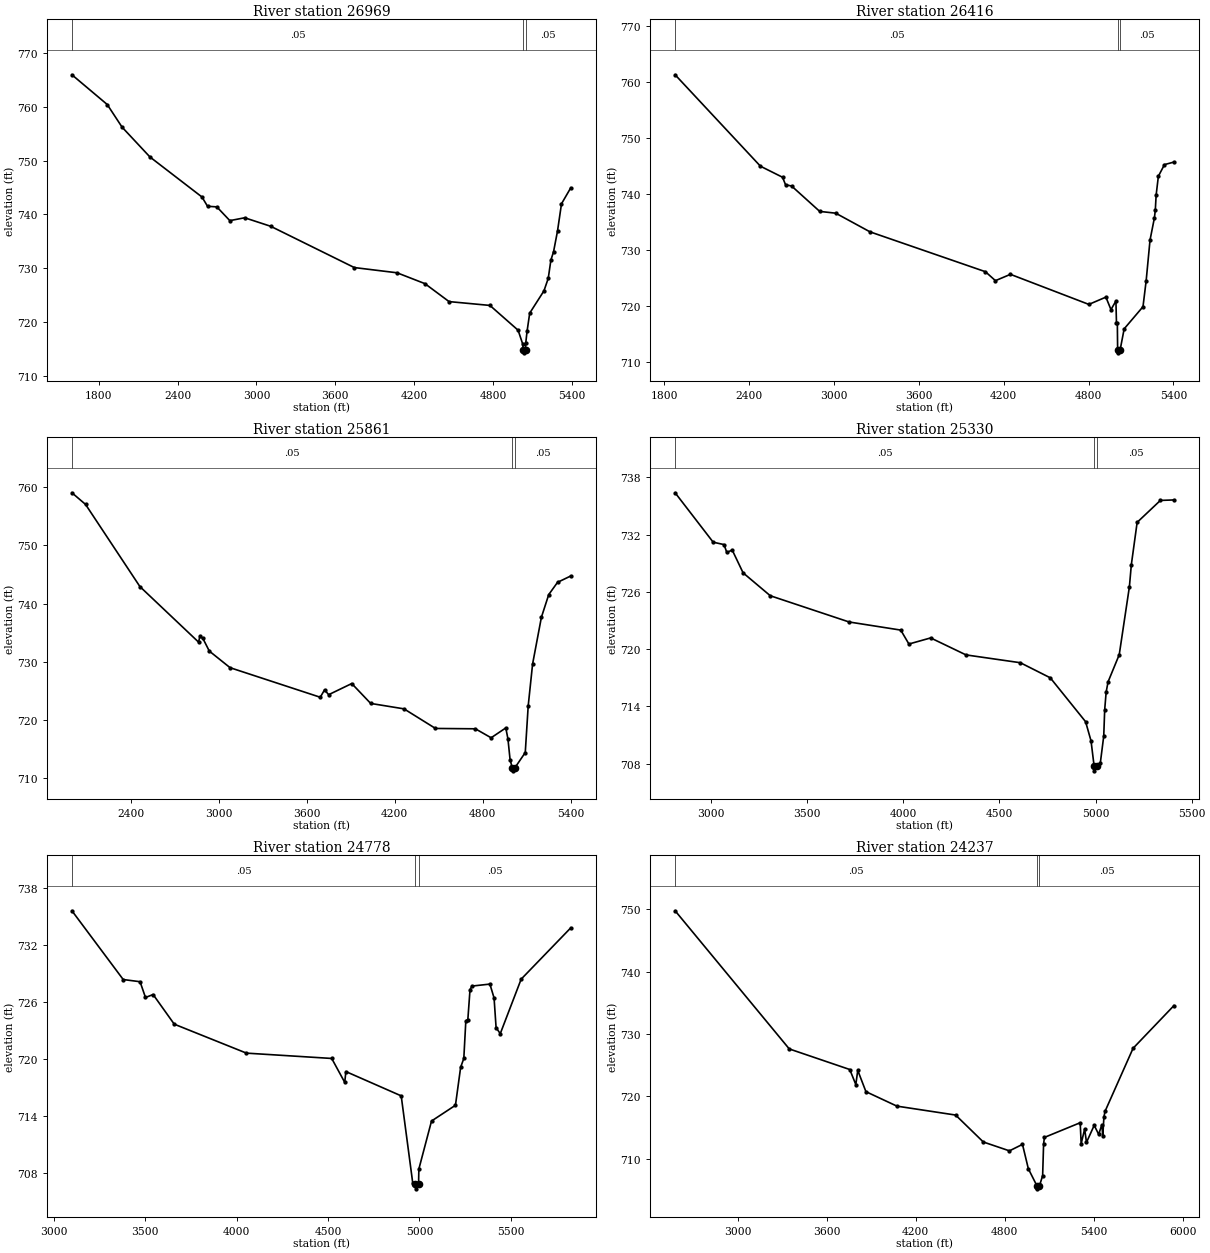
Type RM Length L Ch R = 1,26969,553,553,553
BEGIN DESCRIPTION:
Harriet Creek 46.0
END DESCRIPTION:
XS GIS Cut Line= 3
      2322379.00      7071210.00      2319979.00      7068810.00
      2319929.00      7068410.03
#Sta/Elev= 30
  1595.5  765.90  1864.2  760.39  1977.3  756.19  2189.5  750.66  2585.5  743.24
  2627.9  741.52  2698.6  741.41  2797.6  738.86  2910.7  739.39  3108.7  737.81
  3745.1  730.16  4070.4  729.19  4282.5  727.18  4466.4  723.85  4777.5  723.14
  4992.1  718.54  5027.4  715.95  5031.4  714.85  5033.4  714.35  5048.7  714.85
  5050.1  716.15  5060.2  718.35  5080.3  721.71  5188.7  725.84  5221.4  728.16
  5241.6  731.55  5261.7  733.08  5292.0  736.94  5322.2  741.98  5392.7  744.94
#Mann=3,-1,0
  1595.5    0.05       0  5031.4   0.033       0  5048.7    0.05       0
Bank Sta=5031.4,5048.7
Exp/Cntr=0.3,0.1

Type RM Length L Ch R = 1,26416,555,555,555
BEGIN DESCRIPTION:
Harriet Creek 45.0
END DESCRIPTION:
XS GIS Cut Line= 3
      2322378.97      7070909.97      2320379.00      7068510.00
      2320178.99      7068159.97
#Sta/Elev= 30
  1876.4  761.35  2479.7  745.02  2635.9  743.05  2657.4  741.70  2699.7  741.49
  2898.8  736.95  3012.1  736.63  3254.2  733.30  4070.4  726.18  4141.3  724.58
  4247.4  725.71  4801.9  720.34  4922.4  721.64  4958.2  719.41  4993.3  720.95
  4997.2  716.93  5003.3  716.93  5005.4  712.19  5007.4  711.69  5022.8  712.19
  5051.6  715.98  5184.7  719.93  5207.1  724.57  5234.4  731.83  5265.4  735.79
  5271.8  737.18  5277.6  739.85  5293.4  743.23  5336.6  745.31  5403.6  745.76
#Mann=3,-1,0
  1876.4    0.05       0  5005.4   0.033       0  5022.8    0.05       0
Bank Sta=5005.4,5022.8
Exp/Cntr=0.3,0.1

Type RM Length L Ch R = 1,25861,531,531,531
BEGIN DESCRIPTION:
Harriet Creek 44.0
END DESCRIPTION:
XS GIS Cut Line= 3
      2323028.99      7069859.99      2320629.00      7068060.00
      2320228.99      7068060.00
#Sta/Elev= 30
  2000.2  758.99  2092.9  757.00  2463.7  742.90  2863.7  733.37  2872.1  734.38
  2892.9  734.01  2936.6  731.84  3078.3  728.99  3692.9  723.92  3722.1  725.19
  3750.2  724.36  3907.5  726.27  4036.6  722.86  4263.7  721.93  4478.3  718.57
  4750.2  718.51  4857.5  716.97  4957.5  718.66  4972.1  716.78  4986.6  713.24
  5001.5  711.80  5003.5  711.30  5018.9  711.80  5090.2  714.44  5110.2  722.44
  5140.2  729.63  5200.2  737.64  5250.2  741.53  5310.2  743.63  5400.2  744.72
#Mann=3,-1,0
  2000.2    0.05       0  5001.5   0.033       0  5018.9    0.05       0
Bank Sta=5001.5,5018.9
Exp/Cntr=0.3,0.1

Type RM Length L Ch R = 1,25330,552,552,552
BEGIN DESCRIPTION:
Harriet Creek 43.0
END DESCRIPTION:
XS GIS Cut Line= 3
      2322529.03      7069260.03      2320979.00      7067710.00
      2320578.99      7067660.00
#Sta/Elev= 30
  2812.7  736.38  3010.7  731.20  3067.3  730.95  3081.4  730.13  3109.7  730.38
  3166.3  727.99  3307.7  725.59  3717.8  722.84  3986.5  721.99  4029.0  720.53
  4142.1  721.17  4326.0  719.39  4608.8  718.57  4764.4  716.99  4948.2  712.39
  4976.5  710.38  4992.5  707.74  4994.5  707.24  5010.0  707.74  5024.9  708.07
  5042.6  710.88  5047.6  713.65  5055.2  715.50  5065.2  716.57  5123.2  719.41
  5176.1  726.53  5186.2  728.85  5216.4  733.28  5337.3  735.58  5407.9  735.63
#Mann=3,-1,0
  2812.7    0.05       0  4992.5   0.033       0  5010.0    0.05       0
Bank Sta=4992.5,5010
Exp/Cntr=0.3,0.1

Type RM Length L Ch R = 1,24778,541,541,541
BEGIN DESCRIPTION:
Harriet Creek 42.0
END DESCRIPTION:
XS GIS Cut Line= 3
      2322578.99      7069109.98      2321479.00      7067560.00
      2320728.98      7067209.99
#Sta/Elev= 30
  3099.4  735.56  3379.9  728.32  3472.1  728.09  3501.7  726.43  3543.5  726.74
  3659.1  723.62  4054.0  720.57  4520.3  720.01  4591.6  717.49  4597.7  718.63
  4900.4  716.07  4963.2  706.94  4977.8  706.78  4979.8  706.28  4995.3  706.78
  4997.0  708.37  5066.2  713.42  5197.1  715.08  5225.5  719.08  5242.8  720.01
  5253.8  723.95  5264.9  724.11  5276.7  727.24  5287.0  727.63  5385.5  727.84
  5408.3  726.38  5419.4  723.25  5442.2  722.62  5556.5  728.36  5827.7  733.76
#Mann=3,-1,0
  3099.4    0.05       0  4977.8   0.033       0  4995.3    0.05       0
Bank Sta=4977.8,4995.3
Exp/Cntr=0.3,0.1

Type RM Length L Ch R = 1,24237,564,564,564
BEGIN DESCRIPTION:
Harriet Creek 41.0
END DESCRIPTION:
XS GIS Cut Line= 3
      2322878.98      7069409.96      2321879.00      7067210.00
      2321378.98      7066409.97
#Sta/Elev= 30
  2579.0  749.77  3347.9  727.62  3755.4  724.32  3796.1  721.91  3809.2  724.18
  3864.2  720.77  4072.9  718.45  4468.3  717.02  4655.0  712.70  4830.8  711.28
  4918.7  712.32  4958.2  708.41  5015.7  705.69  5017.7  705.19  5033.3  705.69
  5054.5  707.30  5061.0  712.44  5066.9  713.44  5307.5  715.79  5314.0  712.43
  5337.5  714.77  5349.9  712.64  5401.8  715.37  5431.9  713.93  5453.7  715.48
  5459.6  713.66  5467.3  716.72  5474.9  717.62  5663.6  727.72  5939.0  734.57
#Mann=3,-1,0
  2579.0    0.05       0  5015.7   0.033       0  5033.3    0.05       0
Bank Sta=5015.7,5033.3
Exp/Cntr=0.3,0.1

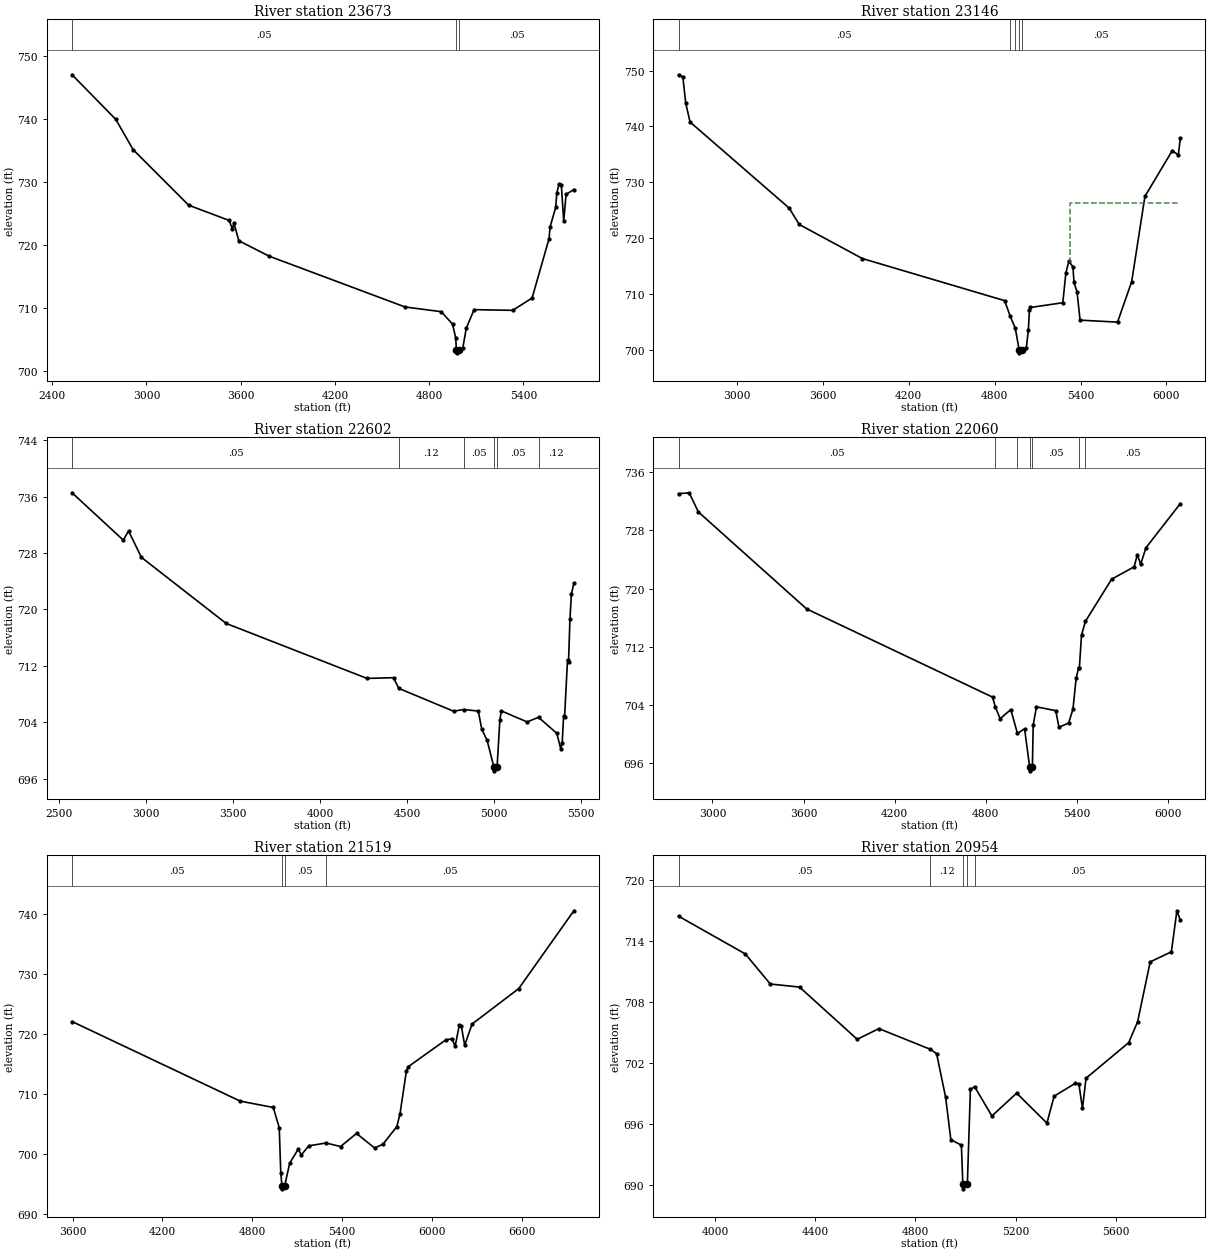
Type RM Length L Ch R = 1,23673,527,527,527
BEGIN DESCRIPTION:
Harriet Creek 40.0
END DESCRIPTION:
XS GIS Cut Line= 3
      2322879.00      7069260.00      2322279.00      7066860.00
      2321878.99      7066259.98
#Sta/Elev= 30
  2526.1  747.08  2804.4  740.00  2915.2  735.18  3268.3  726.37  3526.0  723.95
  3546.6  722.62  3556.9  723.50  3587.8  720.72  3781.1  718.27  4646.9  710.20
  4876.3  709.46  4948.4  707.49  4969.0  705.28  4973.0  703.42  4975.0  702.92
  4990.8  703.42  5013.5  703.63  5036.0  706.82  5085.6  709.78  5332.0  709.67
  5455.2  711.63  5563.3  721.06  5569.3  722.88  5605.4  726.02  5612.9  728.35
  5626.4  729.75  5641.5  729.55  5656.5  723.82  5671.5  728.09  5721.1  728.85
#Mann=3,-1,0
  2526.1    0.05       0  4973.0   0.033       0  4990.8    0.05       0
Bank Sta=4973,4990.8
Exp/Cntr=0.3,0.1

Type RM Length L Ch R = 1,23146,544,544,544
BEGIN DESCRIPTION:
Harriet Creek 39.0
END DESCRIPTION:
XS GIS Cut Line= 3
      2322929.00      7069060.01      2322729.00      7066660.00
      2321929.01      7065910.01
#Sta/Elev= 30
  2592.1  749.25  2622.2  748.89  2642.3  744.18  2672.4  740.79  3364.8  725.37
  3435.0  722.43  3876.5  716.32  4870.0  708.78  4906.7  706.12  4944.3  703.82
  4971.4  699.93  4973.4  699.43  4989.3  699.93  5021.7  700.37  5035.8  703.56
  5042.7  707.16  5050.0  707.56  5276.2  708.41  5297.7  713.78  5318.7  715.82
  5347.0  714.85  5354.3  712.04  5375.3  710.38  5396.8  705.29  5658.4  704.93
  5757.3  712.19  5849.6  727.46  6040.6  735.65  6083.1  734.89  6097.0  737.92
#Mann=5,-1,0
  2592.1    0.05       0  4906.7    0.12       0  4944.3    0.05       0
  4971.4   0.033       0  4989.3    0.05       0
#XS Ineff=2,0
       0                 5326.40    0.00  726.35
Permanent Ineff=
       F       F
Bank Sta=4971.4,4989.3
Exp/Cntr=0.3,0.1

Type RM Length L Ch R = 1,22602,542,542,542
BEGIN DESCRIPTION:
Harriet Creek 38.0
END DESCRIPTION:
XS GIS Cut Line= 3
      2323329.00      7068609.98      2322929.00      7066210.00
      2322729.00      7065810.00
#Sta/Elev= 30
  2577.1  736.54  2871.1  729.83  2901.5  731.13  2975.0  727.39  3461.6  718.02
  4270.1  710.23  4422.2  710.33  4452.1  708.82  4766.9  705.58  4825.0  705.82
  4908.8  705.60  4929.1  703.00  4959.5  701.46  4998.7  697.63  5000.7  697.13
  5016.6  697.63  5032.5  704.28  5040.9  705.63  5189.1  704.06  5254.6  704.72
  5359.6  702.44  5381.9  700.27  5390.3  701.08  5398.7  704.95  5404.3  704.81
  5421.1  712.90  5426.7  712.54  5435.0  718.66  5443.4  722.20  5457.4  723.71
#Mann=6,-1,0
  2577.1    0.05       0  4452.1    0.12       0  4825.0    0.05       0
  4998.7   0.033       0  5016.6    0.05       0  5254.6    0.12       0
Bank Sta=4998.7,5016.6
Exp/Cntr=0.3,0.1

Type RM Length L Ch R = 1,22060,541,541,541
BEGIN DESCRIPTION:
Harriet Creek 37.0
END DESCRIPTION:
XS GIS Cut Line= 3
      2323579.00      7068359.95      2323379.00      7066160.00
      2322629.01      7065360.01
#Sta/Elev= 30
  2776.3  733.03  2846.5  733.16  2906.8  730.53  3619.7  717.21  4844.7  705.09
  4864.2  703.68  4895.0  702.12  4965.2  703.38  5008.9  700.09  5055.9  700.74
  5089.5  695.46  5091.5  694.96  5107.4  695.46  5112.6  701.25  5134.1  703.75
  5261.1  703.23  5282.5  700.94  5346.1  701.53  5374.4  703.42  5395.9  707.71
  5412.0  709.12  5416.9  709.15  5431.0  713.61  5456.6  715.49  5629.3  721.29
  5777.8  722.99  5798.9  724.67  5820.3  723.33  5855.5  725.61  6081.9  731.68
#Mann=7,-1,0
  2776.3    0.05       0  4864.2    0.12       0  5008.9    0.05       0
  5089.5    0.07       0  5107.4    0.05       0  5412.0    0.12       0
  5456.6    0.05       0
Bank Sta=5089.5,5107.4
Exp/Cntr=0.3,0.1

Type RM Length L Ch R = 1,21519,565,565,565
BEGIN DESCRIPTION:
Harriet Creek 36.0
END DESCRIPTION:
XS GIS Cut Line= 3
      2323729.00      7067760.04      2323829.00      7066360.00
      2322529.03      7064910.03
#Sta/Elev= 30
  3596.9  722.09  4719.8  708.84  4940.4  707.79  4980.5  704.41  4990.5  696.93
  4998.6  694.74  5000.6  694.24  5016.6  694.74  5050.2  698.51  5107.0  700.84
  5128.0  699.89  5177.3  701.40  5293.2  701.87  5390.0  701.28  5496.5  703.46
  5616.9  701.04  5672.9  701.66  5765.7  704.61  5786.6  706.67  5829.2  713.81
  5843.4  714.60  6090.8  719.00  6133.5  719.24  6155.1  717.98  6182.8  721.48
  6197.0  721.28  6218.7  718.14  6268.0  721.67  6579.8  727.58  6947.9  740.53
#Mann=4,-1,0
  3596.9    0.05       0  4998.6   0.033       0  5016.6    0.05       0
  5293.2    0.05       0
Bank Sta=4998.6,5016.6
Exp/Cntr=0.3,0.1

Type RM Length L Ch R = 1,20954,1093,1093,1093
BEGIN DESCRIPTION:
Harriet Creek 35.0
END DESCRIPTION:
XS GIS Cut Line= 3
      2324729.03      7066860.04      2324079.00      7065910.00
      2323529.00      7065260.00
#Sta/Elev= 30
  3854.5  716.47  4121.1  712.75  4220.8  709.79  4337.4  709.49  4567.6  704.35
  4654.2  705.40  4859.8  703.36  4884.5  702.93  4920.4  698.64  4941.3  694.47
  4983.3  693.93  4989.1  690.13  4991.1  689.63  5007.2  690.13  5019.3  699.41
  5036.0  699.69  5105.1  696.80  5203.9  699.05  5324.8  696.10  5353.4  698.75
  5437.9  700.02  5452.2  699.96  5466.5  697.55  5480.8  700.52  5651.1  704.02
  5686.8  706.09  5736.8  711.97  5821.4  712.96  5843.4  717.00  5857.1  716.08
#Mann=5,-1,0
  3854.5    0.05       0  4859.8    0.12       0  4989.1    0.07       0
  5007.2    0.12       0  5036.0    0.05       0
Bank Sta=4989.1,5007.2
Exp/Cntr=0.3,0.1

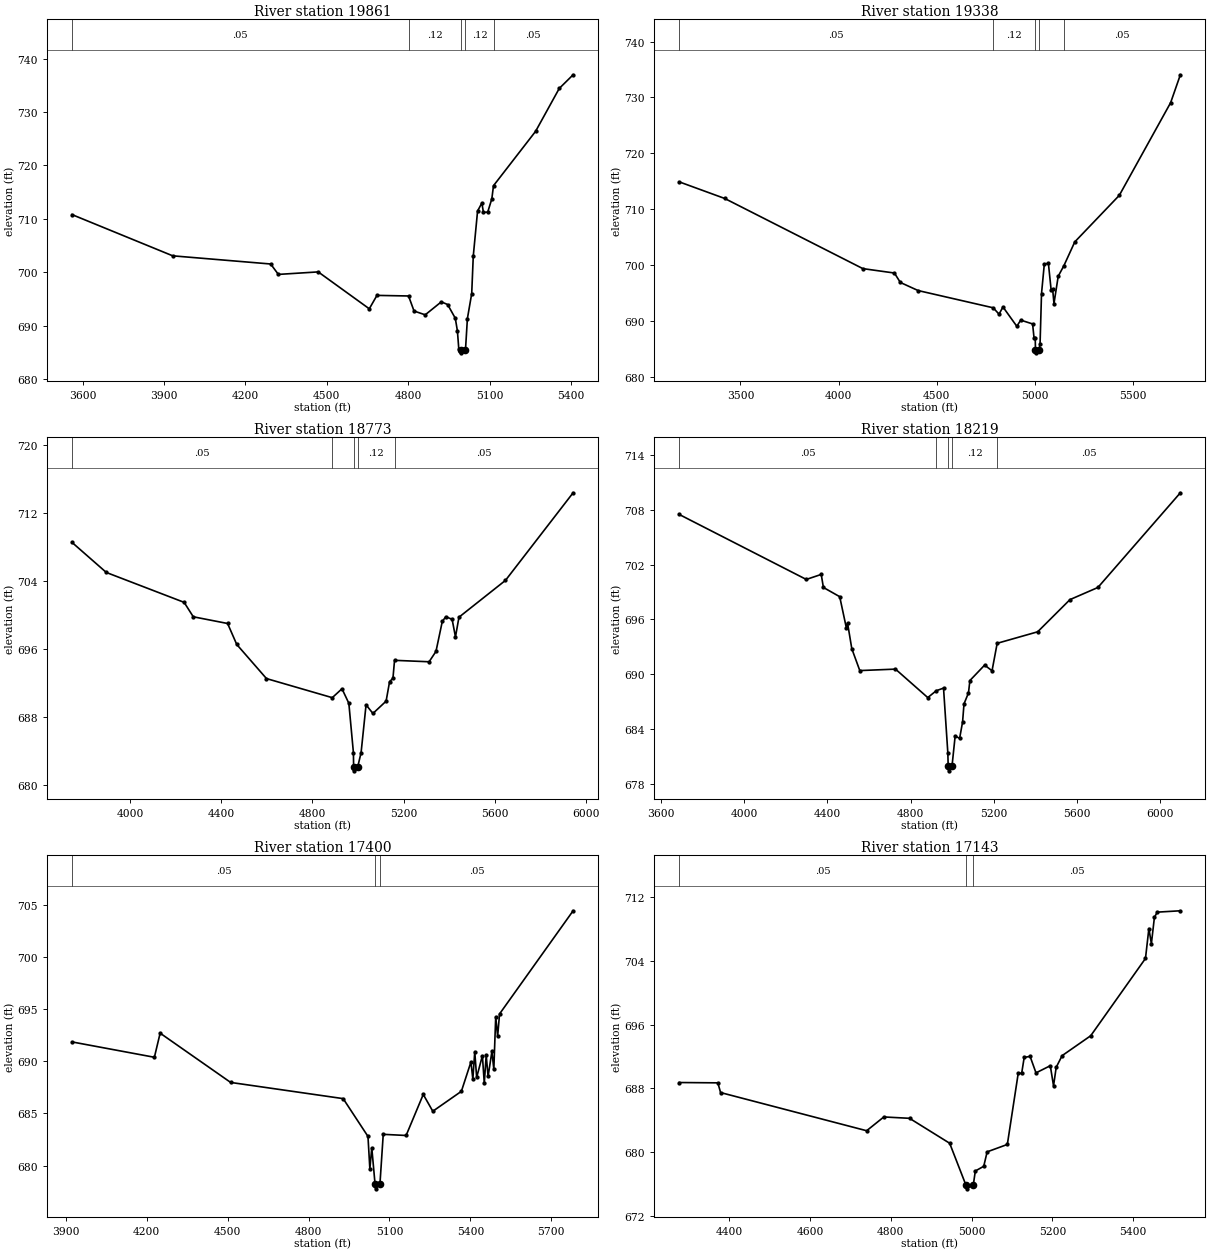
Type RM Length L Ch R = 1,19861,523,523,523
BEGIN DESCRIPTION:
Harriet Creek 34.0
END DESCRIPTION:
XS GIS Cut Line= 3
      2324678.99      7066409.97      2324329.00      7065010.00
      2323978.97      7064809.98
#Sta/Elev= 30
  3561.3  710.77  3932.3  703.05  4293.1  701.52  4321.5  699.57  4468.3  700.04
  4656.5  693.13  4684.8  695.64  4801.2  695.53  4821.4  692.71  4862.6  692.00
  4921.9  694.43  4945.1  693.93  4973.4  691.36  4981.2  688.99  4986.3  685.61
  4992.7  685.38  4994.7  684.88  5010.9  685.38  5018.0  691.30  5033.9  695.99
  5039.6  702.98  5055.5  711.45  5071.3  712.94  5077.1  711.19  5092.9  711.24
  5108.0  713.73  5114.2  716.19  5269.3  726.37  5356.4  734.40  5407.5  736.96
#Mann=5,-1,0
  3561.3    0.05       0  4801.2    0.12       0  4992.7    0.07       0
  5010.9    0.12       0  5114.2    0.05       0
Bank Sta=4992.7,5010.9
Exp/Cntr=0.3,0.1

Type RM Length L Ch R = 1,19338,565,565,565
BEGIN DESCRIPTION:
Harriet Creek 33.0
END DESCRIPTION:
XS GIS Cut Line= 3
      2324979.00      7066610.04      2324779.00      7064810.00
      2324279.01      7064260.02
#Sta/Elev= 30
  3188.2  714.87  3419.7  711.90  4124.0  699.33  4284.9  698.54  4315.1  696.85
  4405.7  695.40  4788.4  692.31  4818.2  691.17  4838.3  692.46  4908.8  689.00
  4928.9  690.10  4989.3  689.42  4996.8  686.87  5002.7  686.87  5004.1  684.74
  5006.1  684.24  5022.3  684.74  5027.4  685.85  5034.8  694.85  5049.0  700.12
  5069.9  700.28  5084.1  695.41  5091.6  695.61  5098.3  693.07  5119.9  697.96
  5149.1  699.87  5204.4  704.12  5431.4  712.46  5693.0  729.06  5742.6  734.06
#Mann=5,-1,0
  3188.2    0.05       0  4788.4    0.12       0  5004.1    0.07       0
  5022.3    0.12       0  5149.1    0.05       0
Bank Sta=5004.1,5022.3
Exp/Cntr=0.3,0.1

Type RM Length L Ch R = 1,18773,554,554,554
BEGIN DESCRIPTION:
Harriet Creek 32.0
END DESCRIPTION:
XS GIS Cut Line= 3
      2325129.00      7066210.03      2325229.00      7064960.00
      2324729.01      7064160.01
#Sta/Elev= 30
  3746.3  708.52  3896.8  704.98  4237.9  701.46  4278.0  699.76  4428.5  698.97
  4468.6  696.50  4599.0  692.48  4887.5  690.23  4930.1  691.28  4960.2  689.57
  4980.3  683.74  4981.1  682.11  4983.1  681.61  4999.4  682.11  5013.9  683.75
  5035.7  689.39  5065.8  688.37  5123.6  689.82  5138.9  692.12  5153.6  692.51
  5160.6  694.63  5312.2  694.46  5342.3  695.68  5370.0  699.21  5385.3  699.77
  5413.1  699.46  5427.8  697.39  5443.1  699.71  5647.1  704.05  5943.7  714.37
#Mann=5,-1,0
  3746.3    0.05       0  4887.5    0.12       0  4981.1    0.07       0
  4999.4    0.12       0  5160.6    0.05       0
Bank Sta=4981.1,4999.4
Exp/Cntr=0.3,0.1

Type RM Length L Ch R = 1,18219,819,819,819
BEGIN DESCRIPTION:
Harriet Creek 31.0
END DESCRIPTION:
XS GIS Cut Line= 3
      2325329.01      7066159.96      2325729.00      7064910.00
      2324928.99      7064159.99
#Sta/Elev= 30
  3688.0  707.49  4298.6  700.37  4370.4  700.92  4380.9  699.49  4459.3  698.48
  4491.5  695.03  4496.8  695.61  4517.4  692.78  4555.8  690.38  4727.4  690.54
  4882.6  687.42  4923.4  688.17  4958.4  688.46  4979.1  681.36  4980.8  679.89
  4982.8  679.39  4999.1  679.89  5014.3  683.21  5035.8  682.95  5050.0  684.75
  5056.8  686.73  5078.3  687.93  5085.2  689.29  5156.0  690.98  5191.6  690.36
  5216.3  693.37  5410.9  694.63  5566.3  698.16  5700.6  699.49  6097.0  709.87
#Mann=5,-1,0
  3688.0    0.05       0  4923.4    0.12       0  4980.8    0.07       0
  4999.1    0.12       0  5216.3    0.05       0
Bank Sta=4980.8,4999.1
Exp/Cntr=0.3,0.1

Type RM Length L Ch R = 1,17400,257,257,257
BEGIN DESCRIPTION:
Harriet Creek 30.0
END DESCRIPTION:
XS GIS Cut Line= 3
      2327095.93      7065354.78      2326788.67      7065063.14
      2325779.56      7064043.63
#Sta/Elev= 30
  3922.9  691.84  4228.3  690.37  4249.6  692.68  4511.1  687.96  4928.3  686.41
  5020.3  682.79  5027.3  679.68  5034.4  681.70  5046.4  678.27  5048.4  677.77
  5064.8  678.27  5076.9  682.99  5161.7  682.88  5225.3  686.81  5260.7  685.20
  5366.7  687.11  5402.1  689.92  5409.2  688.28  5416.3  690.91  5423.3  688.44
  5444.6  690.52  5451.6  687.88  5458.7  690.57  5465.7  688.53  5479.9  690.93
  5487.0  689.22  5494.0  694.26  5501.1  692.37  5508.2  694.52  5781.0  704.40
#Mann=3,-1,0
  3922.9    0.05       0  5046.4   0.033       0  5064.8    0.05       0
Bank Sta=5046.4,5064.8
Exp/Cntr=0.3,0.1

Type RM Length L Ch R = 1,17143,1195,1195,1195
BEGIN DESCRIPTION:
Harriet Creek 29.0
END DESCRIPTION:
XS GIS Cut Line= 3
      2326924.11      7064849.61      2326387.63      7064360.02
      2326080.36      7063948.59
#Sta/Elev= 30
  4276.8  688.73  4372.2  688.69  4379.0  687.47  4740.4  682.68  4782.9  684.41
  4846.5  684.24  4945.8  681.11  4985.8  675.89  4987.8  675.39  5004.3  675.89
  5009.3  677.63  5030.1  678.22  5038.5  680.03  5088.5  680.96  5115.6  689.94
  5123.9  689.87  5130.2  691.88  5144.8  692.01  5159.4  689.94  5194.8  690.84
  5202.8  688.31  5209.4  690.64  5224.0  692.10  5294.8  694.60  5430.3  704.30
  5438.7  708.05  5444.9  706.15  5452.4  709.46  5459.5  710.11  5516.6  710.28
#Mann=3,-1,0
  4276.8    0.05       0  4985.8    0.05       0  5004.3    0.05       0
Bank Sta=4985.8,5004.3
Exp/Cntr=0.3,0.1

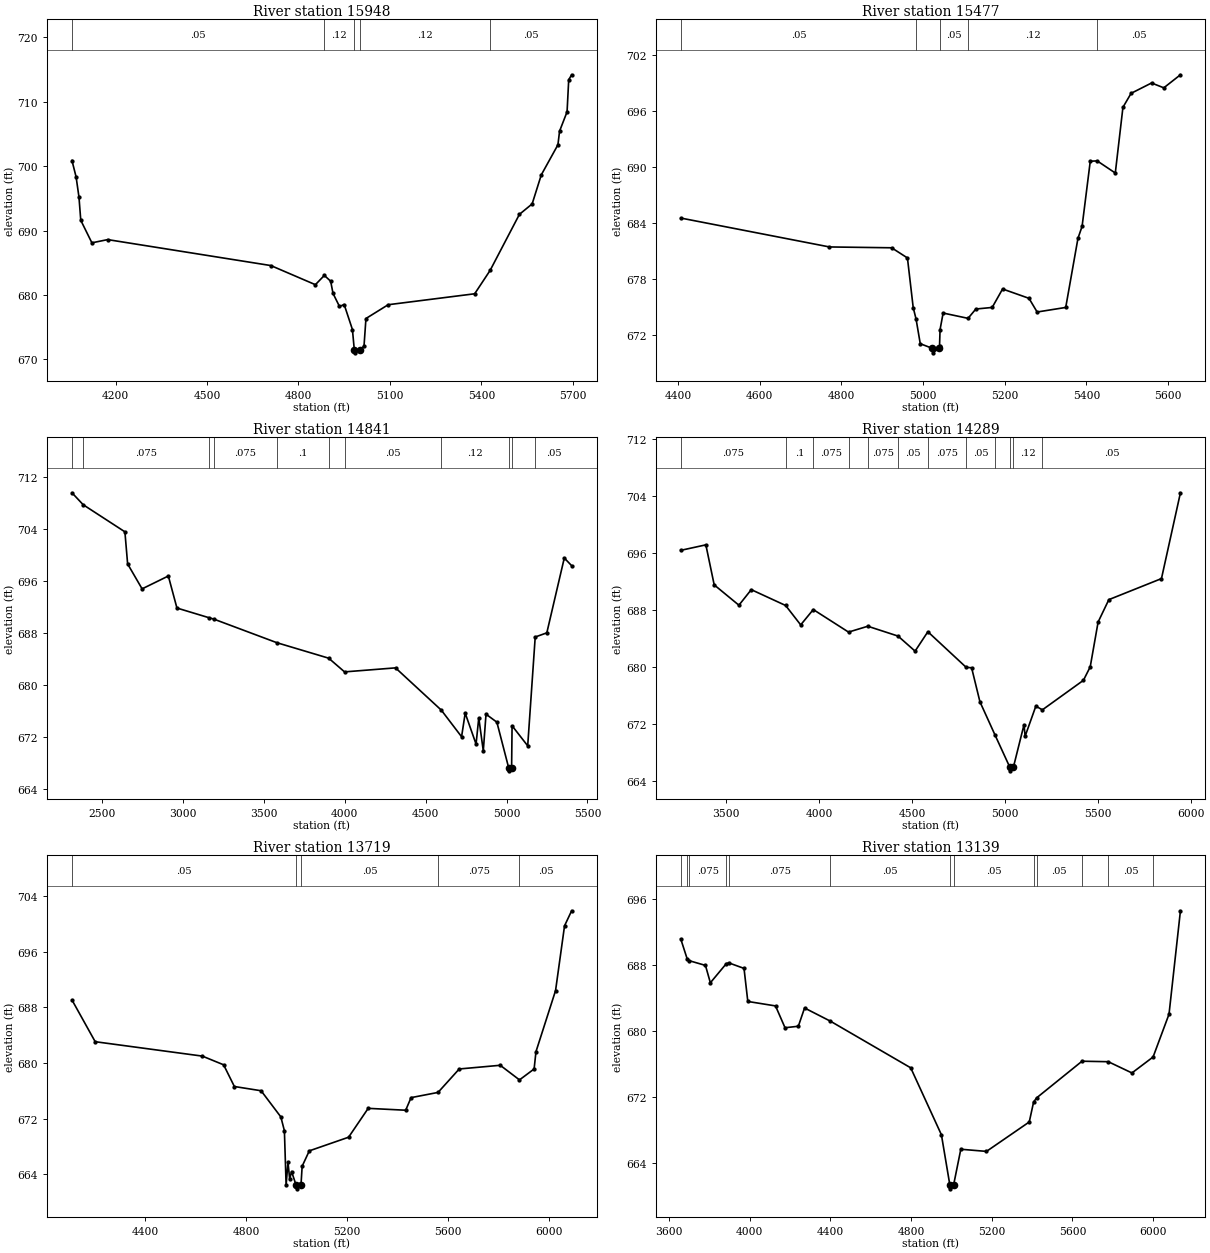
Type RM Length L Ch R = 1,15948,471,471,471
BEGIN DESCRIPTION:
Harriet Creek 28.0
END DESCRIPTION:
XS GIS Cut Line= 3
      2326929.00      7065009.99      2327429.00      7064210.00
      2327179.00      7063560.01
#Sta/Elev= 30
  4056.6  700.87  4070.2  698.32  4079.6  695.19  4085.5  691.59  4122.0  688.09
  4173.9  688.59  4709.3  684.56  4855.5  681.59  4884.8  683.03  4905.6  682.13
  4913.3  680.24  4934.5  678.21  4949.9  678.51  4977.0  674.63  4983.1  671.51
  4985.1  671.01  5001.6  671.51  5015.0  672.04  5021.4  676.34  5094.3  678.48
  5378.2  680.18  5428.9  683.81  5525.0  692.51  5566.8  694.13  5596.8  698.64
  5651.4  703.31  5656.8  705.43  5681.4  708.43  5686.8  713.41  5696.4  714.18
#Mann=5,-1,0
  4056.6    0.05       0  4884.8    0.12       0  4983.1    0.07       0
  5001.6    0.12       0  5428.9    0.05       0
Bank Sta=4983.1,5001.6
Exp/Cntr=0.3,0.1

Type RM Length L Ch R = 1,15477,636,636,636
BEGIN DESCRIPTION:
Harriet Creek 27.0
END DESCRIPTION:
XS GIS Cut Line= 4
      2327642.84      7064583.97      2327875.86      7064264.81
      2327799.74      7064040.10      2327778.00      7063449.32
#Sta/Elev= 30
  4406.6  684.53  4770.7  681.43  4923.0  681.34  4961.7  680.25  4975.8  674.93
  4982.8  673.70  4993.1  671.05  5021.6  670.57  5023.6  670.07  5040.1  670.57
  5040.3  670.84  5041.6  672.57  5049.1  674.34  5110.1  673.77  5129.2  674.77
  5169.2  674.94  5194.7  676.92  5259.3  675.92  5279.3  674.45  5349.3  674.94
  5379.3  682.36  5389.4  683.64  5409.4  690.63  5426.4  690.66  5470.7  689.36
  5489.4  696.41  5509.4  697.91  5559.5  699.02  5589.5  698.50  5630.2  699.90
#Mann=5,-1,0
  4406.6    0.05       0  4982.8    0.12       0  5040.3    0.05       0
  5110.1    0.12       0  5426.4    0.05       0
Bank Sta=5021.6,5040.1
Exp/Cntr=0.3,0.1

Type RM Length L Ch R = 1,14841,552,552,552
BEGIN DESCRIPTION:
Harriet Creek 26.0
END DESCRIPTION:
XS GIS Cut Line= 3
      2329429.00      7066059.99      2328229.00      7063660.00
      2327878.99      7063459.99
#Sta/Elev= 30
  2315.7  709.52  2385.0  707.68  2642.7  703.51  2659.5  698.57  2748.9  694.73
  2911.0  696.71  2964.1  691.78  3160.7  690.30  3193.6  690.06  3581.7  686.44
  3901.5  684.06  3999.5  681.95  4314.2  682.57  4597.2  676.06  4722.3  671.97
  4744.6  675.60  4811.7  670.84  4828.5  674.88  4856.4  669.79  4873.2  675.44
  4940.3  674.21  5012.8  667.22  5014.8  666.72  5031.3  667.22  5034.2  673.66
  5130.7  670.57  5177.1  687.32  5248.8  687.96  5356.7  699.48  5402.1  698.30
#Mann=11,-1,0
  2315.7    0.05       0  2385.0   0.075       0  3160.7    0.05       0
  3193.6   0.075       0  3581.7     0.1       0  3901.5   0.075       0
  3999.5    0.05       0  4597.2    0.12       0  5012.8    0.07       0
  5031.3    0.12       0  5177.1    0.05       0
Bank Sta=5012.8,5031.3
Exp/Cntr=0.3,0.1

Type RM Length L Ch R = 1,14289,570,570,570
BEGIN DESCRIPTION:
Harriet Creek 25.0
END DESCRIPTION:
XS GIS Cut Line= 3
      2329528.99      7065359.98      2328729.00      7063810.00
      2328229.03      7063010.04
#Sta/Elev= 30
  3256.2  696.38  3391.2  697.15  3436.1  691.54  3569.0  688.69  3635.5  690.87
  3820.3  688.65  3901.3  685.93  3969.0  688.08  4158.6  684.92  4262.3  685.74
  4425.0  684.36  4516.6  682.25  4585.3  684.97  4791.3  679.98  4820.6  679.92
  4865.4  675.15  4945.7  670.54  5026.3  665.97  5028.3  665.47  5045.3  665.97
  5102.5  671.94  5108.4  670.32  5166.1  674.54  5201.3  674.02  5422.0  678.16
  5458.6  680.05  5501.0  686.33  5558.8  689.47  5841.8  692.42  5943.8  704.45
#Mann=12,-1,0
  3256.2   0.075       0  3820.3     0.1       0  3969.0   0.075       0
  4158.6     0.1       0  4262.3   0.075       0  4425.0    0.05       0
  4585.3   0.075       0  4791.3    0.05       0  4945.7    0.12       0
  5026.3    0.07       0  5045.3    0.12       0  5201.3    0.05       0
Bank Sta=5026.3,5045.3
Exp/Cntr=0.3,0.1

Type RM Length L Ch R = 1,13719,580,580,580
BEGIN DESCRIPTION:
Harriet Creek 24.0
END DESCRIPTION:
XS GIS Cut Line= 3
      2329879.00      7064210.00      2329229.00      7063610.00
      2328428.98      7062859.98
#Sta/Elev= 30
  4110.3  689.06  4202.4  683.06  4627.2  680.99  4711.6  679.74  4754.2  676.62
  4860.2  676.01  4938.5  672.25  4952.6  670.26  4959.4  662.47  4966.8  665.74
  4973.6  663.30  4981.0  664.40  4999.3  662.41  5001.3  661.91  5018.3  662.41
  5023.0  665.16  5051.3  667.37  5207.1  669.33  5284.8  673.48  5433.5  673.21
  5454.8  675.02  5561.8  675.77  5645.8  679.14  5808.4  679.67  5884.7  677.57
  5942.7  679.14  5950.1  681.63  6027.7  690.40  6063.4  699.72  6091.5  701.88
#Mann=5,-1,0
  4110.3    0.05       0  4999.3   0.033       0  5018.3    0.05       0
  5561.8   0.075       0  5884.7    0.05       0
Bank Sta=4999.3,5018.3
Exp/Cntr=0.3,0.1

Type RM Length L Ch R = 1,13139,541,541,541
BEGIN DESCRIPTION:
Harriet Creek 23.0
END DESCRIPTION:
XS GIS Cut Line= 3
      2330129.01      7064460.01      2329629.00      7063210.00
      2328828.98      7062409.98
#Sta/Elev= 30
  3658.0  691.12  3689.8  688.71  3700.2  688.49  3780.5  687.92  3804.8  685.82
  3883.8  688.13  3895.9  688.23  3971.7  687.56  3990.5  683.56  4127.9  683.02
  4175.0  680.38  4241.0  680.56  4271.9  682.77  4400.4  681.17  4798.3  675.53
  4950.5  667.43  4992.1  661.39  4994.1  660.89  5011.2  661.39  5046.7  665.68
  5174.0  665.42  5386.1  668.98  5407.5  671.38  5422.3  671.89  5647.7  676.33
  5778.0  676.27  5895.3  674.91  6000.1  676.84  6079.1  682.02  6135.7  694.53
#Mann=13,-1,0
  3658.0   0.075       0  3689.8    0.05       0  3700.2   0.075       0
  3883.8    0.05       0  3895.9   0.075       0  4400.4    0.05       0
  4992.1   0.033       0  5011.2    0.05       0  5407.5   0.075       0
  5422.3    0.05       0  5647.7   0.075       0  5778.0    0.05       0
  6000.1    0.12       0
Bank Sta=4992.1,5011.2
Exp/Cntr=0.3,0.1

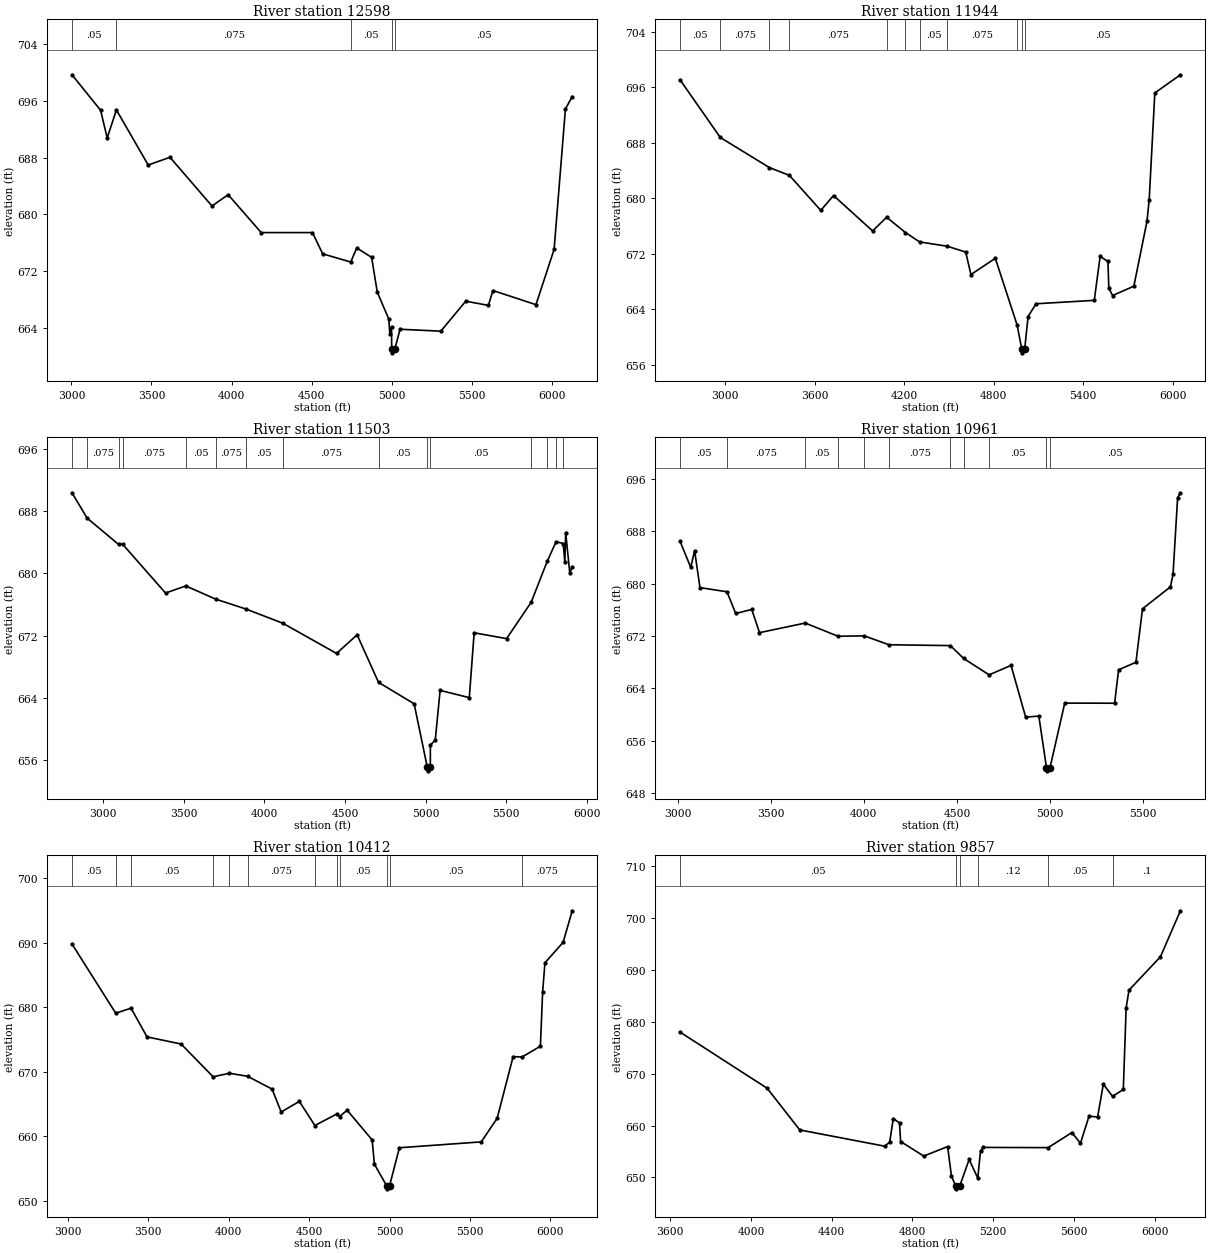
Type RM Length L Ch R = 1,12598,654,654,654
BEGIN DESCRIPTION:
Harriet Creek 22.0
END DESCRIPTION:
XS GIS Cut Line= 3
      2331228.97      7064409.97      2329979.00      7062860.00
      2329178.97      7062059.97
#Sta/Elev= 30
  3003.8  699.71  3182.1  694.71  3223.7  690.79  3281.0  694.75  3479.6  686.97
  3615.5  688.06  3877.8  681.18  3978.6  682.78  4184.9  677.43  4504.8  677.43
  4568.7  674.43  4743.8  673.27  4781.5  675.26  4874.2  673.93  4909.4  669.03
  4981.4  665.21  4987.8  663.13  4998.5  664.16  4999.5  660.95  5001.5  660.45
  5018.7  660.95  5051.6  663.78  5306.1  663.51  5461.7  667.74  5603.1  667.15
  5631.4  669.25  5900.1  667.25  6013.2  675.05  6083.9  694.87  6126.4  696.64
#Mann=5,-1,0
  3003.8    0.05       0  3281.0   0.075       0  4743.8    0.05       0
  4999.5   0.035       0  5018.7    0.05       0
Bank Sta=4999.5,5018.7
Exp/Cntr=0.3,0.1

Type RM Length L Ch R = 1,11944,441,441,441
BEGIN DESCRIPTION:
Harriet Creek 21.0
END DESCRIPTION:
XS GIS Cut Line= 3
      2331629.00      7063910.00      2330217.38      7062278.26
      2329075.10      7061922.51
#Sta/Elev= 30
  2697.7  697.07  2966.6  688.78  3296.1  684.43  3430.1  683.31  3640.4  678.26
  3725.9  680.40  3988.1  675.29  4082.0  677.27  4208.4  675.06  4303.0  673.71
  4488.4  673.09  4612.1  672.25  4647.3  669.00  4810.7  671.35  4956.8  661.73
  4988.3  658.21  4990.3  657.71  5007.5  658.21  5030.4  662.95  5084.0  664.79
  5474.2  665.28  5513.5  671.61  5565.8  670.89  5571.8  667.03  5597.2  665.98
  5739.6  667.32  5827.7  676.69  5842.5  679.80  5880.2  695.20  6051.7  697.82
#Mann=11,-1,0
  2697.7    0.05       0  2966.6   0.075       0  3296.1    0.05       0
  3430.1   0.075       0  4082.0    0.05       0  4208.4   0.075       0
  4303.0    0.05       0  4488.4   0.075       0  4956.8    0.05       0
  4988.3   0.035       0  5007.5    0.05       0
Bank Sta=4988.3,5007.5
Exp/Cntr=0.3,0.1

Type RM Length L Ch R = 1,11503,542,542,542
BEGIN DESCRIPTION:
Harriet Creek 20.0
END DESCRIPTION:
XS GIS Cut Line= 3
      2331579.03      7063360.03      2330029.00      7061810.00
      2329123.84      7061720.98
#Sta/Elev= 30
  2807.5  690.32  2901.3  687.07  3096.1  683.70  3121.9  683.71  3387.4  677.46
  3513.3  678.37  3698.0  676.68  3884.5  675.42  4115.3  673.58  4448.0  669.71
  4575.3  672.10  4708.1  666.00  4928.9  663.25  5010.1  655.15  5012.1  654.65
  5029.3  655.15  5029.7  657.96  5059.9  658.60  5090.0  664.97  5270.9  664.04
  5301.0  672.36  5502.0  671.61  5654.5  676.27  5753.7  681.51  5809.3  684.05
  5853.0  683.81  5863.4  681.42  5868.4  685.22  5893.9  680.03  5909.1  680.79
#Mann=15,-1,0
  2807.5    0.05       0  2901.3   0.075       0  3096.1    0.05       0
  3121.9   0.075       0  3513.3    0.05       0  3698.0   0.075       0
  3884.5    0.05       0  4115.3   0.075       0  4708.1    0.05       0
  5010.1   0.033       0  5029.3    0.05       0  5654.5   0.075       0
  5753.7    0.05       0  5809.3   0.075       0  5853.0    0.05       0
Bank Sta=5010.1,5029.3
Exp/Cntr=0.3,0.1

Type RM Length L Ch R = 1,10961,549,549,549
BEGIN DESCRIPTION:
Harriet Creek 19.0
END DESCRIPTION:
XS GIS Cut Line= 3
      2331678.98      7063059.98      2330429.00      7061510.00
      2329779.02      7061260.01
#Sta/Elev= 30
  3013.2  686.46  3070.0  682.49  3090.8  685.07  3119.5  679.41  3264.8  678.77
  3311.5  675.45  3397.8  676.07  3439.4  672.52  3685.1  673.99  3861.4  671.97
  4002.3  672.03  4135.0  670.67  4465.1  670.54  4535.7  668.59  4672.8  666.07
  4790.9  667.51  4869.3  659.61  4940.2  659.76  4981.2  651.89  4983.2  651.39
  5000.4  651.89  5079.4  661.75  5347.3  661.73  5368.7  666.84  5461.9  667.99
  5497.2  676.17  5647.2  679.52  5661.2  681.44  5685.8  693.15  5700.8  693.91
#Mann=11,-1,0
  3013.2    0.05       0  3264.8   0.075       0  3685.1    0.05       0
  3861.4   0.075       0  4002.3    0.05       0  4135.0   0.075       0
  4465.1    0.05       0  4535.7   0.075       0  4672.8    0.05       0
  4981.2   0.033       0  5000.4    0.05       0
Bank Sta=4981.2,5000.4
Exp/Cntr=0.3,0.1

Type RM Length L Ch R = 1,10412,555,555,555
BEGIN DESCRIPTION:
Harriet Creek 18.0
END DESCRIPTION:
XS GIS Cut Line= 3
      2332329.01      7062760.01      2330929.00      7061360.00
      2330128.99      7060559.99
#Sta/Elev= 30
  3025.1  689.84  3297.1  679.11  3392.3  679.89  3491.8  675.44  3703.9  674.33
  3903.0  669.25  4004.1  669.80  4117.2  669.33  4269.6  667.34  4326.2  663.79
  4439.3  665.44  4535.6  661.70  4672.3  663.49  4689.3  663.08  4736.3  664.08
  4891.9  659.46  4906.0  655.71  4981.3  652.38  4983.3  651.88  5000.5  652.38
  5061.6  658.25  5570.7  659.16  5669.7  662.83  5768.7  672.38  5824.4  672.32
  5938.4  673.99  5952.5  682.46  5966.7  686.92  6079.8  690.10  6136.4  694.99
#Mann=12,-1,0
  3025.1    0.05       0  3297.1   0.075       0  3392.3    0.05       0
  3903.0   0.075       0  4004.1    0.05       0  4117.2   0.075       0
  4535.6    0.05       0  4672.3   0.075       0  4689.3    0.05       0
  4981.3   0.033       0  5000.5    0.05       0  5824.4   0.075       0
Bank Sta=4981.3,5000.5
Exp/Cntr=0.3,0.1

Type RM Length L Ch R = 1,9857,550,550,550
BEGIN DESCRIPTION:
Harriet Creek 17.0
END DESCRIPTION:
XS GIS Cut Line= 3
      2332579.04      7061560.02      2331329.00      7061060.00
      2330529.00      7060260.00
#Sta/Elev= 30
  3649.4  678.02  4080.3  667.20  4241.8  659.16  4663.2  656.02  4687.4  656.85
  4704.9  661.36  4735.9  660.52  4741.3  656.93  4855.7  654.12  4974.2  655.96
  4993.0  650.28  5014.3  648.30  5016.3  647.80  5033.7  648.30  5080.6  653.46
  5123.4  649.87  5137.2  655.15  5151.3  655.79  5472.0  655.75  5589.7  658.66
  5632.1  656.59  5674.6  661.82  5717.0  661.66  5745.3  667.98  5791.1  665.64
  5844.3  666.97  5858.4  682.74  5872.5  686.13  6028.1  692.56  6127.1  701.44
#Mann=6,-1,0
  3649.4    0.05       0  5014.3   0.033       0  5033.7    0.05       0
  5123.4    0.12       0  5472.0    0.05       0  5791.1     0.1       0
Bank Sta=5014.3,5033.7
Exp/Cntr=0.3,0.1