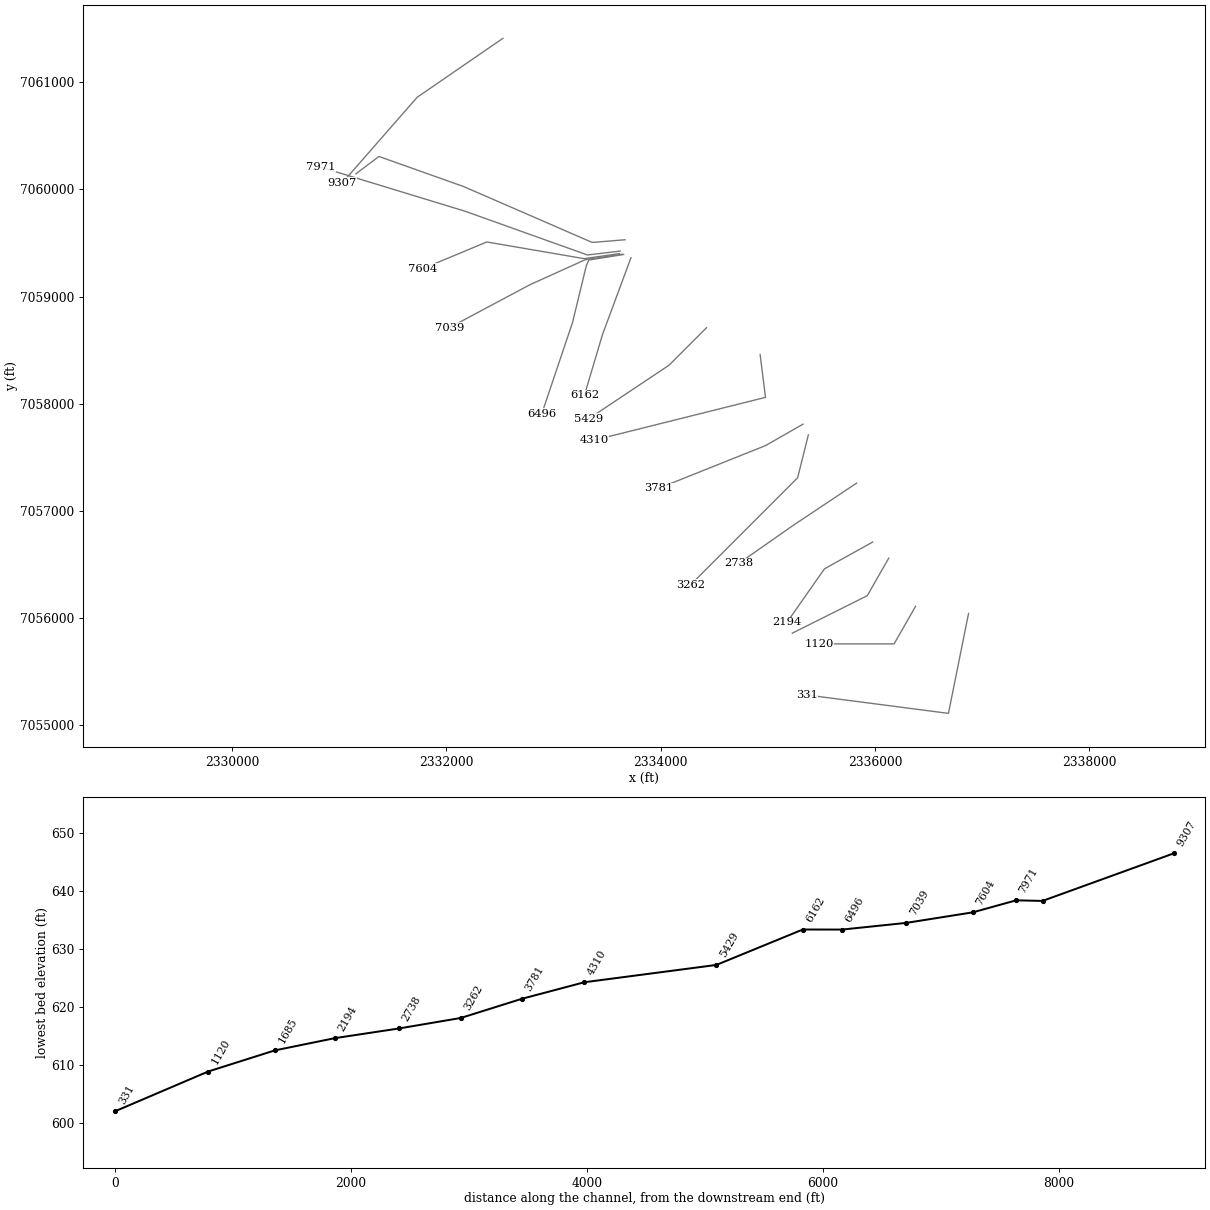
HEC-RAS study Harriet Creek.prj: Harriet Creek Base Level Engineering

--- Harriet Creek.g01 (geometry) --- (continued)

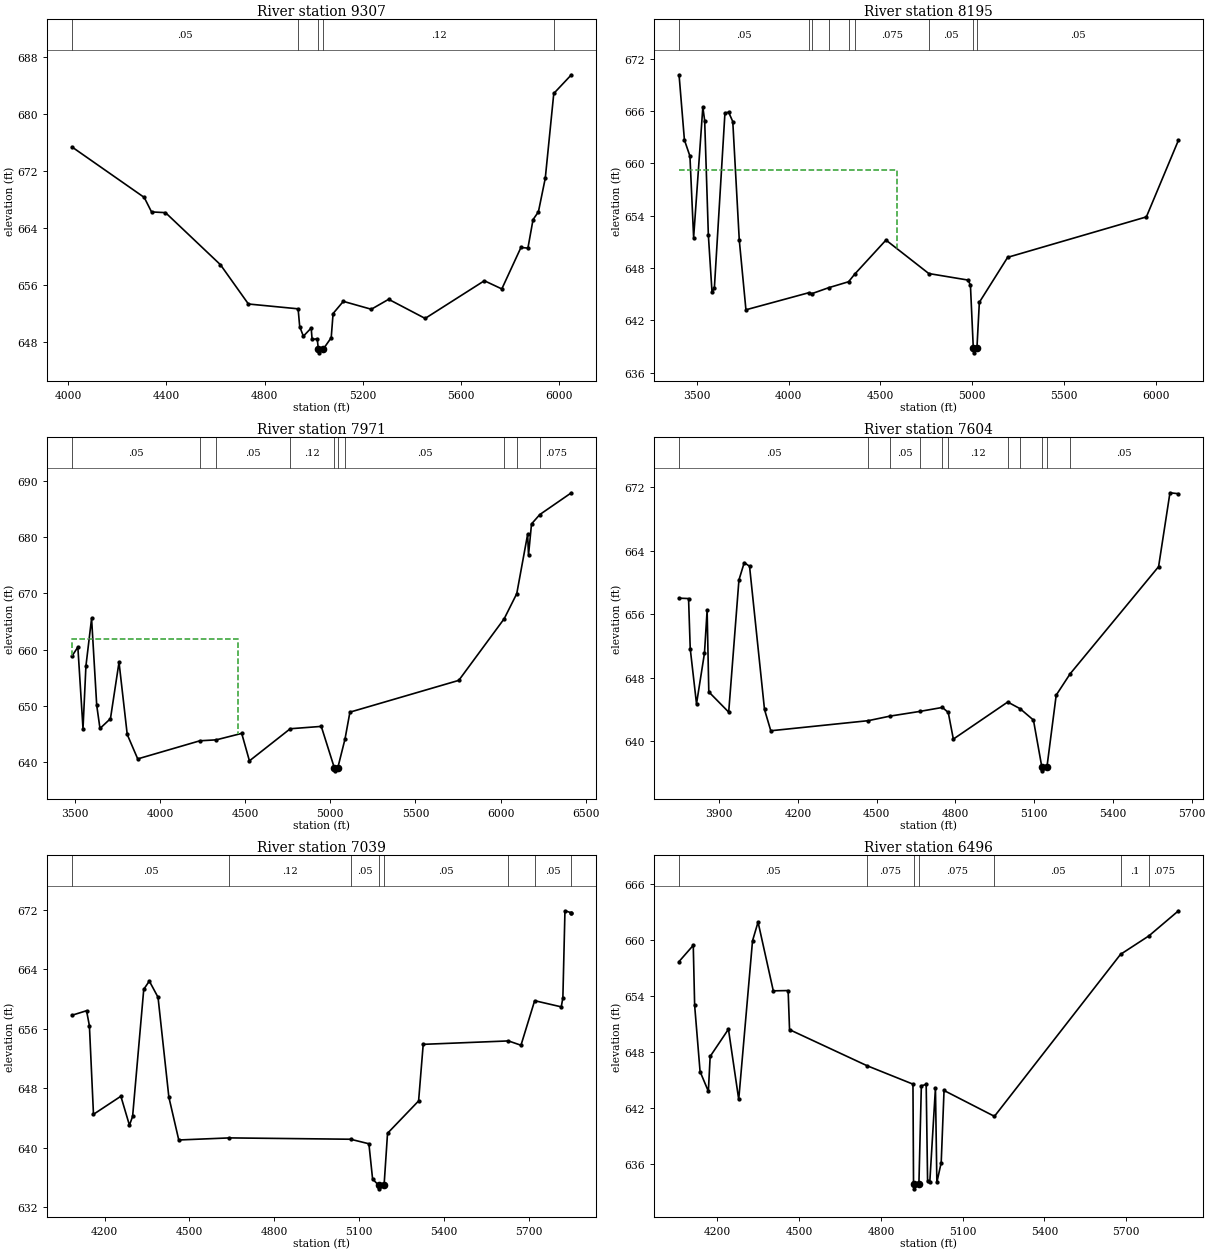
Type RM Length L Ch R = 1,9307,1112,1112,1112
BEGIN DESCRIPTION:
Harriet Creek 16.0
END DESCRIPTION:
XS GIS Cut Line= 3
      2332529.01      7061410.01      2331729.00      7060860.00
      2331029.03      7060060.04
#Sta/Elev= 30
  4015.3  675.41  4309.6  668.31  4339.4  666.27  4396.2  666.17  4620.1  658.84
  4733.8  653.32  4936.3  652.64  4942.8  650.13  4957.7  648.79  4989.5  649.94
  4993.3  648.33  5014.1  648.43  5018.7  646.95  5020.7  646.45  5038.1  646.95
  5071.1  648.58  5078.7  651.98  5120.4  653.69  5234.3  652.58  5305.0  653.98
  5453.6  651.29  5694.7  656.59  5765.8  655.44  5843.7  661.27  5872.1  661.18
  5893.0  665.19  5914.8  666.28  5942.8  671.01  5977.4  682.93  6049.1  685.56
#Mann=5,-1,0
  4015.3    0.05       0  4936.3    0.12       0  5018.7    0.07       0
  5038.1    0.12       0  5977.4   0.075       0
Bank Sta=5018.7,5038.1
Exp/Cntr=0.3,0.1

Type RM Length L Ch R = 1,8195,224,224,224
BEGIN DESCRIPTION:
Harriet Creek 15.0
END DESCRIPTION:
XS GIS Cut Line= 6
      2333668.12      7059530.73      2333378.89      7059506.76
      2333355.83      7059508.35      2332163.67      7060026.68
      2331372.01      7060307.93      2331158.43      7060146.45
#Sta/Elev= 30
  3403.4  670.17  3432.6  662.69  3462.7  660.83  3482.8  651.49  3533.0  666.46
  3543.0  664.90  3563.1  651.76  3583.1  645.21  3596.0  645.75  3653.4  665.77
  3673.4  665.88  3696.1  664.80  3731.5  651.21  3767.8  643.20  4108.7  645.15
  4128.0  645.06  4218.0  645.73  4327.2  646.42  4360.0  647.28  4530.8  651.20
  4764.1  647.36  4978.2  646.61  4991.0  646.03  5006.7  638.76  5008.7  638.26
  5026.3  638.76  5039.6  644.06  5193.8  649.22  5949.6  653.86  6124.6  662.67
#Mann=9,-1,0
  3403.4    0.05       0  4108.7   0.075       0  4128.0    0.05       0
  4218.0   0.075       0  4327.2    0.05       0  4360.0   0.075       0
  4764.1    0.05       0  5006.7    0.05       0  5026.3    0.05       0
#XS Ineff=2,0
    0.00 4592.00  659.21               0
Permanent Ineff=
       F       F
Bank Sta=5006.7,5026.3
Exp/Cntr=0.3,0.1

Type RM Length L Ch R = 1,7971,367,367,367
BEGIN DESCRIPTION:
Harriet Creek 14.0
END DESCRIPTION:
XS GIS Cut Line= 4
      2333623.49      7059424.95      2333318.11      7059388.57
      2332174.09      7059797.52      2330825.10      7060208.98
#Sta/Elev= 30
  3482.6  658.82  3517.3  660.44  3547.5  645.90  3564.7  657.07  3597.9  665.54
  3628.1  650.03  3647.2  645.92  3708.7  647.67  3759.0  657.73  3807.2  644.85
  3868.8  640.49  4233.6  643.72  4330.0  643.89  4479.5  645.04  4524.8  640.14
  4764.5  645.87  4946.7  646.29  5023.8  638.86  5025.8  638.36  5043.4  638.86
  5086.0  644.03  5114.9  648.83  5754.2  654.50  6021.1  665.51  6094.6  669.97
  6158.5  680.56  6163.7  676.88  6181.3  682.41  6229.8  684.08  6415.4  687.97
#Mann=10,-1,0
  3482.6    0.05       0  4233.6    0.12       0  4330.0    0.05       0
  4764.5    0.12       0  5023.8    0.07       0  5043.4    0.12       0
  5086.0    0.05       0  6021.1   0.075       0  6094.6    0.05       0
  6229.8   0.075       0
#XS Ineff=2,0
    0.00 4458.10  661.90               0
Permanent Ineff=
       F       F
Bank Sta=5023.8,5043.4
Exp/Cntr=0.3,0.1

Type RM Length L Ch R = 1,7604,565,565,565
BEGIN DESCRIPTION:
Harriet Creek 13.0
END DESCRIPTION:
XS GIS Cut Line= 4
      2333614.83      7059401.20      2333286.81      7059354.38
      2332379.00      7059510.00      2331779.00      7059260.00
#Sta/Elev= 30
  3747.6  658.05  3783.8  658.00  3790.2  651.68  3814.1  644.73  3844.4  651.12
  3854.5  656.54  3860.9  646.24  3936.7  643.69  3975.7  660.34  3995.9  662.53
  4016.1  662.07  4073.1  644.02  4097.0  641.34  4467.9  642.61  4551.8  643.19
  4665.0  643.78  4750.6  644.28  4773.0  643.65  4792.4  640.29  4999.5  644.96
  5046.7  644.12  5097.5  642.69  5129.4  636.79  5131.4  636.29  5149.0  636.79
  5184.2  645.83  5237.1  648.51  5574.2  662.02  5617.5  671.33  5650.0  671.21
#Mann=11,-1,0
  3747.6    0.05       0  4467.9    0.12       0  4551.8    0.05       0
  4665.0    0.12       0  4750.6    0.05       0  4773.0    0.12       0
  4999.5    0.05       0  5046.7    0.12       0  5129.4   0.033       0
  5149.0    0.12       0  5237.1    0.05       0
Bank Sta=5129.4,5149
Exp/Cntr=0.3,0.1

Type RM Length L Ch R = 1,7039,543,543,543
BEGIN DESCRIPTION:
Harriet Creek 12.0
END DESCRIPTION:
XS GIS Cut Line= 4
      2333639.98      7059396.16      2333298.30      7059345.02
      2332779.00      7059110.00      2332029.00      7058710.00
#Sta/Elev= 30
  4084.5  657.81  4136.1  658.42  4146.2  656.40  4160.6  644.49  4257.4  646.92
  4287.7  643.03  4298.9  644.20  4338.3  661.30  4358.0  662.41  4388.8  660.23
  4427.1  646.80  4462.1  641.04  4641.4  641.32  5069.4  641.14  5134.2  640.53
  5147.3  635.78  5168.3  634.97  5170.3  634.47  5187.9  634.97  5200.1  641.94
  5309.9  646.29  5326.2  653.90  5627.5  654.36  5671.8  653.78  5720.2  659.77
  5814.2  658.94  5819.9  660.15  5827.3  671.86  5849.1  671.60  5850.0  671.60
#Mann=8,-1,0
  4084.5    0.05       0  4641.4    0.12       0  5069.4    0.05       0
  5168.3    0.07       0  5187.9    0.05       0  5627.5   0.075       0
  5720.2    0.05       0  5849.1   0.075       0
Bank Sta=5168.3,5187.9
Exp/Cntr=0.3,0.1

Type RM Length L Ch R = 1,6496,334,334,334
BEGIN DESCRIPTION:
Harriet Creek 11.0
END DESCRIPTION:
XS GIS Cut Line= 5
      2333655.13      7059393.28      2333331.31      7059341.47
      2333307.93      7059291.01      2333179.00      7058760.00
      2332891.11      7057905.16
#Sta/Elev= 30
  4059.5  657.68  4111.6  659.42  4116.7  652.98  4136.6  645.89  4167.0  643.77
  4173.6  647.51  4240.7  650.43  4278.4  642.90  4329.0  659.90  4349.3  661.91
  4405.2  654.54  4459.6  654.57  4464.8  650.38  4748.7  646.52  4917.5  644.54
  4919.6  633.82  4921.6  633.32  4939.3  633.82  4948.3  644.36  4966.0  644.51
  4971.2  634.14  4979.2  634.02  5000.0  644.13  5005.2  634.02  5021.1  636.13
  5031.5  643.86  5216.4  641.09  5678.9  658.45  5783.0  660.43  5891.5  663.12
#Mann=7,-1,0
  4059.5    0.05       0  4748.7   0.075       0  4919.6    0.07       0
  4939.3   0.075       0  5216.4    0.05       0  5678.9     0.1       0
  5783.0   0.075       0
Bank Sta=4919.6,4939.3
Exp/Cntr=0.3,0.1

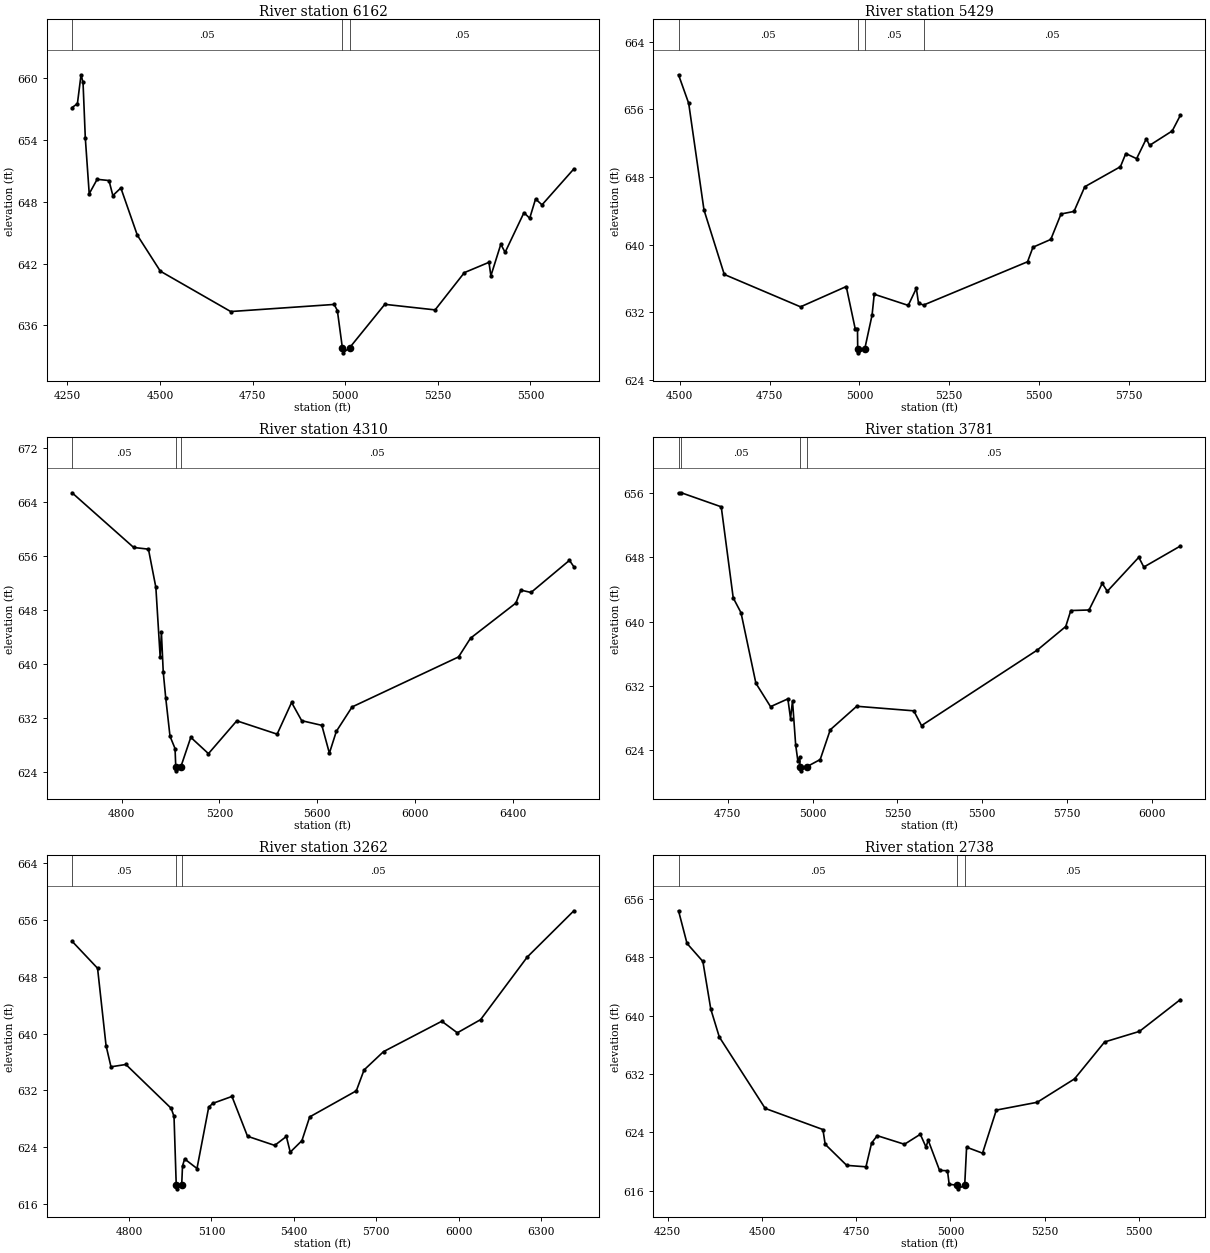
Type RM Length L Ch R = 1,6162,733,733,733
BEGIN DESCRIPTION:
Harriet Creek 10.0
END DESCRIPTION:
XS GIS Cut Line= 3
      2333723.99      7059363.46      2333457.08      7058643.00
      2333289.97      7058080.93
#Sta/Elev= 30
  4262.4  657.15  4276.8  657.52  4286.6  660.33  4292.0  659.59  4298.1  654.22
  4308.7  648.78  4330.1  650.18  4362.1  650.06  4372.5  648.60  4394.1  649.34
  4438.6  644.75  4500.7  641.26  4690.7  637.34  4969.9  638.03  4978.6  637.44
  4992.1  633.83  4994.1  633.33  5011.8  633.83  5106.7  638.04  5242.5  637.50
  5321.5  641.12  5387.9  642.12  5393.1  640.81  5419.9  643.87  5431.5  643.09
  5482.4  646.94  5497.9  646.40  5513.7  648.27  5531.1  647.70  5617.1  651.19
#Mann=3,-1,0
  4262.4    0.05       0  4992.1   0.033       0  5011.8    0.05       0
Bank Sta=4992.1,5011.8
Exp/Cntr=0.3,0.1

Type RM Length L Ch R = 1,5429,1119,1119,1119
BEGIN DESCRIPTION:
Harriet Creek 9.0
END DESCRIPTION:
XS GIS Cut Line= 3
      2334429.03      7058710.03      2334079.00      7058360.00
      2333329.01      7057860.00
#Sta/Elev= 30
  4496.6  660.10  4524.9  656.72  4567.4  644.12  4623.9  636.49  4836.1  632.66
  4963.3  635.06  4988.1  630.09  4994.6  630.09  4995.2  627.72  4997.2  627.22
  5015.0  627.72  5035.2  631.69  5041.2  634.15  5135.8  632.83  5158.4  634.85
  5164.4  633.09  5178.4  632.87  5467.9  637.99  5482.9  639.71  5532.5  640.63
  5561.0  643.64  5597.1  643.94  5627.1  646.86  5726.3  649.23  5741.3  650.79
  5771.3  650.18  5798.4  652.54  5807.4  651.75  5870.5  653.46  5893.0  655.30
#Mann=4,-1,0
  4496.6    0.05       0  4995.2   0.033       0  5015.0    0.05       0
  5178.4    0.05       0
Bank Sta=4995.2,5015
Exp/Cntr=0.3,0.1

Type RM Length L Ch R = 1,4310,529,529,529
BEGIN DESCRIPTION:
Harriet Creek 8.0
END DESCRIPTION:
XS GIS Cut Line= 3
      2334929.00      7058460.03      2334979.00      7058060.00
      2333378.99      7057660.00
#Sta/Elev= 30
  4597.6  665.32  4849.6  657.24  4910.0  656.99  4940.3  651.35  4957.9  641.08
  4963.0  644.69  4970.5  638.84  4980.6  635.04  4998.2  629.35  5018.8  627.53
  5021.8  624.74  5023.8  624.24  5041.6  624.74  5083.2  629.19  5155.4  626.78
  5271.3  631.63  5436.3  629.66  5495.5  634.34  5536.8  631.65  5619.2  630.96
  5650.1  626.85  5678.5  630.07  5742.9  633.68  6178.4  641.07  6227.4  643.84
  6412.9  649.03  6433.5  650.94  6474.8  650.59  6632.0  655.34  6650.0  654.39
#Mann=3,-1,0
  4597.6    0.05       0  5021.8   0.033       0  5041.6    0.05       0
Bank Sta=5021.8,5041.6
Exp/Cntr=0.3,0.1

Type RM Length L Ch R = 1,3781,519,519,519
BEGIN DESCRIPTION:
Harriet Creek 7.0
END DESCRIPTION:
XS GIS Cut Line= 3
      2335329.01      7057810.01      2334979.00      7057610.00
      2333978.97      7057209.99
#Sta/Elev= 30
  4604.6  655.99  4612.8  656.05  4730.6  654.30  4765.9  642.95  4788.9  641.10
  4832.8  632.31  4876.0  629.39  4927.1  630.36  4935.0  627.91  4940.8  630.11
  4950.1  624.63  4956.6  622.63  4962.4  623.10  4962.6  621.89  4964.6  621.39
  4982.4  621.89  5022.5  622.80  5052.2  626.51  5130.2  629.44  5298.5  628.87
  5321.4  627.03  5663.4  636.46  5746.8  639.38  5761.7  641.37  5815.5  641.44
  5854.5  644.75  5869.4  643.77  5962.3  648.01  5977.1  646.79  6084.8  649.41
#Mann=4,-1,0
  4604.6     0.1       0  4612.8    0.05       0  4962.6   0.033       0
  4982.4    0.05       0
Bank Sta=4962.6,4982.4
Exp/Cntr=0.3,0.1

Type RM Length L Ch R = 1,3262,524,524,524
BEGIN DESCRIPTION:
Harriet Creek 6.0
END DESCRIPTION:
XS GIS Cut Line= 3
      2335379.00      7057710.01      2335279.00      7057310.00
      2334279.02      7056310.02
#Sta/Elev= 30
  4592.7  653.02  4685.5  649.21  4716.4  638.29  4734.4  635.30  4788.6  635.63
  4953.5  629.44  4963.8  628.29  4971.9  618.58  4973.9  618.08  4991.7  618.58
  4994.7  621.30  5002.4  622.30  5047.4  620.95  5089.9  629.57  5104.0  630.13
  5174.7  631.12  5231.3  625.50  5330.3  624.21  5372.7  625.47  5386.9  623.26
  5429.3  624.88  5457.6  628.23  5627.3  631.91  5655.6  634.86  5726.3  637.44
  5938.4  641.73  5995.0  640.10  6079.8  641.96  6249.5  650.79  6419.2  657.32
#Mann=3,-1,0
  4592.7    0.05       0  4971.9   0.033       0  4991.7    0.05       0
Bank Sta=4971.9,4991.7
Exp/Cntr=0.3,0.1

Type RM Length L Ch R = 1,2738,544,544,544
BEGIN DESCRIPTION:
Harriet Creek 5.0
END DESCRIPTION:
XS GIS Cut Line= 3
      2335829.00      7057260.00      2335229.00      7056860.00
      2334729.03      7056510.02
#Sta/Elev= 30
  4278.7  654.40  4301.2  649.92  4343.3  647.45  4364.3  640.91  4386.9  637.09
  4508.6  627.30  4661.8  624.40  4667.8  622.38  4724.9  619.49  4776.0  619.29
  4791.0  622.56  4806.0  623.56  4878.1  622.38  4920.2  623.75  4935.2  622.01
  4941.2  622.93  4971.3  618.80  4992.3  618.75  4996.8  616.89  5018.2  616.77
  5020.2  616.27  5038.0  616.77  5043.0  621.98  5085.3  621.16  5121.9  627.07
  5230.4  628.14  5329.4  631.35  5409.2  636.41  5501.6  637.86  5610.1  642.22
#Mann=3,-1,0
  4278.7    0.05       0  5018.2   0.033       0  5038.0    0.05       0
Bank Sta=5018.2,5038
Exp/Cntr=0.3,0.1

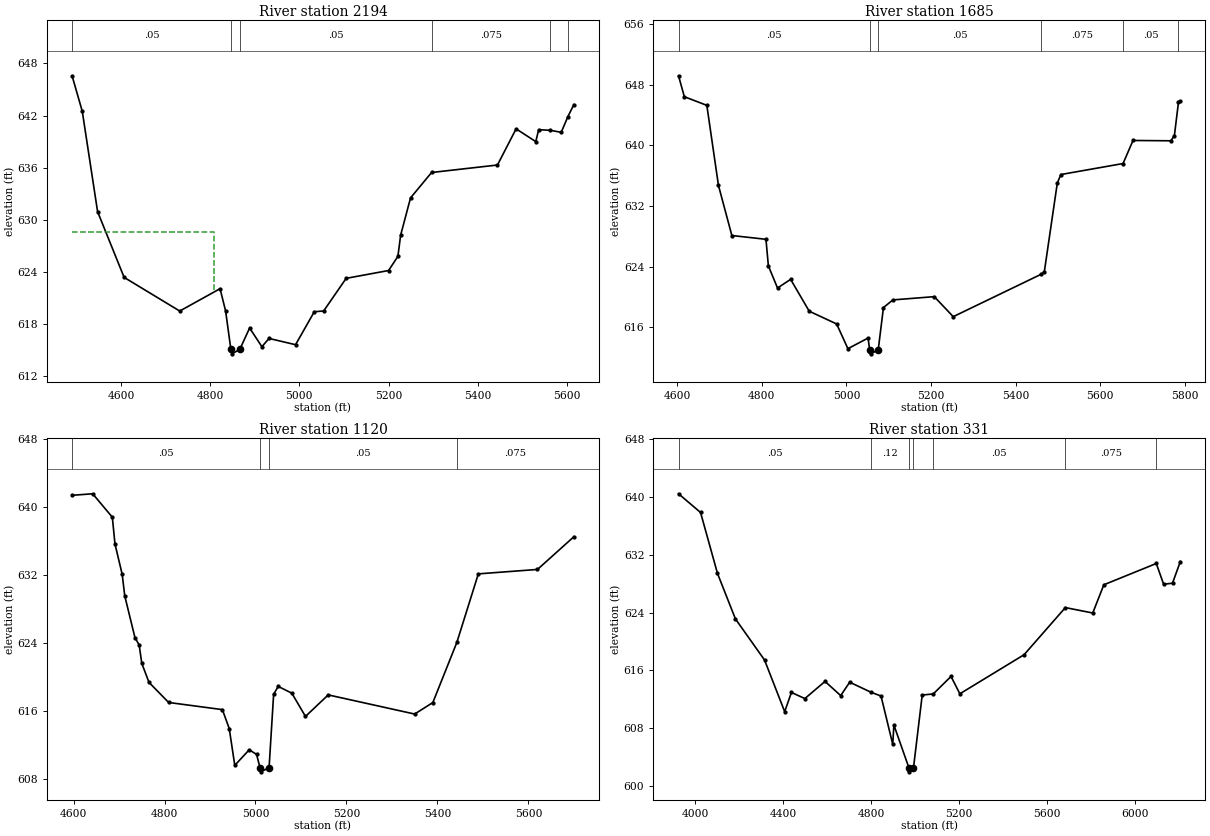
Type RM Length L Ch R = 1,2194,509,509,509
BEGIN DESCRIPTION:
Harriet Creek 4.0
END DESCRIPTION:
XS GIS Cut Line= 3
      2335979.01      7056710.00      2335529.00      7056460.00
      2335179.01      7055960.02
#Sta/Elev= 30
  4490.4  646.57  4513.3  642.48  4547.6  630.95  4607.1  623.39  4731.8  619.52
  4822.2  622.09  4834.7  619.52  4846.5  615.10  4848.5  614.60  4866.4  615.10
  4888.5  617.57  4916.0  615.42  4932.0  616.37  4991.5  615.65  5033.5  619.44
  5054.5  619.53  5105.0  623.28  5200.1  624.18  5221.0  625.81  5227.1  628.24
  5249.3  632.53  5296.5  635.45  5444.2  636.31  5486.0  640.47  5530.1  639.00
  5536.6  640.37  5562.8  640.30  5587.2  640.07  5602.0  641.86  5615.5  643.26
#Mann=6,-1,0
  4490.4    0.05       0  4846.5   0.033       0  4866.4    0.05       0
  5296.5   0.075       0  5562.8    0.05       0  5602.0   0.075       0
#XS Ineff=2,0
    0.00 4808.90  628.61               0
Permanent Ineff=
       F       F
Bank Sta=4846.5,4866.4
Exp/Cntr=0.3,0.1

Type RM Length L Ch R = 1,1685,565,565,565
BEGIN DESCRIPTION:
Harriet Creek 3.0
END DESCRIPTION:
XS GIS Cut Line= 3
      2336128.99      7056559.98      2335929.00      7056210.00
      2335229.02      7055860.01
#Sta/Elev= 30
  4603.3  649.15  4617.0  646.39  4670.2  645.25  4697.6  634.70  4729.3  628.09
  4809.9  627.59  4815.6  624.08  4837.2  621.17  4868.2  622.31  4912.1  618.11
  4976.9  616.43  5003.5  613.17  5051.1  614.57  5055.1  612.99  5057.1  612.49
  5075.1  612.99  5087.5  618.59  5109.8  619.60  5207.6  620.03  5252.4  617.39
  5460.8  623.00  5467.6  623.30  5498.3  635.00  5506.7  636.13  5653.7  637.58
  5677.2  640.62  5766.7  640.58  5775.0  641.27  5784.6  645.65  5789.0  645.81
#Mann=6,-1,0
  4603.3    0.05       0  5055.1   0.033       0  5075.1    0.05       0
  5460.8   0.075       0  5653.7    0.05       0  5784.6   0.075       0
Bank Sta=5055.1,5075.1
Exp/Cntr=0.3,0.1

Type RM Length L Ch R = 1,1120,789,789,789
BEGIN DESCRIPTION:
Harriet Creek 2.0
END DESCRIPTION:
XS GIS Cut Line= 3
      2336378.99      7056109.97      2336179.00      7055760.00
      2335478.98      7055760.00
#Sta/Elev= 30
  4596.8  641.34  4642.1  641.52  4685.3  638.77  4691.1  635.63  4706.9  632.07
  4712.7  629.50  4735.0  624.63  4744.3  623.76  4750.1  621.59  4765.9  619.36
  4809.1  617.00  4927.2  616.16  4942.3  613.94  4954.5  609.61  4986.2  611.44
  5002.4  610.90  5009.9  609.35  5011.9  608.85  5029.9  609.35  5039.9  617.96
  5049.9  618.89  5079.9  618.09  5109.9  615.36  5159.9  617.89  5349.9  615.64
  5389.9  616.99  5442.7  624.06  5489.9  632.11  5619.9  632.63  5699.9  636.47
#Mann=4,-1,0
  4596.8    0.05       0  5009.9   0.033       0  5029.9    0.05       0
  5442.7   0.075       0
Bank Sta=5009.9,5029.9
Exp/Cntr=0.3,0.1

Type RM Length L Ch R = 1,331,0,0,0
BEGIN DESCRIPTION:
Harriet Creek 1.0
END DESCRIPTION:
XS GIS Cut Line= 3
      2336873.62      7056043.83      2336686.13      7055111.59
      2335363.66      7055283.41
#Sta/Elev= 30
  3922.9  640.41  4023.1  637.83  4100.2  629.41  4181.8  623.13  4314.4  617.45
  4406.2  610.31  4436.8  612.97  4498.0  612.12  4589.8  614.49  4661.2  612.53
  4702.0  614.38  4799.5  612.99  4844.8  612.47  4898.2  605.79  4903.3  608.47
  4972.4  602.50  4974.4  602.00  4992.4  602.50  5032.3  612.61  5082.6  612.76
  5163.4  615.18  5203.7  612.78  5496.1  618.18  5684.0  624.69  5808.7  623.94
  5859.2  627.84  6098.0  630.78  6131.4  627.91  6171.8  628.06  6207.4  631.05
#Mann=7,-1,0
  3922.9    0.05       0  4799.5    0.12       0  4972.4    0.07       0
  4992.4    0.12       0  5082.6    0.05       0  5684.0   0.075       0
  6098.0    0.05       0
Bank Sta=4972.4,4992.4
Exp/Cntr=0.3,0.1

Chan Stop Cuts=-1