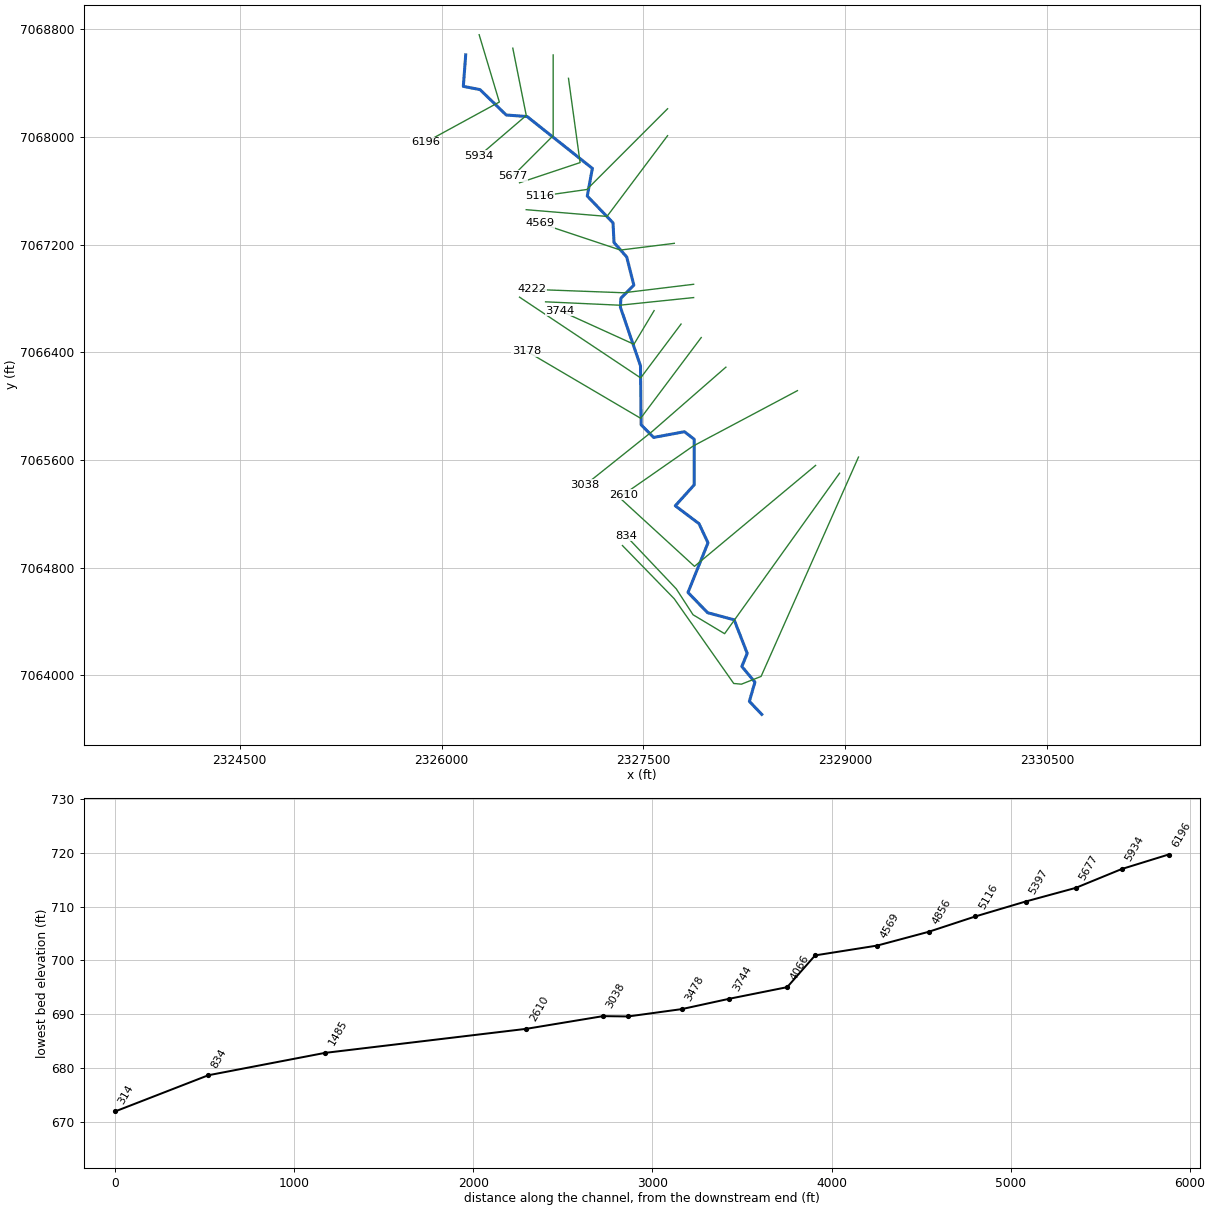
--- Harriet Creek Tributary 2.prj (project) ---

Proj Title=Harriet Creek Tributary 2 Base Level Engineering
Current Plan=p01
Default Exp/Contr=0.3,0.1
English Units
Geom File=g01
Flow File=f01
Plan File=p01
Y Axis Title=Elevation
X Axis Title(PF)=Main Channel Distance
X Axis Title(XS)=Station
BEGIN DESCRIPTION:
Harriet Creek Tributary 2
END DESCRIPTION:
DSS File=dss
DSS Export Rating Curves= 0
DSS Export Rating Curve Sorted= 0
DSS Export Volume Flow Curves= 0
DXF OffsetX= 0
DXF OffsetY= 0
DXF ScaleX= 1
DXF ScaleY= 10

--- Harriet Creek Tributary 2.p01 (plan) ---

Plan Title=Multiple Run
Program Version=4.10
Geom File=g01
Flow File=f01
Subcritical Flow
K Sum by GR= 0
Std Step Tol= 0.01
Critical Tol= 0.01
Num of Std Step Trials= 20
Max Error Tol= 0.3
Flow Tol Ratio= 0.001
Split Flow NTrial= 30
Split Flow Tol= 0.02
Split Flow Ratio= 0.02
Log Output Level= 0
Friction Slope Method= 0
Unsteady Friction Slope Method= 2
Unsteady Bridges Friction Slope Method= 1
Parabolic Critical Depth
Global Vel Dist= 1 , 1 , 1
Global Log Level= 0
CheckData=True
Encroach Param=-1 ,0,0, 0
BEGIN DESCRIPTION:
Multiple Run
END DESCRIPTION:
Computation Interval=1HOUR
Output Interval=1HOUR
Run HTab= 0
Run UNet= 0
Run PostProcess= 0
Run WQNet= 0
UNET Theta= 1
UNET Theta Warmup= 1
UNET ZTol= 0.02
UNET ZSATol= 0.05
UNET MxIter= 20
UNET MaxInSteps= 0
UNET DtIC= 0
UNET DtMin= 0
UNET MaxCRTS= 20
UNET WFStab= 2
UNET SFStab= 1
UNET WFX= 1
UNET SFX= 1
UNET DSS MLevel= 4
UNET DZMax Abort= 100
UNET Convert EG Bridges= 0
UNET Use Existing IB Tables=-1
UNET Froude Reduction=False
UNET Froude Limit= 1
UNET Froude Power= 10
UNET Time Slicing=0,0, 5
UNET Junction Losses=0
Instantaneous Interval=1HOUR
DSS File=dss
Write IC File= 0
Write IC File at Sim End=0
Echo Input=False
Echo Parameters=False
Echo Output=False
Write Detailed= 0
WQ AD Non Conservative
WQ ULTIMATE=-1
WQ Max Comp Step=1HOUR
WQ Output Interval=15MIN
WQ Output Selected Increments= 0
WQ Output face flow=0
WQ Output face velocity=0
WQ Output face area=0
WQ Output face dispersion=0
WQ Output cell volume=0
WQ Output cell surface area=0
WQ Output cell continuity=0
WQ Output cumulative cell continuity=0
WQ Output face conc=0
WQ Output face dconc_dx=0
WQ Output face courant=0
WQ Output face peclet=0
WQ Output face adv mass=0
WQ Output face disp mass=0
WQ Output cell mass=0
WQ Output cell source sink temp=0
WQ Output cell source sink nsm=0
WQ Output MaxMinRange=-1
WQ Daily Max Min Mean=-1
WQ Daily Range=0
WQ Daily Time=0
WQ Create Restart=0
WQ Fixed Restart=0
WQ System Summary=0
WQ Use Fixed Temperature=0
Sorting and Armoring Iterations= 10
XS Update Threshold= 0.02
Hydraulics Update Threshold= 0.02
Energy Slope Method= 1
Volume Change Method= 0
XS Weighting Method= 0
Number of US Weighted Cross Sections= 1
Number of DS Weighted Cross Sections= 1
Upstream XS Weight=0.25
Main XS Weight=0.5
Downstream XS Weight=0.25
Number of DS XS's Weighted with US Boundary= 1
Upstream Boundary Weight= 1
Weight of XSs Associated with US Boundary= 0
Number of US XS's Weighted with DS Boundary= 1
Downstream Boundary Weight= 0.5
Weight of XSs Associated with DS Boundary= 0.5
Sediment Output Level= 4
Mass or Volume Output= 0
Output Increment Type= 1
Profile and TS Output Increment= 10
XS Output Flag= 0
XS Output Increment= 10
Disregard all LS=0
Disregard all Conn=0
Disregard all Breaches=0
Disregard all Pumps=0

--- Harriet Creek Tributary 2.f01 (steady flow) ---

Flow Title=Multiple
Number of Profiles=7
Profile Names=10-year,25-year,50-year,1pct_min,100-year,1pct_plu,500-year
River Rch & RM= Harriet Creek Tr,Reach-1,6196
     150     187     216     124     247     493     324
River Rch & RM= Harriet Creek Tr,Reach-1,5116
     398     533     642     384     767    1530    1100
River Rch & RM= Harriet Creek Tr,Reach-1,2610
     457     617     746     449     895    1790    1290
Boundary for River Rch & Prof#=Harriet Creek Tr,Reach-1,1
Up Type=0
Dn Type=3
Dn Slope=0.005
Boundary for River Rch & Prof#=Harriet Creek Tr,Reach-1,2
Up Type=0
Dn Type=3
Dn Slope=0.005
Boundary for River Rch & Prof#=Harriet Creek Tr,Reach-1,3
Up Type=0
Dn Type=3
Dn Slope=0.005
Boundary for River Rch & Prof#=Harriet Creek Tr,Reach-1,4
Up Type=0
Dn Type=3
Dn Slope=0.005
Boundary for River Rch & Prof#=Harriet Creek Tr,Reach-1,5
Up Type=0
Dn Type=3
Dn Slope=0.005
Boundary for River Rch & Prof#=Harriet Creek Tr,Reach-1,6
Up Type=0
Dn Type=3
Dn Slope=0.005
Boundary for River Rch & Prof#=Harriet Creek Tr,Reach-1,7
Up Type=0
Dn Type=3
Dn Slope=0.005

--- Harriet Creek Tributary 2.g01 (geometry) ---

Geom Title=Existing Conditions

River Reach=Harriet Creek Tr,Reach-1
Reach XY= 30
      2326179.00      7068610.00      2326161.36      7068376.44
      2326285.43      7068352.21      2326480.27      7068163.49
      2326635.19      7068152.18      2327120.15      7067767.02
      2327082.38      7067561.40      2327273.53      7067362.45
      2327281.08      7067215.86      2327375.44      7067108.53
      2327428.30      7066899.25      2327332.00      7066801.65
      2327328.51      7066735.19      2327477.78      7066299.50
      2327482.54      7065861.44      2327575.57      7065767.79
      2327804.22      7065810.34      2327877.03      7065754.35
      2327877.00      7065415.68      2327736.27      7065259.93
      2327912.52      7065127.05      2327979.33      7064984.97
      2327830.62      7064616.03      2327976.55      7064465.47
      2328173.60      7064412.71      2328270.93      7064163.31
      2328230.67      7064066.05      2328328.05      7063949.51
      2328286.68      7063806.58      2328379.00      7063710.00

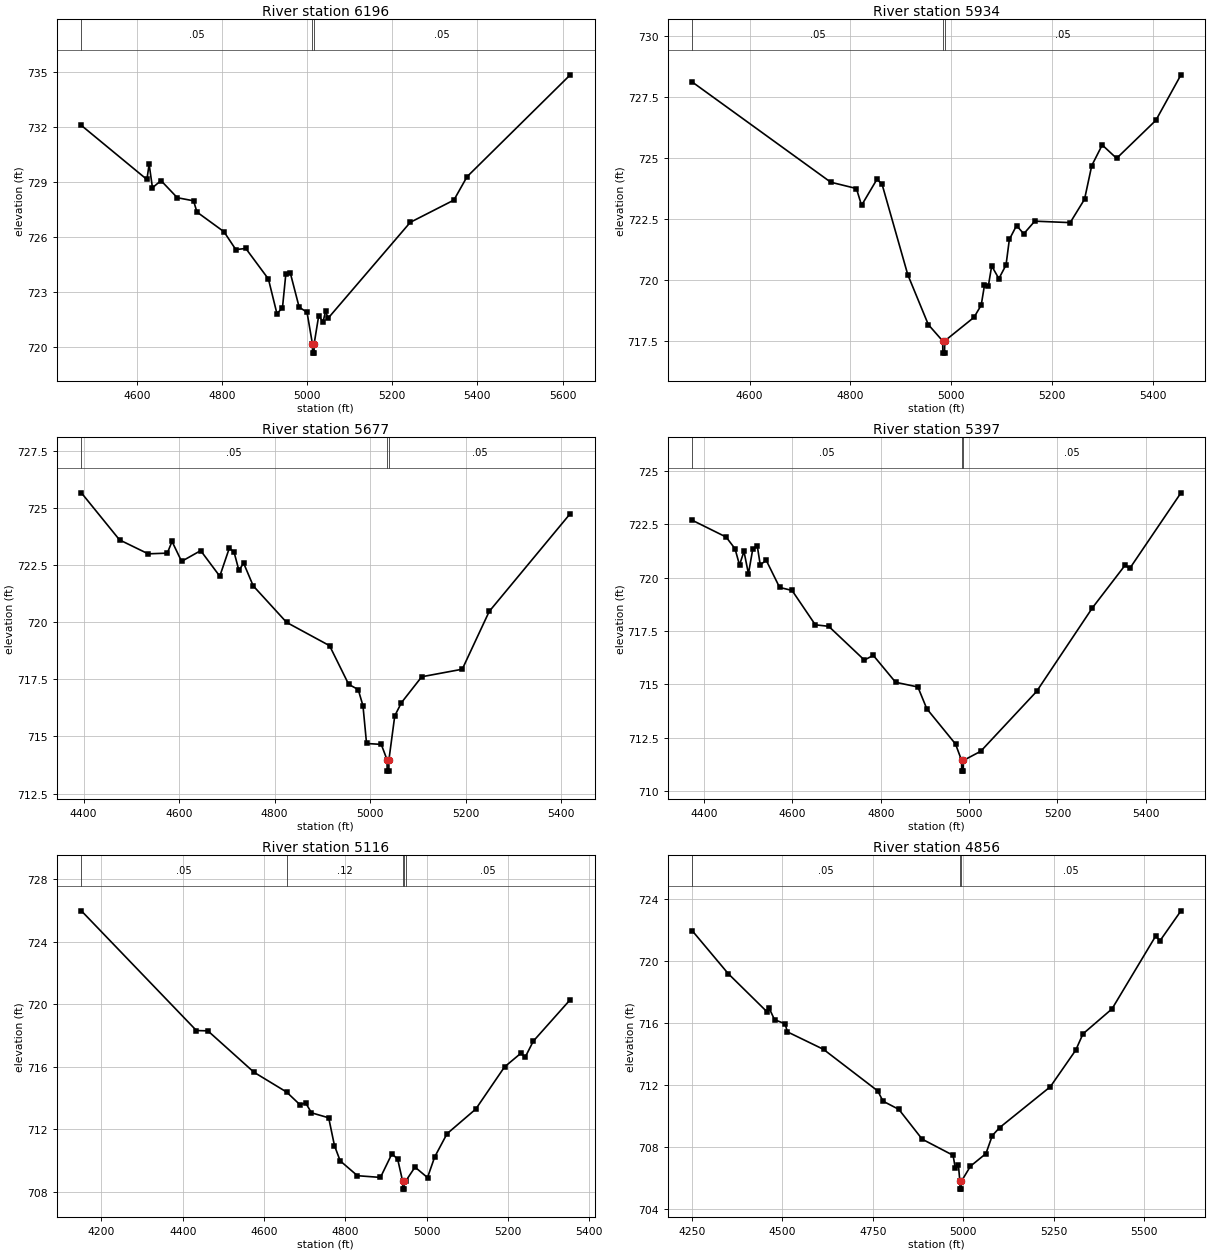
Type RM Length L Ch R = 1,6196,262,262,262
BEGIN DESCRIPTION:
Harriet Creek Tributary 2 15.0
END DESCRIPTION:
XS GIS Cut Line= 3
      2326279.00      7068760.00      2326429.00      7068260.00
      2325879.01      7067960.01
#Sta/Elev= 30
  4469.6  732.07  4623.6  729.13  4628.8  729.96  4636.6  728.68  4656.7  729.07
  4694.9  728.14  4733.2  727.97  4741.1  727.36  4804.6  726.29  4832.4  725.32
  4855.9  725.38  4909.0  723.72  4929.0  721.84  4942.0  722.15  4949.9  723.99
  4960.3  724.06  4981.2  722.19  4999.7  721.91  5012.4  720.19  5012.7  719.69
  5016.2  719.69  5016.4  720.19  5027.2  721.73  5037.2  721.38  5043.4  721.98
  5049.0  721.58  5242.2  726.80  5344.7  728.01  5375.6  729.28  5618.1  734.82
#Mann=3,-1,0
  4469.6    0.05       0  5012.4   0.033       0  5016.4    0.05       0
Bank Sta=5012.4,5016.4
Exp/Cntr=0.3,0.1

Type RM Length L Ch R = 1,5934,257,257,257
BEGIN DESCRIPTION:
Harriet Creek Tributary 2 14.0
END DESCRIPTION:
XS GIS Cut Line= 3
      2326528.99      7068660.04      2326629.00      7068160.00
      2326279.02      7067860.01
#Sta/Elev= 30
  4485.6  728.13  4761.0  724.01  4812.0  723.75  4822.2  723.06  4852.8  724.13
  4863.0  723.92  4914.0  720.21  4954.8  718.16  4983.3  717.49  4983.6  716.99
  4987.1  716.99  4987.3  717.49  5045.5  718.46  5059.8  718.96  5066.3  719.78
  5074.0  719.75  5080.6  720.57  5094.9  720.05  5109.1  720.61  5115.7  721.66
  5130.0  722.23  5144.3  721.89  5166.2  722.41  5236.5  722.35  5265.0  723.31
  5279.3  724.69  5300.1  725.54  5328.7  724.99  5406.6  726.55  5456.5  728.42
#Mann=3,-1,0
  4485.6    0.05       0  4983.3   0.033       0  4987.3    0.05       0
Bank Sta=4983.3,4987.3
Exp/Cntr=0.3,0.1

Type RM Length L Ch R = 1,5677,280,280,280
BEGIN DESCRIPTION:
Harriet Creek Tributary 2 13.0
END DESCRIPTION:
XS GIS Cut Line= 3
      2326829.00      7068609.99      2326829.00      7068010.00
      2326528.97      7067709.97
#Sta/Elev= 30
  4395.2  725.66  4475.2  723.60  4535.2  722.99  4575.2  723.02  4585.2  723.53
  4605.2  722.66  4645.2  723.13  4685.2  722.01  4705.2  723.24  4715.2  723.06
  4725.2  722.27  4735.2  722.58  4755.2  721.59  4825.2  719.99  4915.2  718.97
  4955.2  717.28  4975.2  717.05  4985.2  716.34  4992.7  714.69  5023.5  714.65
  5035.6  713.98  5035.9  713.48  5039.4  713.48  5039.6  713.98  5051.8  715.90
  5065.9  716.48  5108.3  717.61  5193.2  717.94  5249.7  720.47  5419.5  724.75
#Mann=3,-1,0
  4395.2    0.05       0  5035.6   0.033       0  5039.6    0.05       0
Bank Sta=5035.6,5039.6
Exp/Cntr=0.3,0.1

Type RM Length L Ch R = 1,5397,281,281,281
BEGIN DESCRIPTION:
Harriet Creek Tributary 2 12.0
END DESCRIPTION:
XS GIS Cut Line= 3
      2326942.75      7068436.36      2327029.00      7067810.00
      2326579.01      7067660.00
#Sta/Elev= 30
  4372.9  722.69  4450.0  721.90  4470.2  721.35  4480.3  720.59  4490.4  721.23
  4500.5  720.18  4510.5  721.36  4520.6  721.47  4527.2  720.60  4540.8  720.81
  4571.1  719.54  4599.2  719.40  4651.9  717.79  4682.2  717.72  4762.9  716.14
  4783.1  716.36  4833.6  715.10  4884.0  714.88  4904.2  713.86  4969.2  712.21
  4983.0  711.44  4983.2  710.94  4986.7  710.94  4987.0  711.44  5026.3  711.87
  5152.7  714.67  5279.2  718.59  5353.0  720.58  5363.6  720.43  5479.5  723.97
#Mann=3,-1,0
  4372.9    0.05       0  4983.0   0.033       0  4987.0    0.05       0
Bank Sta=4983,4987
Exp/Cntr=0.3,0.1

Type RM Length L Ch R = 1,5116,260,260,260
BEGIN DESCRIPTION:
Harriet Creek Tributary 2 11.0
END DESCRIPTION:
XS GIS Cut Line= 3
      2327679.01      7068210.01      2327079.00      7067610.00
      2326729.00      7067560.00
#Sta/Elev= 30
  4150.8  725.99  4433.7  718.32  4461.9  718.30  4575.1  715.65  4655.4  714.38
  4688.2  713.57  4702.4  713.68  4716.5  713.05  4758.9  712.73  4773.1  710.95
  4787.2  709.97  4829.6  709.02  4886.2  708.91  4914.5  710.43  4928.6  710.07
  4940.8  708.66  4941.0  708.16  4944.5  708.16  4944.8  708.66  4948.7  708.69
  4971.1  709.57  5001.9  708.90  5019.5  710.22  5049.9  711.71  5120.6  713.29
  5191.3  715.99  5231.7  716.87  5241.8  716.60  5262.0  717.64  5352.9  720.30
#Mann=5,-1,0
  4150.8    0.05       0  4655.4    0.12       0  4940.8   0.033       0
  4944.8    0.12       0  4948.7    0.05       0
Bank Sta=4940.8,4944.8
Exp/Cntr=0.3,0.1

Type RM Length L Ch R = 1,4856,287,287,287
BEGIN DESCRIPTION:
Harriet Creek Tributary 2 10.0
END DESCRIPTION:
XS GIS Cut Line= 3
      2327678.99      7068009.98      2327229.00      7067410.00
      2326628.96      7067460.00
#Sta/Elev= 30
  4250.3  721.98  4350.3  719.20  4457.6  716.74  4463.8  716.96  4478.4  716.23
  4507.6  715.97  4513.8  715.45  4613.8  714.32  4763.8  711.64  4778.4  710.98
  4822.2  710.45  4886.7  708.53  4972.2  707.49  4978.4  706.64  4986.7  706.89
  4991.0  705.81  4991.2  705.31  4994.7  705.31  4995.0  705.81  5020.3  706.79
  5063.0  707.60  5080.6  708.76  5100.6  709.27  5241.1  711.91  5311.4  714.27
  5331.4  715.32  5411.7  716.93  5532.1  721.61  5544.7  721.33  5602.4  723.25
#Mann=3,-1,0
  4250.3    0.05       0  4991.0    0.04       0  4995.0    0.05       0
Bank Sta=4991,4995
Exp/Cntr=0.3,0.1

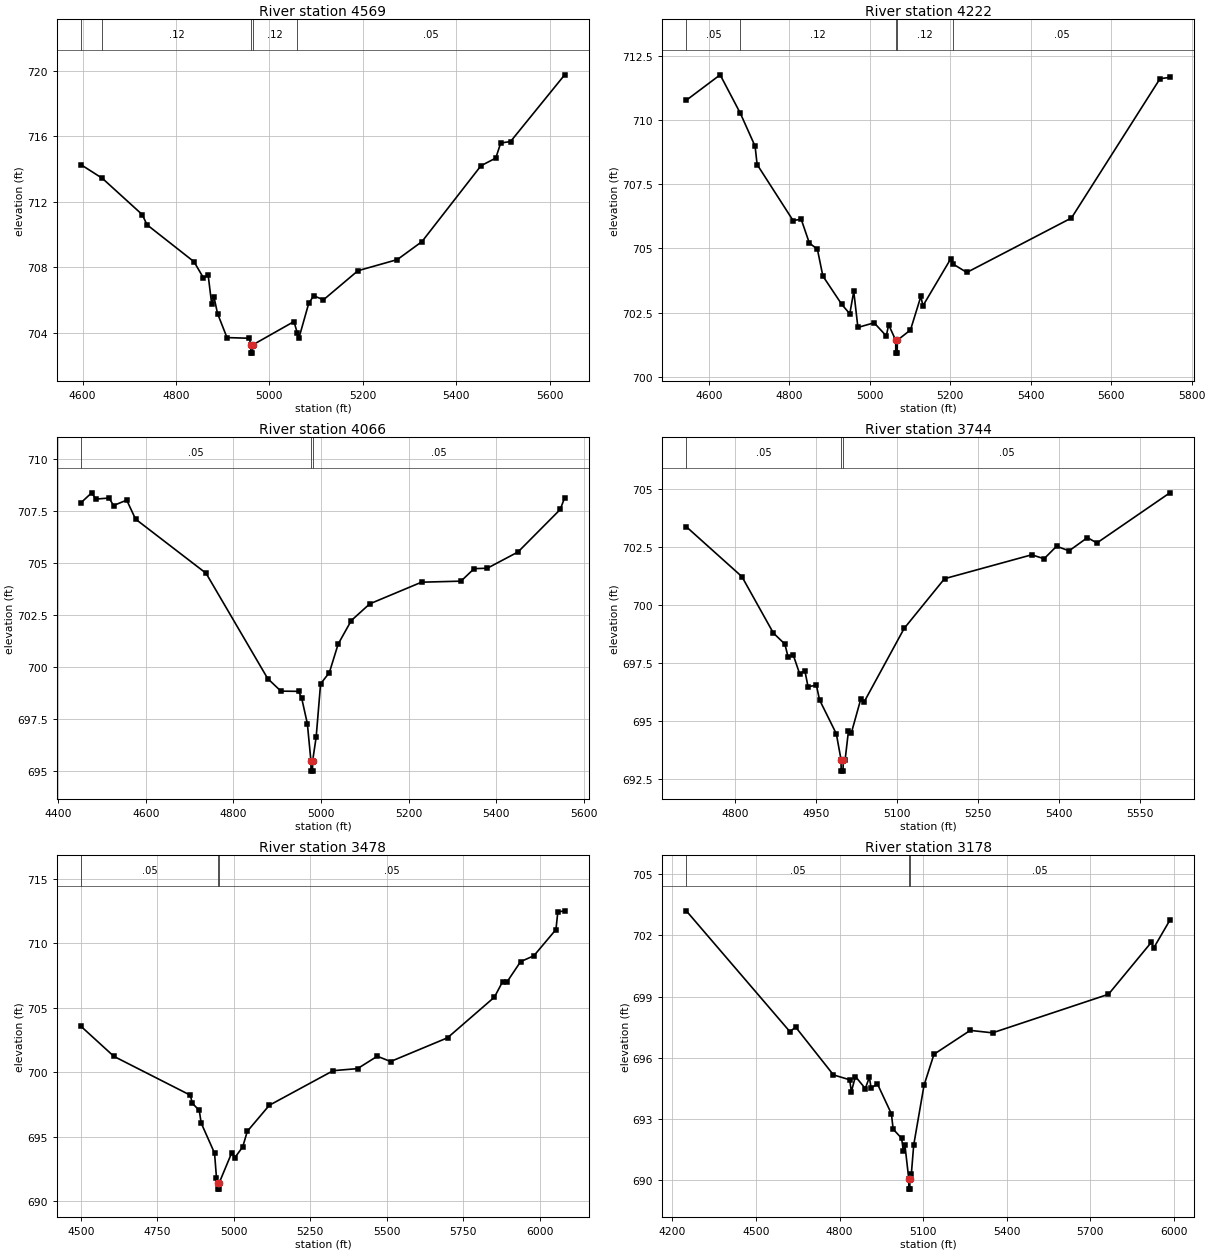
Type RM Length L Ch R = 1,4569,347,347,347
BEGIN DESCRIPTION:
Harriet Creek Tributary 2 9.0
END DESCRIPTION:
XS GIS Cut Line= 3
      2327728.97      7067210.00      2327329.00      7067160.00
      2326729.04      7067359.99
#Sta/Elev= 30
  4596.9  714.27  4642.4  713.44  4727.9  711.22  4738.0  710.60  4838.7  708.34
  4858.9  707.35  4869.0  707.52  4876.5  705.76  4881.6  706.16  4889.1  705.17
  4909.3  703.70  4957.2  703.66  4960.2  703.25  4960.4  702.75  4963.9  702.75
  4964.2  703.25  5052.7  704.68  5059.9  703.98  5063.2  703.66  5084.3  705.79
  5094.9  706.26  5115.9  706.01  5189.7  707.79  5274.0  708.47  5326.8  709.57
  5453.2  714.21  5484.9  714.68  5495.4  715.60  5516.5  715.69  5632.4  719.77
#Mann=5,-1,0
  4596.9    0.05       0  4642.4    0.12       0  4960.2    0.07       0
  4964.2    0.12       0  5059.9    0.05       0
Bank Sta=4960.2,4964.2
Exp/Cntr=0.3,0.1

Type RM Length L Ch R = 1,4222,156,156,156
BEGIN DESCRIPTION:
Harriet Creek Tributary 2 8.0
END DESCRIPTION:
XS GIS Cut Line= 3
      2327872.58      7066905.78      2327353.47      7066842.73
      2326674.56      7066867.95
#Sta/Elev= 30
  4543.5  710.76  4627.7  711.75  4678.0  710.25  4714.6  708.97  4719.6  708.26
  4809.0  706.08  4829.2  706.13  4849.3  705.21  4869.5  704.96  4883.1  703.92
  4929.9  702.82  4950.0  702.45  4959.9  703.32  4970.2  701.92  5010.5  702.10
  5040.7  701.59  5046.7  702.02  5064.2  701.42  5064.4  700.92  5067.9  700.92
  5068.2  701.42  5100.9  701.82  5126.8  703.13  5131.8  702.76  5201.0  704.59
  5206.4  704.39  5241.0  704.06  5501.2  706.18  5721.3  711.60  5745.8  711.65
#Mann=5,-1,0
  4543.5    0.05       0  4678.0    0.12       0  5064.2    0.07       0
  5068.2    0.12       0  5206.4    0.05       0
Bank Sta=5064.2,5068.2
Exp/Cntr=0.3,0.1

Type RM Length L Ch R = 1,4066,322,322,322
BEGIN DESCRIPTION:
Harriet Creek Tributary 2 7.0
END DESCRIPTION:
XS GIS Cut Line= 3
      2327872.59      7066806.99      2327324.04      7066750.25
      2326772.59      7066775.41
#Sta/Elev= 30
  4452.6  707.90  4476.7  708.37  4486.4  708.07  4516.5  708.12  4526.6  707.76
  4556.7  708.02  4576.8  707.11  4737.7  704.51  4878.5  699.45  4908.6  698.85
  4948.8  698.84  4955.9  698.52  4968.9  697.29  4977.0  695.51  4977.2  695.01
  4980.7  695.01  4981.0  695.51  4989.0  696.64  4999.1  699.20  5019.1  699.74
  5039.2  701.11  5069.2  702.24  5111.3  703.04  5229.4  704.08  5319.4  704.13
  5349.5  704.73  5379.5  704.75  5449.6  705.53  5545.9  707.57  5556.1  708.14
#Mann=3,-1,0
  4452.6    0.05       0  4977.0   0.033       0  4981.0    0.05       0
Bank Sta=4977,4981
Exp/Cntr=0.3,0.1

Type RM Length L Ch R = 1,3744,266,266,266
BEGIN DESCRIPTION:
Harriet Creek Tributary 2 6.0
END DESCRIPTION:
XS GIS Cut Line= 3
      2327579.00      7066710.00      2327429.00      7066460.00
      2326879.00      7066710.00
#Sta/Elev= 30
  4709.1  703.39  4812.1  701.24  4870.4  698.81  4891.8  698.33  4897.6  697.78
  4907.4  697.85  4919.0  697.06  4928.7  697.19  4934.6  696.50  4950.1  696.56
  4955.9  695.93  4987.0  694.47  4995.7  693.36  4996.0  692.86  4999.5  692.86
  4999.7  693.36  5003.4  693.36  5009.4  694.58  5014.9  694.51  5032.5  695.98
  5038.0  695.82  5112.7  699.01  5187.4  701.15  5348.9  702.18  5371.9  702.01
  5395.0  702.55  5418.1  702.35  5452.1  702.92  5469.7  702.69  5604.8  704.85
#Mann=3,-1,0
  4709.1    0.05       0  4995.7   0.033       0  4999.7    0.05       0
Bank Sta=4995.7,4999.7
Exp/Cntr=0.3,0.1

Type RM Length L Ch R = 1,3478,300,300,300
BEGIN DESCRIPTION:
Harriet Creek Tributary 2 5.0
END DESCRIPTION:
XS GIS Cut Line= 3
      2327779.03      7066610.04      2327479.00      7066210.00
      2326579.01      7066809.99
#Sta/Elev= 30
  4500.1  703.54  4607.4  701.22  4857.4  698.21  4863.7  697.59  4886.6  697.03
  4892.9  696.05  4936.6  693.72  4942.9  691.81  4948.1  691.43  4948.4  690.93
  4951.9  690.93  4952.1  691.43  4992.9  693.75  5003.2  693.38  5028.7  694.20
  5043.7  695.41  5115.8  697.43  5324.6  700.11  5404.3  700.27  5468.9  701.23
  5512.4  700.82  5698.7  702.66  5852.0  705.81  5879.0  707.02  5894.0  707.02
  5937.6  708.56  5981.2  709.02  6053.3  711.05  6059.3  712.41  6081.8  712.50
#Mann=3,-1,0
  4500.1    0.05       0  4948.1   0.033       0  4952.1    0.05       0
Bank Sta=4948.1,4952.1
Exp/Cntr=0.3,0.1

Type RM Length L Ch R = 1,3178,140,140,140
BEGIN DESCRIPTION:
Harriet Creek Tributary 2 4.0
END DESCRIPTION:
XS GIS Cut Line= 3
      2327929.02      7066510.03      2327479.00      7065910.00
      2326628.99      7066410.00
#Sta/Elev= 30
  4249.5  703.20  4621.4  697.28  4642.2  697.50  4777.7  695.16  4836.0  694.92
  4842.2  694.34  4856.8  695.08  4892.2  694.49  4906.8  695.04  4913.1  694.52
  4936.0  694.71  4986.0  693.25  4992.2  692.50  5022.7  692.05  5028.8  691.42
  5034.6  691.70  5048.3  690.06  5048.5  689.56  5052.0  689.56  5052.3  690.06
  5057.5  690.29  5066.0  691.72  5103.1  694.65  5138.8  696.17  5269.0  697.34
  5349.0  697.22  5765.3  699.11  5919.3  701.66  5927.7  701.38  5985.7  702.74
#Mann=3,-1,0
  4249.5    0.05       0  5048.3   0.033       0  5052.3    0.05       0
Bank Sta=5048.3,5052.3
Exp/Cntr=0.3,0.1

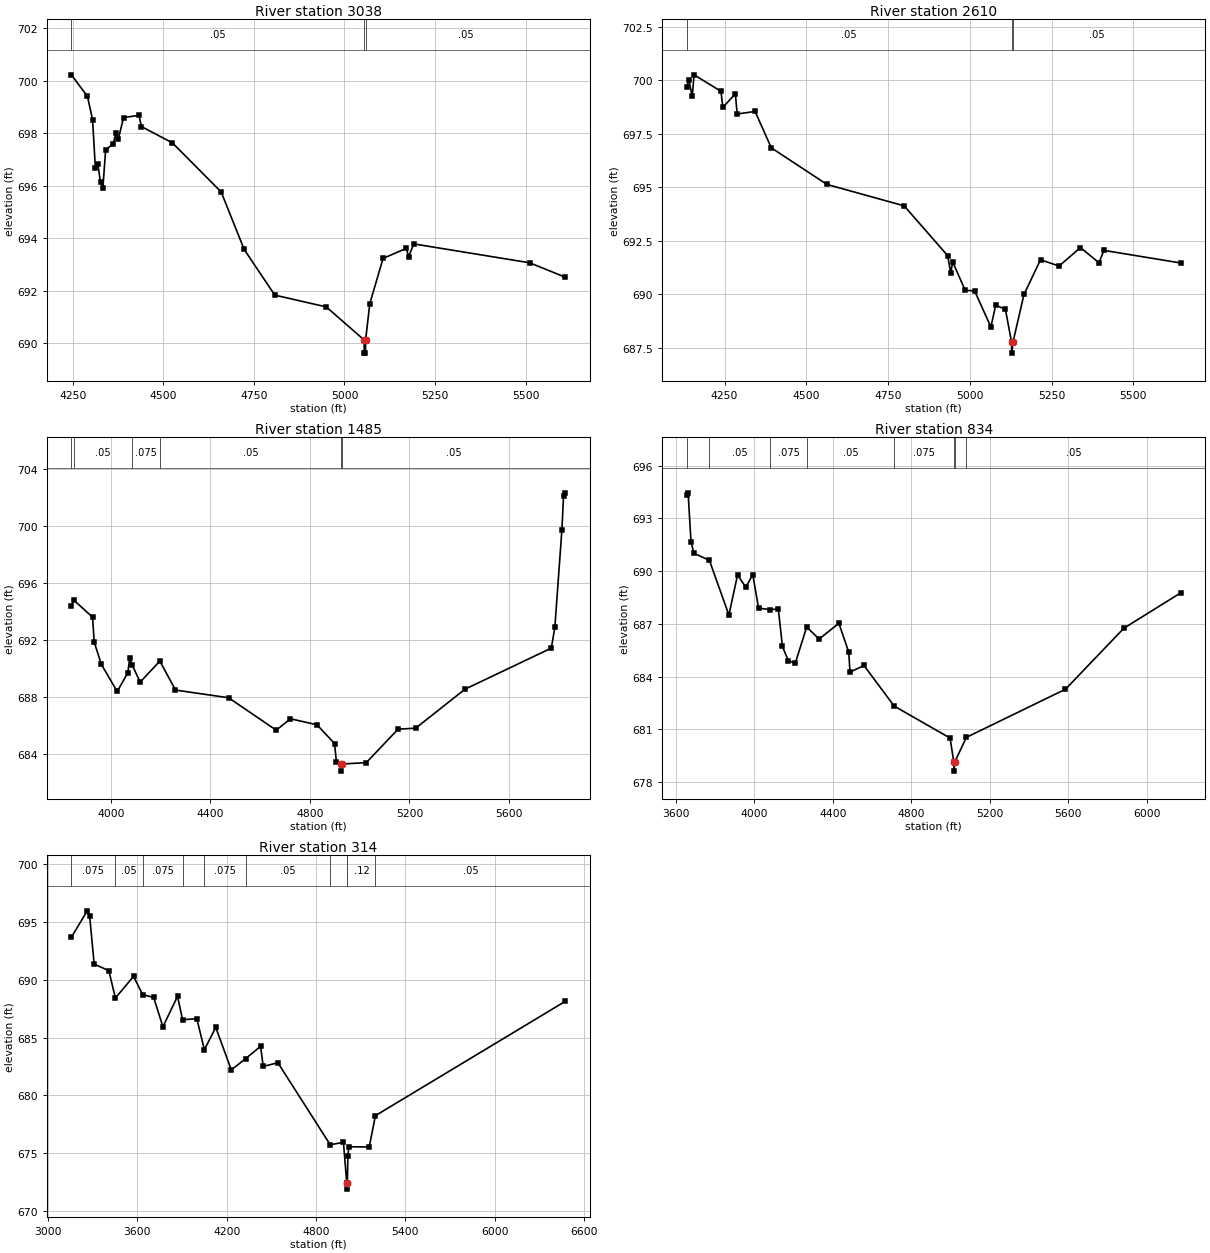
Type RM Length L Ch R = 1,3038,428,428,428
BEGIN DESCRIPTION:
Harriet Creek Tributary 2 3.0
END DESCRIPTION:
XS GIS Cut Line= 3
      2328112.27      7066289.98      2327567.86      7065814.93
      2327066.44      7065414.22
#Sta/Elev= 30
  4245.6  700.22  4290.0  699.40  4304.2  698.51  4311.8  696.69  4318.5  696.84
  4326.1  696.12  4332.7  695.92  4340.3  697.37  4361.2  697.58  4368.8  698.01
  4375.4  697.78  4389.7  698.59  4432.4  698.68  4439.0  698.25  4524.5  697.63
  4659.3  695.76  4722.9  693.57  4807.4  691.83  4949.8  691.38  5054.3  690.12
  5054.5  689.62  5058.0  689.62  5058.3  690.12  5069.8  691.50  5106.6  693.23
  5170.7  693.61  5177.1  693.30  5191.5  693.78  5511.7  693.06  5610.0  692.51
#Mann=3,-1,0
  4245.6    0.05       0  5054.3   0.033       0  5058.3    0.05       0
Bank Sta=5054.3,5058.3
Exp/Cntr=0.3,0.1

Type RM Length L Ch R = 1,2610,1125,1125,1125
BEGIN DESCRIPTION:
Harriet Creek Tributary 2 2.0
END DESCRIPTION:
XS GIS Cut Line= 3
      2328643.95      7066115.47      2327868.42      7065703.54
      2327349.24      7065342.00
#Sta/Elev= 30
  4134.3  699.68  4140.4  700.04  4151.1  699.25  4156.8  700.26  4239.0  699.49
  4244.7  698.74  4283.0  699.37  4288.6  698.43  4343.3  698.55  4392.9  696.85
  4563.1  695.14  4799.2  694.14  4932.5  691.81  4941.8  690.99  4947.4  691.53
  4985.7  690.20  5015.1  690.16  5064.5  688.48  5079.3  689.50  5109.0  689.30
  5127.9  687.76  5128.2  687.26  5131.9  687.76  5165.7  690.00  5216.3  691.62
  5273.1  691.33  5338.5  692.19  5395.2  691.48  5410.1  692.06  5645.1  691.47
#Mann=3,-1,0
  4134.3    0.05       0  5127.9   0.033       0  5131.9    0.05       0
Bank Sta=5127.9,5131.9
Exp/Cntr=0.3,0.1

Type RM Length L Ch R = 1,1485,651,651,651
BEGIN DESCRIPTION:
Harriet Creek Tributary 2 1.0
END DESCRIPTION:
XS GIS Cut Line= 3
      2328778.97      7065559.97      2327879.00      7064810.00
      2327279.03      7065359.97
#Sta/Elev= 30
  3841.2  694.39  3850.4  694.81  3926.4  693.61  3932.9  691.86  3961.6  690.29
  4025.4  688.38  4068.3  689.70  4075.5  690.72  4085.6  690.24  4117.8  689.04
  4196.9  690.52  4259.7  688.48  4473.1  687.94  4664.5  685.66  4721.8  686.46
  4828.5  686.04  4898.8  684.72  4906.6  683.41  4925.4  683.28  4925.7  682.78
  4929.4  683.28  5026.6  683.38  5154.2  685.73  5225.1  685.80  5423.1  688.54
  5770.2  691.43  5784.4  692.89  5812.8  699.76  5819.5  702.16  5826.6  702.35
#Mann=6,-1,0
  3841.2   0.075       0  3850.4    0.05       0  4085.6   0.075       0
  4196.9    0.05       0  4925.4   0.033       0  4929.4    0.05       0
Bank Sta=4925.4,4929.4
Exp/Cntr=0.3,0.1

Type RM Length L Ch R = 1,834,520,520,520
BEGIN DESCRIPTION:
Harriet Creek Tributary 2 0.9
END DESCRIPTION:
XS GIS Cut Line= 5
      2328956.97      7065502.22      2328102.80      7064309.51
      2327868.42      7064450.13      2327743.42      7064642.84
      2327368.44      7065038.66
#Sta/Elev= 30
  3656.7  694.34  3663.7  694.45  3678.4  691.67  3693.2  691.01  3772.1  690.61
  3871.3  687.50  3915.5  689.78  3957.3  689.08  3992.9  689.80  4022.4  687.89
  4081.8  687.81  4123.1  687.84  4144.0  685.71  4173.5  684.91  4209.1  684.75
  4267.6  686.82  4330.7  686.13  4431.4  687.03  4481.8  685.38  4487.9  684.25
  4559.2  684.63  4713.0  682.32  4997.7  680.50  5016.6  679.12  5016.8  678.62
  5020.6  679.12  5080.5  680.54  5585.3  683.28  5882.7  686.75  6172.0  688.76
#Mann=8,-1,0
  3656.7   0.075       0  3772.1    0.05       0  4081.8   0.075       0
  4267.6    0.05       0  4713.0   0.075       0  5016.6    0.07       0
  5020.6   0.075       0  5080.5    0.05       0
Bank Sta=5016.6,5020.6
Exp/Cntr=0.3,0.1

Type RM Length L Ch R = 1,314,0,0,0
BEGIN DESCRIPTION:
Harriet Creek Tributary 2 0.5
END DESCRIPTION:
XS GIS Cut Line= 6
      2329097.60      7065622.03      2328373.63      7063991.80
      2328227.80      7063934.51      2328170.51      7063939.71
      2327727.80      7064569.92      2327343.57      7064964.53
#Sta/Elev= 30
  3156.8  693.69  3263.6  695.98  3279.4  695.56  3310.1  691.37  3408.6  690.80
  3452.6  688.43  3574.8  690.31  3635.7  688.72  3709.6  688.49  3771.8  685.94
  3870.2  688.58  3903.9  686.55  3999.7  686.65  4050.4  683.96  4127.0  685.89
  4231.3  682.21  4326.9  683.18  4428.3  684.25  4445.8  682.51  4544.3  682.83
  4896.0  675.73  4984.8  675.94  5007.2  672.39  5007.5  671.89  5011.2  672.39
  5014.6  674.77  5020.7  675.56  5158.0  675.54  5199.6  678.25  6475.7  688.15
#Mann=10,-1,0
  3156.8   0.075       0  3452.6    0.05       0  3635.7   0.075       0
  3903.9     0.1       0  4050.4   0.075       0  4326.9    0.05       0
  4896.0    0.12       0  5007.2    0.07       0  5011.2    0.12       0
  5199.6    0.05       0
Bank Sta=5007.2,5011.2
Exp/Cntr=0.3,0.1

Chan Stop Cuts=-1