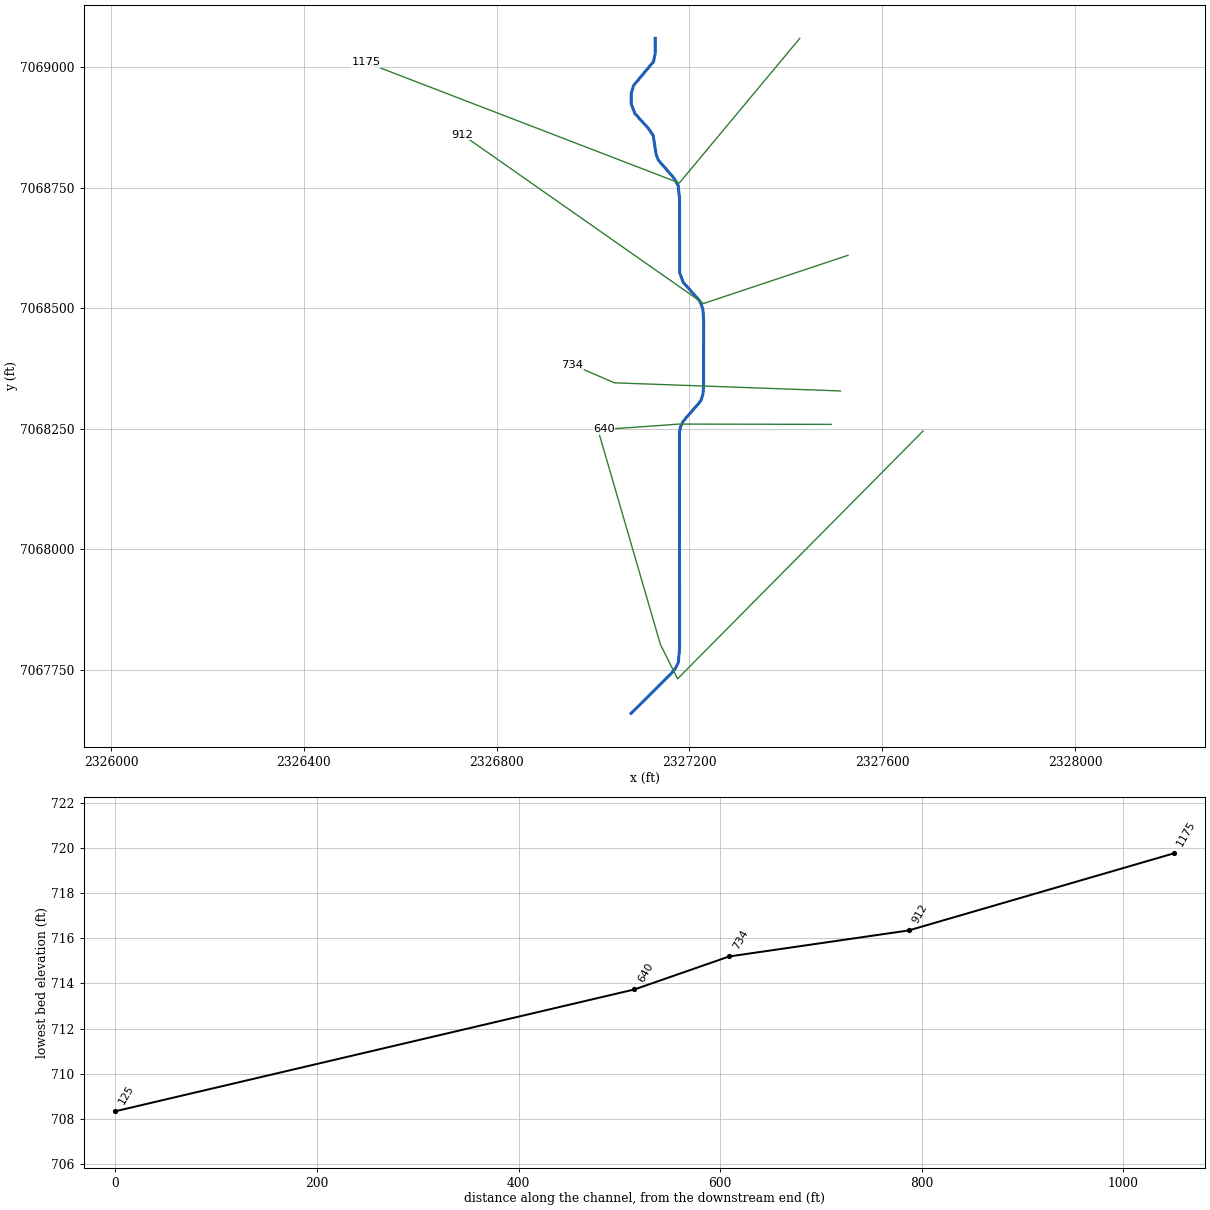
--- Harriet Creek Tributary 2_1.prj (project) ---

Proj Title=Harriet Creek Tributary 2_1 Base Level Engineering
Current Plan=p01
Default Exp/Contr=0.3,0.1
English Units
Geom File=g01
Flow File=f01
Plan File=p01
BEGIN DESCRIPTION:
Harriet Creek Tributary 2_1
END DESCRIPTION:

--- Harriet Creek Tributary 2_1.p01 (plan) ---

Plan Title=Multiple Run
Short Identifier=Multiple
Geom File=g01
Flow File=f01
Subcritical Flow
K Sum by GR= 0
Std Step Tol= 0.01
Critical Tol= 0.01
Num of Std Step Trials= 20
Max Error Tol= 0.3
Flow Tol Ratio= 0.001
Split Flow NTrial= 30
Split Flow Tol= 0.02
Split Flow Ratio= 0.02
Log Output Level= 0
Friction Slope Method= 1
Unsteady Friction Slope Method= 2
Unsteady Bridges Friction Slope Method= 1
Parabolic Critical Depth
Global Vel Dist=  1 , 1 , 1
Global Log Level= 0
CheckData=True
Encroach Param= -1, 0, 0, 0
BEGIN DESCRIPTION:
Multiple Run
END DESCRIPTION:

--- Harriet Creek Tributary 2_1.f01 (steady flow) ---

Flow Title=Multiple
Number of Profiles=7
Profile Names=10-year,25-year,50-year,1pct_min,100-year,1pct_plu,500-year
River Rch & RM= Harriet Creek Tr,Reach-1,1175
     185     235     273     158     316     630     421
Boundary for River Rch & Prof#=Harriet Creek Tr,Reach-1,1
Up Type=0
Dn Type=3
Dn Slope=0.005
Boundary for River Rch & Prof#=Harriet Creek Tr,Reach-1,2
Up Type=0
Dn Type=3
Dn Slope=0.005
Boundary for River Rch & Prof#=Harriet Creek Tr,Reach-1,3
Up Type=0
Dn Type=3
Dn Slope=0.005
Boundary for River Rch & Prof#=Harriet Creek Tr,Reach-1,4
Up Type=0
Dn Type=3
Dn Slope=0.005
Boundary for River Rch & Prof#=Harriet Creek Tr,Reach-1,5
Up Type=0
Dn Type=3
Dn Slope=0.005
Boundary for River Rch & Prof#=Harriet Creek Tr,Reach-1,6
Up Type=0
Dn Type=3
Dn Slope=0.005
Boundary for River Rch & Prof#=Harriet Creek Tr,Reach-1,7
Up Type=0
Dn Type=3
Dn Slope=0.005

--- Harriet Creek Tributary 2_1.g01 (geometry) ---

Geom Title=Existing Conditions

River Reach=Harriet Creek Tr,Reach-1
Reach XY= 30
      2327129.00      7069060.00      2327128.86      7069028.19
      2327125.31      7069011.49      2327084.12      7068962.25
      2327079.12      7068945.91      2327079.19      7068924.09
      2327086.76      7068904.06      2327114.89      7068873.07
      2327124.78      7068858.28      2327130.83      7068819.85
      2327135.11      7068807.82      2327168.20      7068769.67
      2327176.65      7068754.48      2327179.39      7068728.35
      2327179.69      7068573.92      2327187.14      7068553.94
      2327220.86      7068516.06      2327227.78      7068499.49
      2327229.43      7068475.18      2327229.20      7068334.92
      2327227.78      7068320.51      2327223.25      7068307.67
      2327187.14      7068266.06      2327181.38      7068254.47
      2327179.21      7068241.73      2327179.49      7067794.80
      2327176.98      7067765.84      2327171.27      7067753.78
      2327162.67      7067743.19      2327079.00      7067660.00

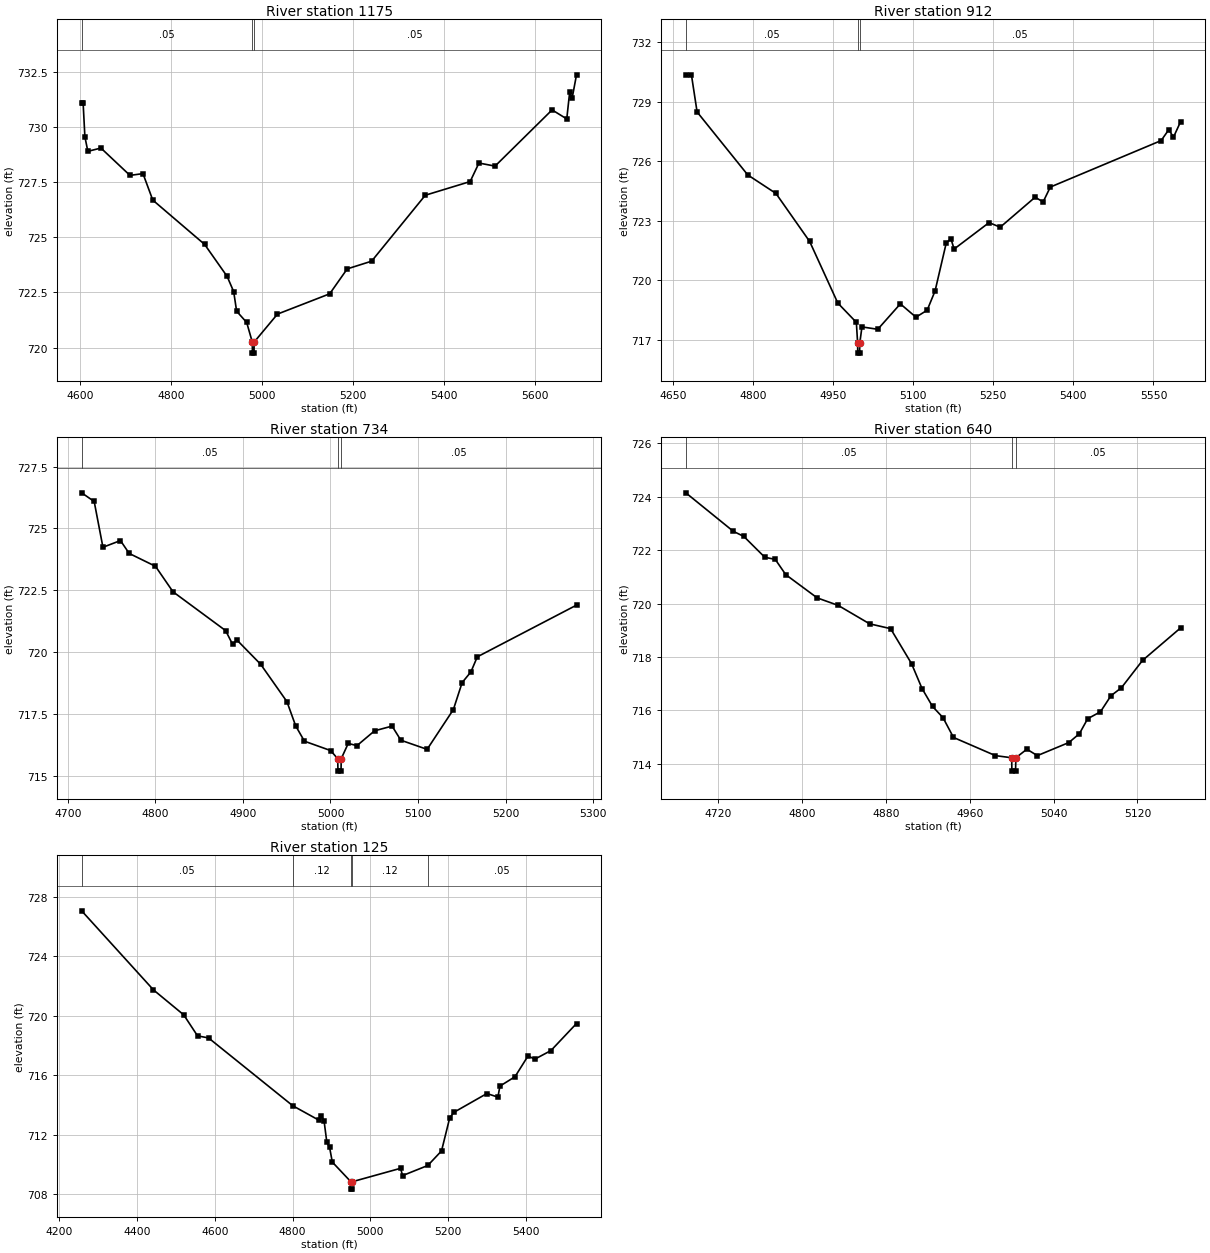
Type RM Length L Ch R = 1,1175,263,263,263
BEGIN DESCRIPTION:
Harriet Creek Tributary 2_1 3.0
END DESCRIPTION:
XS GIS Cut Line= 3
      2327428.98      7069059.98      2327179.00      7068760.00
      2326529.00      7069010.00
#Sta/Elev= 30
  4603.5  731.10  4606.7  731.10  4610.6  729.56  4617.1  728.90  4645.8  729.05
  4709.6  727.81  4738.2  727.89  4759.7  726.69  4873.6  724.68  4923.0  723.23
  4937.4  722.54  4943.9  721.65  4966.0  721.14  4978.3  720.25  4978.6  719.75
  4982.1  719.75  4982.3  720.25  5033.6  721.52  5148.3  722.44  5186.8  723.57
  5240.4  723.92  5358.3  726.91  5456.8  727.53  5476.1  728.37  5511.5  728.23
  5636.8  730.78  5669.0  730.37  5675.4  731.59  5680.8  731.31  5690.4  732.37
#Mann=3,-1,0
  4603.5    0.05       0  4978.3   0.033       0  4982.3    0.05       0
Bank Sta=4978.3,4982.3
Exp/Cntr=0.3,0.1

Type RM Length L Ch R = 1,912,178,178,178
BEGIN DESCRIPTION:
Harriet Creek Tributary 2_1 2.0
END DESCRIPTION:
XS GIS Cut Line= 3
      2327529.04      7068610.01      2327229.00      7068510.00
      2326729.00      7068860.00
#Sta/Elev= 30
  4674.3  730.35  4684.9  730.33  4695.4  728.48  4790.3  725.31  4843.0  724.38
  4906.2  721.96  4958.9  718.86  4993.6  717.89  4996.0  716.84  4996.2  716.34
  4999.7  716.34  5000.0  716.84  5004.1  717.66  5033.7  717.54  5076.0  718.82
  5105.2  718.15  5126.2  718.50  5141.0  719.47  5161.9  721.88  5170.6  722.10
  5176.7  721.58  5242.1  722.91  5263.0  722.68  5328.4  724.19  5343.3  723.95
  5356.8  724.70  5564.3  727.04  5578.7  727.59  5587.4  727.21  5600.9  728.00
#Mann=3,-1,0
  4674.3    0.05       0  4996.0    0.04       0  5000.0    0.05       0
Bank Sta=4996,5000
Exp/Cntr=0.3,0.1

Type RM Length L Ch R = 1,734,94,94,94
BEGIN DESCRIPTION:
Harriet Creek Tributary 2_1 1.5
END DESCRIPTION:
XS GIS Cut Line= 3
      2327513.25      7068328.72      2327044.50      7068345.54
      2326956.21      7068383.37
#Sta/Elev= 30
  4715.9  726.44  4730.2  726.09  4740.2  724.24  4760.2  724.51  4770.2  723.99
  4800.2  723.47  4820.2  722.44  4880.3  720.87  4888.2  720.32  4893.2  720.49
  4920.3  719.51  4950.3  718.00  4960.3  717.02  4970.3  716.40  5000.3  716.02
  5008.3  715.69  5008.6  715.19  5012.1  715.19  5012.3  715.69  5020.3  716.31
  5030.3  716.22  5050.4  716.82  5070.4  717.01  5080.4  716.44  5110.4  716.07
  5140.4  717.68  5150.4  718.77  5160.4  719.20  5167.7  719.81  5281.0  721.90
#Mann=3,-1,0
  4715.9    0.05       0  5008.3    0.04       0  5012.3    0.05       0
Bank Sta=5008.3,5012.3
Exp/Cntr=0.3,0.1

Type RM Length L Ch R = 1,640,515,515,515
BEGIN DESCRIPTION:
Harriet Creek Tributary 2_1 1.0
END DESCRIPTION:
XS GIS Cut Line= 3
      2327494.26      7068259.36      2327179.00      7068260.00
      2327022.66      7068248.94
#Sta/Elev= 30
  4689.3  724.14  4734.6  722.70  4744.6  722.51  4764.6  721.73  4774.6  721.65
  4784.6  721.08  4814.6  720.21  4834.6  719.93  4864.6  719.24  4884.6  719.06
  4904.6  717.75  4914.6  716.82  4924.6  716.15  4934.6  715.73  4944.6  714.99
  4984.6  714.31  5000.1  714.23  5000.3  713.73  5003.8  713.73  5004.1  714.23
  5014.6  714.55  5024.6  714.31  5054.7  714.80  5064.7  715.13  5072.6  715.69
  5084.8  715.95  5094.8  716.55  5104.8  716.85  5124.9  717.87  5161.3  719.09
#Mann=3,-1,0
  4689.3    0.05       0  5000.1   0.033       0  5004.1    0.05       0
Bank Sta=5000.1,5004.1
Exp/Cntr=0.3,0.1

Type RM Length L Ch R = 1,125,0,0,0
BEGIN DESCRIPTION:
Harriet Creek Tributary 2_1 0.2
END DESCRIPTION:
XS GIS Cut Line= 4
      2327684.64      7068245.48      2327175.35      7067731.74
      2327139.77      7067802.91      2327008.76      7068253.07
#Sta/Elev= 30
  4258.1  727.06  4442.7  721.74  4520.5  720.06  4555.9  718.65  4584.2  718.51
  4800.6  713.95  4867.0  712.99  4874.1  713.28  4881.2  712.91  4888.2  711.50
  4895.3  711.15  4902.3  710.16  4949.9  708.84  4950.1  708.34  4953.6  708.34
  4953.9  708.84  5077.7  709.74  5082.9  709.25  5147.7  709.93  5183.0  710.91
  5203.8  713.11  5214.3  713.50  5299.6  714.77  5327.9  714.53  5333.1  715.27
  5371.8  715.90  5405.4  717.30  5422.6  717.08  5464.2  717.66  5529.9  719.48
#Mann=5,-1,0
  4258.1    0.05       0  4800.6    0.12       0  4949.9    0.07       0
  4953.9    0.12       0  5147.7    0.05       0
Bank Sta=4949.9,4953.9
Exp/Cntr=0.3,0.1

Chan Stop Cuts=-1