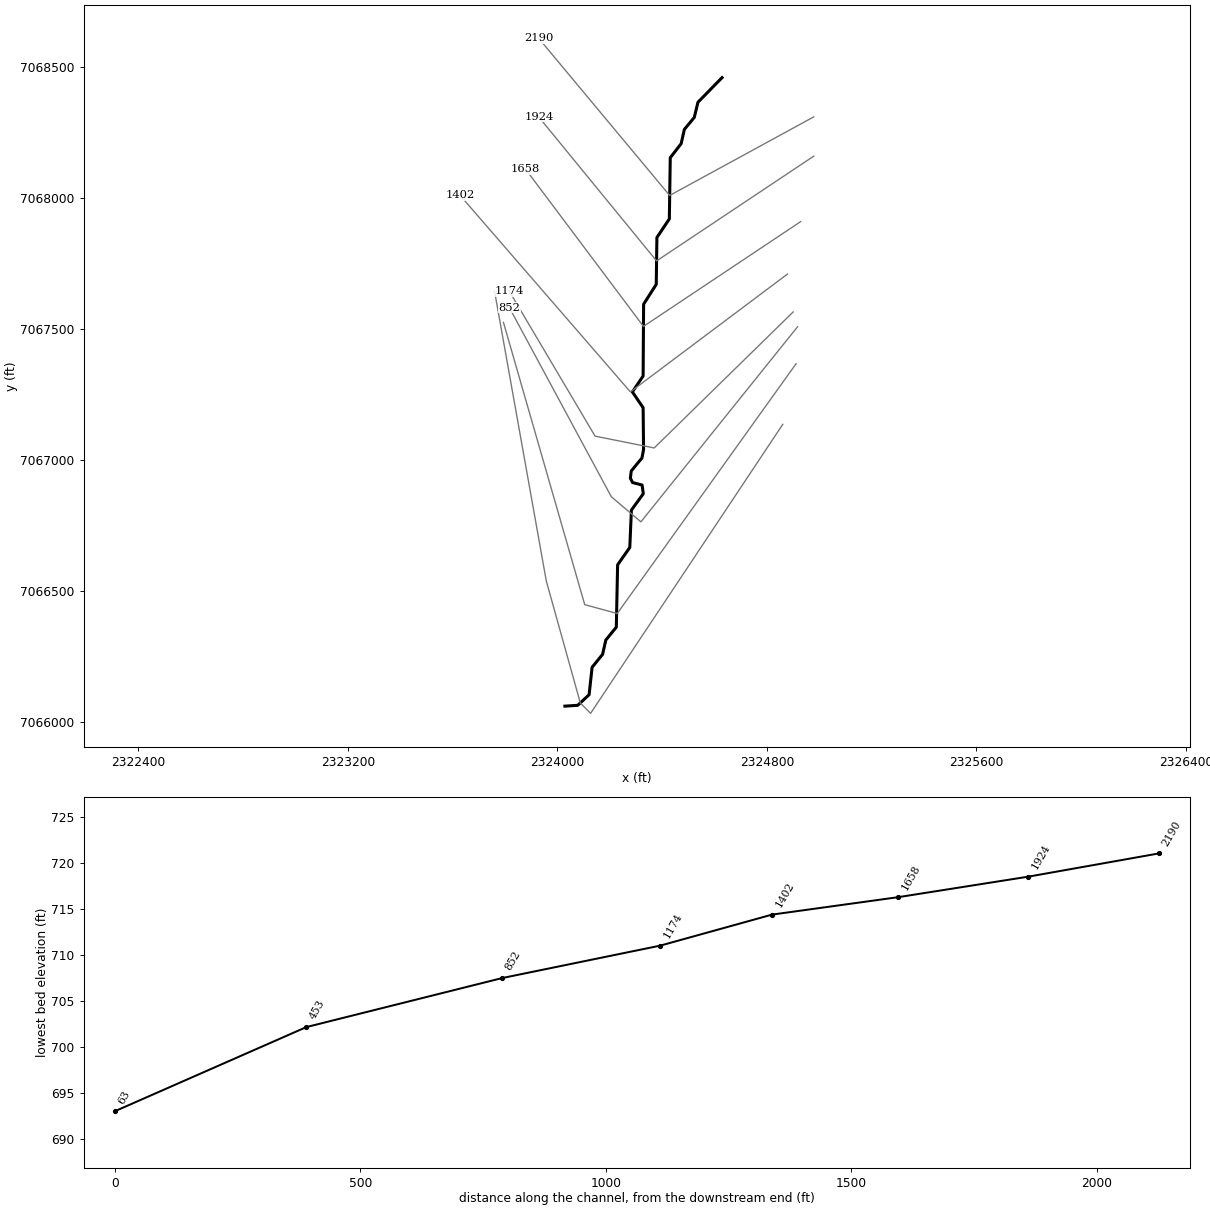
--- Harriet Creek Tributary 3.prj (project) ---

Proj Title=Harriet Creek Tributary 3 Base Level Engineering
Current Plan=p01
Default Exp/Contr=0.3,0.1
English Units
Geom File=g01
Flow File=f01
Plan File=p01
Y Axis Title=Elevation
X Axis Title(PF)=Main Channel Distance
X Axis Title(XS)=Station
BEGIN DESCRIPTION:
Harriet Creek Tributary 3
END DESCRIPTION:
DSS Export Rating Curves= 0
DSS Export Rating Curve Sorted= 0
DSS Export Volume Flow Curves= 0
DXF OffsetX= 0
DXF OffsetY= 0
DXF ScaleX= 1
DXF ScaleY= 10

--- Harriet Creek Tributary 3.p01 (plan) ---

Plan Title=Multiple Run
Program Version=4.10
Short Identifier=Multiple
Geom File=g01
Flow File=f01
Subcritical Flow
K Sum by GR= 0
Std Step Tol= 0.01
Critical Tol= 0.01
Num of Std Step Trials= 20
Max Error Tol= 0.3
Flow Tol Ratio= 0.001
Split Flow NTrial= 30
Split Flow Tol= 0.02
Split Flow Ratio= 0.02
Log Output Level= 0
Friction Slope Method= 0
Unsteady Friction Slope Method= 2
Unsteady Bridges Friction Slope Method= 1
Parabolic Critical Depth
Global Vel Dist= 1 , 1 , 1
Global Log Level= 0
CheckData=True
Encroach Param=-1 ,0,0, 0
BEGIN DESCRIPTION:
Multiple Run
END DESCRIPTION:
Computation Interval=1HOUR
Output Interval=1HOUR
Run HTab= 0
Run UNet= 0
Run PostProcess= 0
Run WQNet= 0
UNET Theta= 1
UNET Theta Warmup= 1
UNET ZTol= 0.02
UNET ZSATol= 0.05
UNET MxIter= 20
UNET MaxInSteps= 0
UNET DtIC= 0
UNET DtMin= 0
UNET MaxCRTS= 20
UNET WFStab= 2
UNET SFStab= 1
UNET WFX= 1
UNET SFX= 1
UNET DSS MLevel= 4
UNET DZMax Abort= 100
UNET Convert EG Bridges= 0
UNET Use Existing IB Tables=-1
UNET Froude Reduction=False
UNET Froude Limit= 1
UNET Froude Power= 10
UNET Time Slicing=0,0, 5
UNET Junction Losses=0
Instantaneous Interval=1HOUR
Write IC File= 0
Write IC File at Sim End=0
Echo Input=False
Echo Parameters=False
Echo Output=False
Write Detailed= 0
WQ AD Non Conservative
WQ ULTIMATE=-1
WQ Max Comp Step=1HOUR
WQ Output Interval=15MIN
WQ Output Selected Increments= 0
WQ Output face flow=0
WQ Output face velocity=0
WQ Output face area=0
WQ Output face dispersion=0
WQ Output cell volume=0
WQ Output cell surface area=0
WQ Output cell continuity=0
WQ Output cumulative cell continuity=0
WQ Output face conc=0
WQ Output face dconc_dx=0
WQ Output face courant=0
WQ Output face peclet=0
WQ Output face adv mass=0
WQ Output face disp mass=0
WQ Output cell mass=0
WQ Output cell source sink temp=0
WQ Output cell source sink nsm=0
WQ Output MaxMinRange=-1
WQ Daily Max Min Mean=-1
WQ Daily Range=0
WQ Daily Time=0
WQ Create Restart=0
WQ Fixed Restart=0
WQ System Summary=0
WQ Use Fixed Temperature=0
Sorting and Armoring Iterations= 10
XS Update Threshold= 0.02
Hydraulics Update Threshold= 0.02
Energy Slope Method= 1
Volume Change Method= 0
XS Weighting Method= 0
Number of US Weighted Cross Sections= 1
Number of DS Weighted Cross Sections= 1
Upstream XS Weight=0.25
Main XS Weight=0.5
Downstream XS Weight=0.25
Number of DS XS's Weighted with US Boundary= 1
Upstream Boundary Weight= 1
Weight of XSs Associated with US Boundary= 0
Number of US XS's Weighted with DS Boundary= 1
Downstream Boundary Weight= 0.5
Weight of XSs Associated with DS Boundary= 0.5
Sediment Output Level= 4
Mass or Volume Output= 0
Output Increment Type= 1
Profile and TS Output Increment= 10
XS Output Flag= 0
XS Output Increment= 10
Disregard all LS=0
Disregard all Conn=0
Disregard all Breaches=0
Disregard all Pumps=0

--- Harriet Creek Tributary 3.f01 (steady flow) ---

Flow Title=Multiple
Number of Profiles=7
Profile Names=10-year,25-year,50-year,1pct_min,100-year,1pct_plu,500-year
River Rch & RM= Harriet Creek Tr,Reach-1,2190
     184     233     271     157     314     626     420
Boundary for River Rch & Prof#=Harriet Creek Tr,Reach-1,1
Up Type=0
Dn Type=3
Dn Slope=0.005
Boundary for River Rch & Prof#=Harriet Creek Tr,Reach-1,2
Up Type=0
Dn Type=3
Dn Slope=0.005
Boundary for River Rch & Prof#=Harriet Creek Tr,Reach-1,3
Up Type=0
Dn Type=3
Dn Slope=0.005
Boundary for River Rch & Prof#=Harriet Creek Tr,Reach-1,4
Up Type=0
Dn Type=3
Dn Slope=0.005
Boundary for River Rch & Prof#=Harriet Creek Tr,Reach-1,5
Up Type=0
Dn Type=3
Dn Slope=0.005
Boundary for River Rch & Prof#=Harriet Creek Tr,Reach-1,6
Up Type=0
Dn Type=3
Dn Slope=0.005
Boundary for River Rch & Prof#=Harriet Creek Tr,Reach-1,7
Up Type=0
Dn Type=3
Dn Slope=0.005

--- Harriet Creek Tributary 3.g01 (geometry) ---

Geom Title=Existing Conditions

River Reach=Harriet Creek Tr,Reach-1
Reach XY= 30
      2324629.00      7068460.00      2324537.09      7068366.08
      2324522.90      7068307.81      2324485.08      7068262.20
      2324472.88      7068207.82      2324431.24      7068154.07
      2324427.78      7067920.50      2324380.22      7067849.49
      2324377.78      7067670.51      2324329.52      7067594.78
      2324327.62      7067320.44      2324286.56      7067260.00
      2324327.62      7067199.56      2324329.35      7067039.84
      2324323.20      7067007.62      2324282.28      7066957.92
      2324278.97      7066930.43      2324287.31      7066913.70
      2324323.71      7066904.24      2324328.31      7066871.05
      2324282.83      7066808.47      2324276.73      7066665.94
      2324230.22      7066599.50      2324225.25      7066361.55
      2324185.12      7066312.18      2324172.89      7066257.82
      2324132.83      7066208.41      2324121.36      7066103.55
      2324078.01      7066063.12      2324029.00      7066060.00

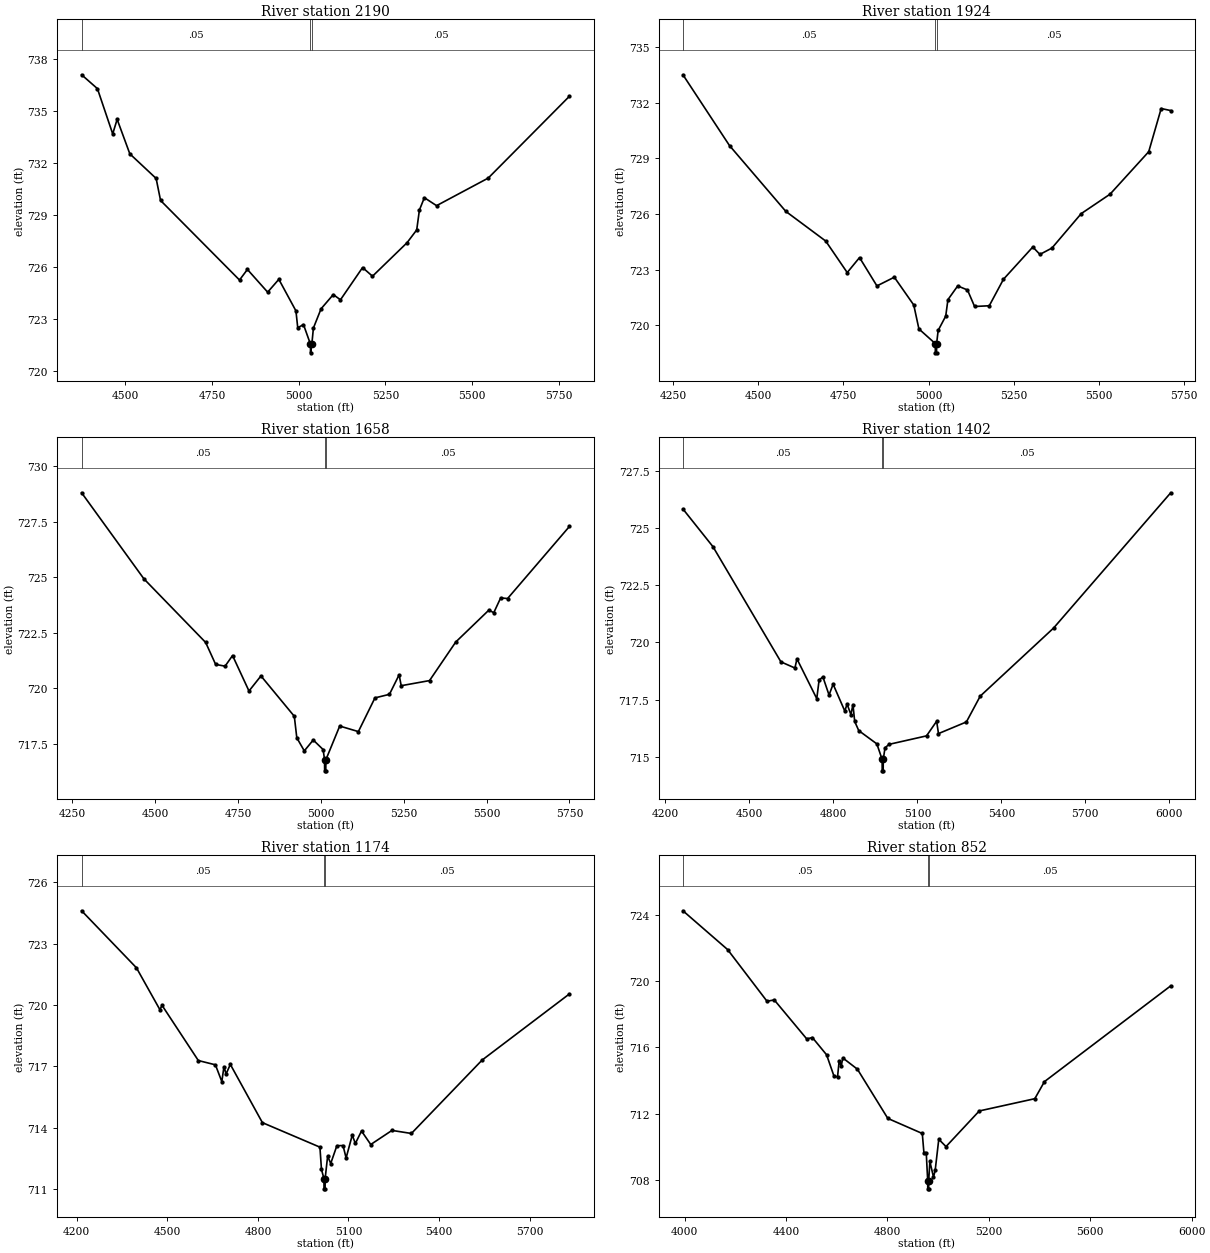
Type RM Length L Ch R = 1,2190,266,266,266
BEGIN DESCRIPTION:
Harriet Creek Tributary 3 4.0
END DESCRIPTION:
XS GIS Cut Line= 3
      2324978.99      7068309.99      2324429.00      7068010.00
      2323929.01      7068609.99
#Sta/Elev= 30
  4373.6  737.08  4419.2  736.28  4463.3  733.67  4476.1  734.51  4512.7  732.52
  4588.6  731.10  4601.4  729.83  4829.2  725.24  4852.0  725.85  4910.4  724.54
  4942.7  725.28  4992.0  723.46  4997.2  722.49  5013.8  722.67  5033.9  721.54
  5034.1  721.04  5037.9  721.54  5042.4  722.47  5064.5  723.58  5099.7  724.40
  5120.5  724.10  5184.3  725.96  5212.9  725.46  5312.5  727.39  5340.5  728.13
  5348.3  729.28  5362.6  729.99  5397.8  729.53  5546.8  731.12  5781.1  735.84
#Mann=3,-1,0
  4373.6    0.05       0  5033.9   0.033       0  5037.9    0.05       0
Bank Sta=5033.9,5037.9
Exp/Cntr=0.3,0.1

Type RM Length L Ch R = 1,1924,266,266,266
BEGIN DESCRIPTION:
Harriet Creek Tributary 3 3.0
END DESCRIPTION:
XS GIS Cut Line= 3
      2324978.99      7068159.99      2324379.00      7067760.00
      2323929.02      7068309.97
#Sta/Elev= 30
  4278.9  733.51  4415.6  729.69  4580.9  726.14  4698.0  724.54  4761.1  722.84
  4797.2  723.65  4848.3  722.12  4899.3  722.59  4956.4  721.09  4971.5  719.80
  5019.5  719.01  5019.8  718.51  5023.3  718.51  5023.5  719.01  5028.0  719.72
  5050.2  720.49  5056.7  721.38  5085.4  722.12  5114.1  721.90  5134.9  721.01
  5178.0  721.05  5219.7  722.48  5305.8  724.22  5326.6  723.82  5361.8  724.16
  5447.9  726.02  5532.6  727.07  5646.0  729.36  5682.6  731.69  5710.6  731.58
#Mann=3,-1,0
  4278.9    0.05       0  5019.5   0.033       0  5023.5    0.05       0
Bank Sta=5019.5,5023.5
Exp/Cntr=0.3,0.1

Type RM Length L Ch R = 1,1658,256,256,256
BEGIN DESCRIPTION:
Harriet Creek Tributary 3 2.0
END DESCRIPTION:
XS GIS Cut Line= 3
      2324929.04      7067910.03      2324329.00      7067510.00
      2323878.97      7068110.03
#Sta/Elev= 30
  4278.7  728.81  4466.5  724.93  4652.8  722.06  4682.9  721.07  4711.4  720.99
  4733.9  721.47  4783.5  719.87  4819.6  720.55  4920.2  718.73  4927.7  717.76
  4950.3  717.17  4977.3  717.66  5007.1  717.23  5011.4  716.77  5011.6  716.27
  5015.1  716.27  5015.4  716.77  5057.1  718.29  5113.4  718.04  5163.4  719.56
  5207.1  719.72  5236.3  720.60  5242.6  720.11  5328.0  720.34  5407.1  722.08
  5507.1  723.52  5521.7  723.40  5542.6  724.07  5563.4  724.04  5749.9  727.29
#Mann=3,-1,0
  4278.7    0.05       0  5011.4   0.033       0  5015.4    0.05       0
Bank Sta=5011.4,5015.4
Exp/Cntr=0.3,0.1

Type RM Length L Ch R = 1,1402,228,228,228
BEGIN DESCRIPTION:
Harriet Creek Tributary 3 1.0
END DESCRIPTION:
XS GIS Cut Line= 3
      2324879.02      7067710.01      2324279.00      7067260.00
      2323628.99      7068010.01
#Sta/Elev= 30
  4262.5  725.84  4369.8  724.19  4612.5  719.15  4662.5  718.88  4669.8  719.28
  4740.6  717.54  4749.0  718.36  4762.5  718.49  4784.4  717.70  4799.0  718.17
  4840.6  717.00  4849.0  717.30  4862.5  716.84  4869.8  717.28  4876.1  716.54
  4890.6  716.14  4955.2  715.56  4974.1  714.88  4974.3  714.38  4977.8  714.38
  4978.1  714.88  4984.4  715.39  4999.0  715.54  5132.6  715.91  5168.8  716.55
  5175.4  716.01  5275.1  716.52  5324.5  717.65  5586.6  720.63  6005.0  726.55
#Mann=3,-1,0
  4262.5    0.05       0  4974.1   0.033       0  4978.1    0.05       0
Bank Sta=4974.1,4978.1
Exp/Cntr=0.3,0.1

Type RM Length L Ch R = 1,1174,322,322,322
BEGIN DESCRIPTION:
Harriet Creek Tributary 3 0.4
END DESCRIPTION:
XS GIS Cut Line= 4
      2324900.50      7067565.12      2324369.92      7067045.83
      2324144.15      7067090.98      2323816.78      7067644.11
#Sta/Elev= 30
  4216.3  724.61  4397.8  721.82  4475.5  719.77  4482.7  719.98  4602.8  717.28
  4659.4  717.07  4680.6  716.25  4687.7  716.98  4694.7  716.62  4708.8  717.09
  4815.0  714.24  5005.5  713.04  5010.6  711.95  5018.8  711.50  5019.1  711.00
  5022.6  711.00  5022.8  711.50  5031.0  712.60  5041.2  712.24  5061.6  713.11
  5082.0  713.12  5092.2  712.51  5112.6  713.63  5122.8  713.22  5143.2  713.83
  5173.8  713.17  5244.1  713.86  5308.4  713.71  5542.4  717.30  5831.7  720.54
#Mann=3,-1,0
  4216.3    0.05       0  5018.8   0.033       0  5022.8    0.05       0
Bank Sta=5018.8,5022.8
Exp/Cntr=0.3,0.1

Type RM Length L Ch R = 1,852,399,399,399
BEGIN DESCRIPTION:
Harriet Creek Tributary 3 0.3
END DESCRIPTION:
XS GIS Cut Line= 4
      2324917.39      7067508.64      2324319.12      7066763.62
      2324206.23      7066859.57      2323816.78      7067582.03
#Sta/Elev= 30
  3993.0  724.25  4169.2  721.91  4324.7  718.79  4353.3  718.87  4481.3  716.52
  4503.7  716.60  4559.7  715.56  4588.5  714.29  4602.9  714.22  4609.3  715.19
  4617.3  714.87  4623.7  715.37  4681.3  714.69  4801.3  711.72  4937.3  710.81
  4943.7  709.65  4952.9  709.65  4958.6  707.97  4958.9  707.47  4962.4  707.47
  4962.6  707.97  4967.2  709.12  4981.5  708.18  4988.1  708.58  5002.3  710.46
  5030.9  710.02  5162.1  712.17  5381.2  712.91  5419.2  713.94  5917.4  719.72
#Mann=3,-1,0
  3993.0    0.05       0  4958.6   0.033       0  4962.6    0.05       0
Bank Sta=4958.6,4962.6
Exp/Cntr=0.3,0.1

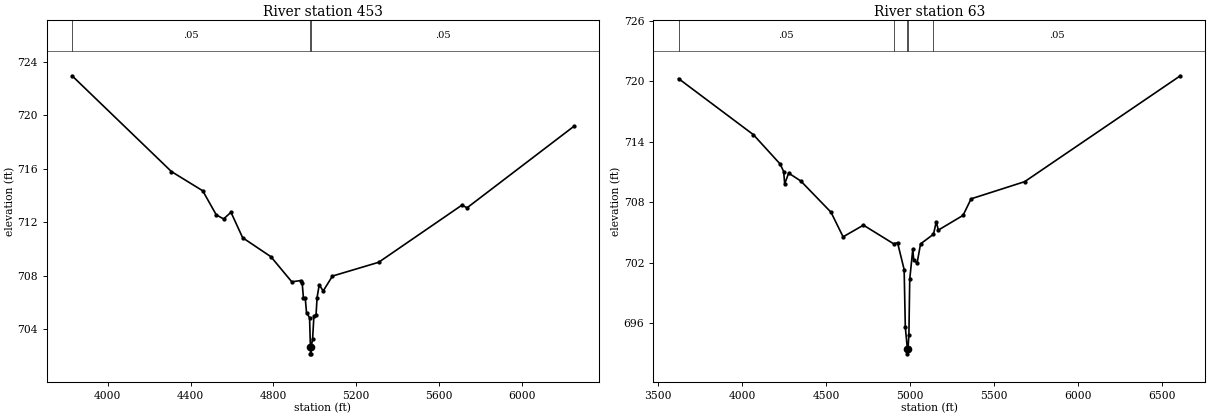
Type RM Length L Ch R = 1,453,390,390,390
BEGIN DESCRIPTION:
Harriet Creek Tributary 3 0.2
END DESCRIPTION:
XS GIS Cut Line= 4
      2324911.76      7067367.55      2324228.81      7066413.68
      2324104.64      7066447.54      2323794.29      7067525.28
#Sta/Elev= 30
  3827.8  722.97  4307.8  715.79  4458.9  714.35  4524.0  712.55  4559.6  712.24
  4595.2  712.74  4651.7  710.83  4788.1  709.41  4888.8  707.53  4931.7  707.62
  4939.2  707.42  4945.3  706.30  4953.9  706.30  4960.1  705.22  4974.8  704.84
  4978.9  702.63  4979.2  702.13  4982.7  702.13  4982.9  702.63  4989.5  703.26
  4995.7  704.95  5006.0  705.02  5011.1  706.35  5021.5  707.31  5040.5  706.84
  5085.4  707.96  5308.3  708.99  5710.0  713.27  5735.8  713.08  6251.2  719.18
#Mann=3,-1,0
  3827.8    0.05       0  4978.9   0.033       0  4982.9    0.05       0
Bank Sta=4978.9,4982.9
Exp/Cntr=0.3,0.1

Type RM Length L Ch R = 1,63,0,0,0
BEGIN DESCRIPTION:
Harriet Creek Tributary 3 0.1
END DESCRIPTION:
XS GIS Cut Line= 5
      2324860.97      7067136.15      2324126.97      7066032.35
      2324087.83      7066072.20      2323957.89      7066537.85
      2323760.35      7067644.08
#Sta/Elev= 30
  3621.0  720.26  4066.9  714.70  4226.2  711.79  4247.2  711.04  4253.2  709.82
  4276.9  710.89  4348.9  710.11  4529.1  707.01  4601.1  704.57  4722.2  705.73
  4902.3  703.88  4925.4  703.99  4964.7  701.33  4971.7  695.61  4983.8  693.47
  4984.1  692.97  4987.8  693.47  4993.0  694.86  4998.0  700.35  5016.2  703.35
  5021.4  702.32  5041.7  701.96  5062.4  703.87  5139.5  704.83  5155.9  706.06
  5168.5  705.24  5315.6  706.70  5363.5  708.34  5682.4  710.04  6609.6  720.54
#Mann=5,-1,0
  3621.0    0.05       0  4902.3    0.12       0  4983.8    0.07       0
  4987.8    0.12       0  5139.5    0.05       0
Bank Sta=4983.8,4987.8
Exp/Cntr=0.3,0.1

Chan Stop Cuts=-1