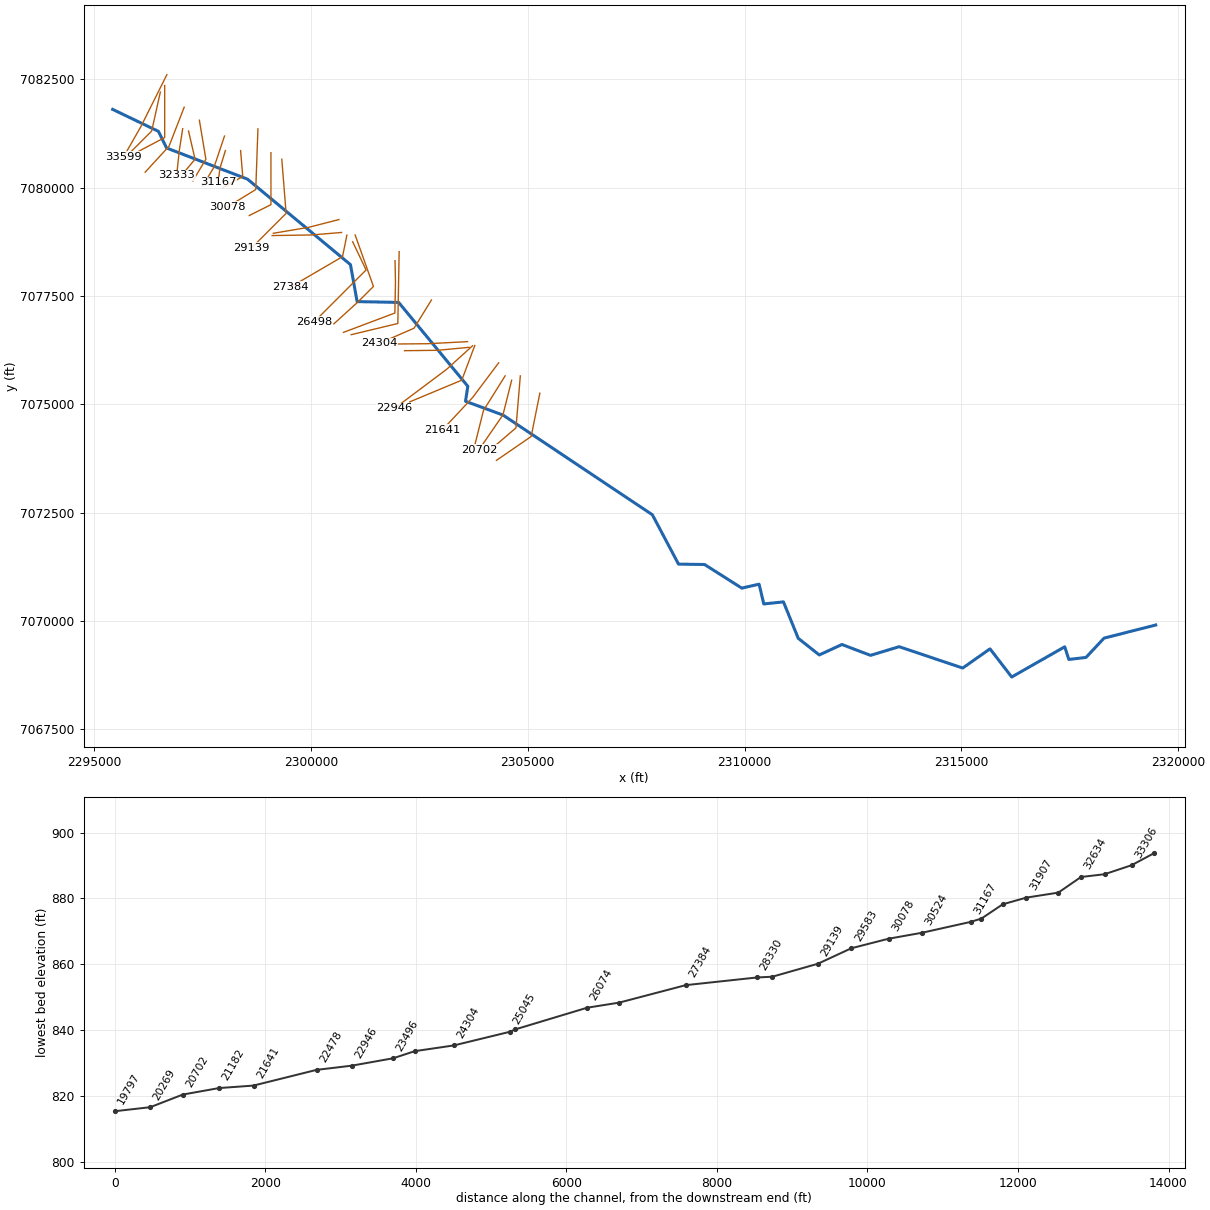
--- Harriet Creek Tributary 5.prj (project) ---

Proj Title=Harriet Creek Tributary 5 Base Level Engineering
Current Plan=p01
Default Exp/Contr=0.3,0.1
English Units
Geom File=g01
Flow File=f01
Plan File=p01
BEGIN DESCRIPTION:
Harriet Creek Tributary 5
END DESCRIPTION:

--- Harriet Creek Tributary 5.p01 (plan) ---

Plan Title=Multiple Run
Short Identifier=Multiple
Geom File=g01
Flow File=f01
Subcritical Flow
K Sum by GR= 0
Std Step Tol= 0.01
Critical Tol= 0.01
Num of Std Step Trials= 20
Max Error Tol= 0.3
Flow Tol Ratio= 0.001
Split Flow NTrial= 30
Split Flow Tol= 0.02
Split Flow Ratio= 0.02
Log Output Level= 0
Friction Slope Method= 1
Unsteady Friction Slope Method= 2
Unsteady Bridges Friction Slope Method= 1
Parabolic Critical Depth
Global Vel Dist=  1 , 1 , 1
Global Log Level= 0
CheckData=True
Encroach Param= -1, 0, 0, 0
BEGIN DESCRIPTION:
Multiple Run
END DESCRIPTION:

--- Harriet Creek Tributary 5.f01 (steady flow) ---

Flow Title=Multiple
Number of Profiles=7
Profile Names=10-year,25-year,50-year,1pct_min,100-year,1pct_plu,500-year
River Rch & RM= Harriet Creek Tr,Reach-1,33599
     337     445     530     315     628    1250     881
River Rch & RM= Harriet Creek Tr,Reach-1,32947
     579     791     965     585    1170    2330    1710
River Rch & RM= Harriet Creek Tr,Reach-1,29583
     714     985    1210     736    1470    2930    2180
River Rch & RM= Harriet Creek Tr,Reach-1,25117
    1040    1460    1820    1120    2230    4460    3390
River Rch & RM= Harriet Creek Tr,Reach-1,22478
    1190    1690    2110    1300    2600    5190    3980
River Rch & RM= Harriet Creek Tr,Reach-1,21641
    1310    1860    2330    1450    2890    5760    4430
River Rch & RM= Harriet Creek Tr,Reach-1,17930
    1440    2060    2590    1610    3210    6400    4950
River Rch & RM= Harriet Creek Tr,Reach-1,16635
    1560    2230    2810    1750    3490    6960    5410
River Rch & RM= Harriet Creek Tr,Reach-1,13334
    1660    2380    3010    1870    3740    7460    5810
River Rch & RM= Harriet Creek Tr,Reach-1,9188
    1770    2550    3230    2020    4020    8020    6270
River Rch & RM= Harriet Creek Tr,Reach-1,5971
    1880    2710    3430    2150    4280    8540    6690
River Rch & RM= Harriet Creek Tr,Reach-1,1263
    1890    2730    3450    2160    4300    8580    6720
Boundary for River Rch & Prof#=Harriet Creek Tr,Reach-1,1
Up Type=0
Dn Type=3
Dn Slope=0.005
Boundary for River Rch & Prof#=Harriet Creek Tr,Reach-1,2
Up Type=0
Dn Type=3
Dn Slope=0.005
Boundary for River Rch & Prof#=Harriet Creek Tr,Reach-1,3
Up Type=0
Dn Type=3
Dn Slope=0.005
Boundary for River Rch & Prof#=Harriet Creek Tr,Reach-1,4
Up Type=0
Dn Type=3
Dn Slope=0.005
Boundary for River Rch & Prof#=Harriet Creek Tr,Reach-1,5
Up Type=0
Dn Type=3
Dn Slope=0.005
Boundary for River Rch & Prof#=Harriet Creek Tr,Reach-1,6
Up Type=0
Dn Type=3
Dn Slope=0.005
Boundary for River Rch & Prof#=Harriet Creek Tr,Reach-1,7
Up Type=0
Dn Type=3
Dn Slope=0.005

--- Harriet Creek Tributary 5.g01 (geometry) ---

Geom Title=Existing Conditions

River Reach=Harriet Creek Tr,Reach-1
Reach XY= 30
      2295429.00      7081810.00      2296485.19      7081302.19
      2296671.93      7080918.99      2298538.71      7080199.25
      2300912.61      7078226.73      2301065.76      7077373.59
      2302023.73      7077355.01      2303617.93      7075420.07
      2303565.76      7075073.10      2304431.45      7074754.53
      2307873.39      7072454.41      2308476.70      7071315.09
      2309077.54      7071306.46      2309935.04      7070761.61
      2310335.21      7070852.20      2310442.20      7070396.25
      2310896.21      7070443.78      2311236.73      7069603.50
      2311722.27      7069219.11      2312244.34      7069460.04
      2312903.88      7069209.71      2313563.84      7069409.62
      2315029.00      7068917.08      2315658.74      7069360.13
      2316158.97      7068710.06      2317381.14      7069406.89
      2317476.29      7069115.28      2317873.15      7069162.06
      2318287.31      7069606.92      2319479.00      7069910.00

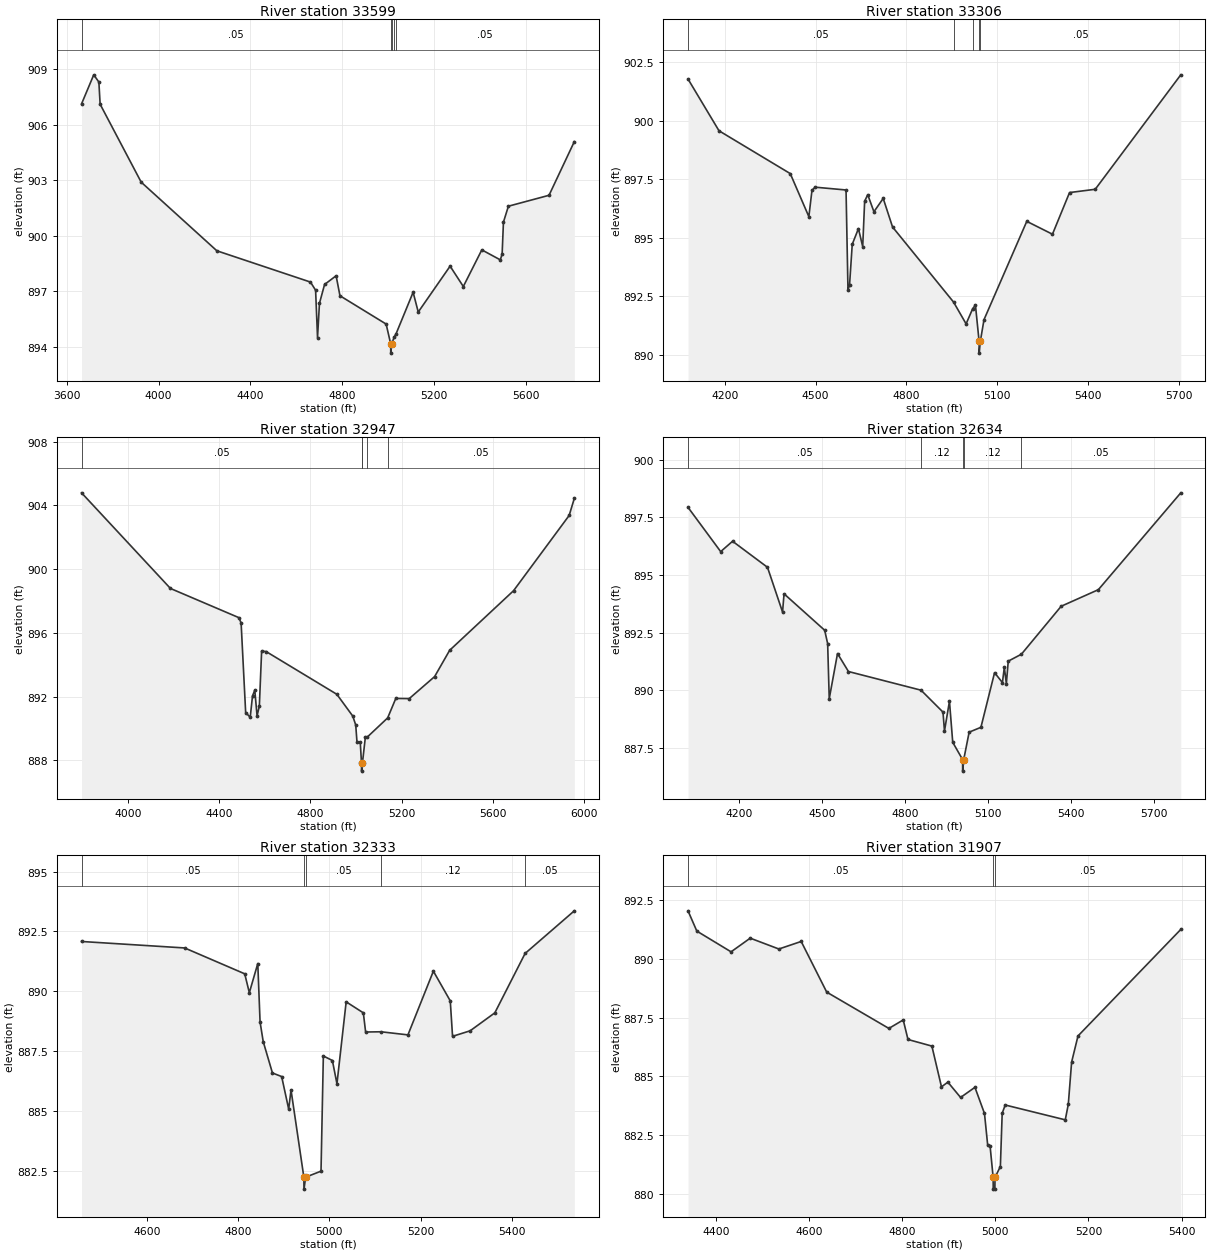
Type RM Length L Ch R = 1,33599,293,293,293
BEGIN DESCRIPTION:
Harriet Creek Tributary 5 60.0
END DESCRIPTION:
XS GIS Cut Line= 3
      2296679.00      7082609.99      2296079.00      7081410.00
      2295678.98      7080709.96
#Sta/Elev= 30
  3664.5  907.13  3717.6  908.70  3740.0  908.31  3745.5  907.11  3924.4  902.90
  4254.3  899.19  4662.3  897.50  4684.7  897.06  4693.1  894.50  4701.5  896.35
  4723.8  897.37  4774.1  897.84  4790.9  896.76  4992.2  895.23  5012.0  894.16
  5012.3  893.66  5016.0  894.16  5027.2  894.52  5035.6  894.71  5109.8  896.95
  5132.1  895.88  5271.0  898.36  5328.6  897.26  5409.2  899.24  5489.9  898.70
  5497.8  899.02  5503.5  900.74  5525.1  901.60  5702.2  902.19  5812.4  905.09
#Mann=5,-1,0
  3664.5    0.05       0  5012.0   0.033       0  5016.0    0.05       0
  5027.2    0.12       0  5035.6    0.05       0
Bank Sta=5012,5016
Exp/Cntr=0.3,0.1

Type RM Length L Ch R = 1,33306,359,359,359
BEGIN DESCRIPTION:
Harriet Creek Tributary 5 59.0
END DESCRIPTION:
XS GIS Cut Line= 3
      2296528.99      7082209.96      2296329.00      7081310.00
      2295829.01      7080810.01
#Sta/Elev= 30
  4078.1  901.78  4180.5  899.57  4416.1  897.74  4477.6  895.90  4487.8  897.02
  4498.1  897.16  4600.5  897.04  4606.9  892.78  4612.0  892.96  4621.0  894.72
  4641.5  895.39  4655.6  894.62  4662.0  896.56  4672.2  896.84  4692.7  896.11
  4723.4  896.68  4754.2  895.46  4956.0  892.25  4997.4  891.32  5019.2  891.97
  5028.3  892.12  5040.4  890.57  5040.7  890.07  5044.4  890.57  5056.6  891.50
  5198.0  895.70  5282.9  895.15  5339.4  896.93  5424.3  897.07  5707.1  901.96
#Mann=5,-1,0
  4078.1    0.05       0  4956.0    0.12       0  5019.2    0.05       0
  5040.4    0.07       0  5044.4    0.05       0
Bank Sta=5040.4,5044.4
Exp/Cntr=0.3,0.1

Type RM Length L Ch R = 1,32947,313,313,313
BEGIN DESCRIPTION:
Harriet Creek Tributary 5 58.0
END DESCRIPTION:
XS GIS Cut Line= 3
      2296629.00      7082360.03      2296629.00      7081160.00
      2295779.00      7080710.00
#Sta/Elev= 30
  3796.1  904.79  4186.1  898.79  4486.1  896.96  4496.1  896.63  4516.1  891.00
  4536.1  890.71  4546.1  892.05  4556.1  892.41  4566.1  890.80  4576.1  891.41
  4586.1  894.86  4606.1  894.83  4916.1  892.15  4986.1  890.78  4999.0  890.22
  5004.3  889.18  5018.8  889.16  5024.3  887.83  5024.6  887.33  5028.3  887.83
  5041.4  889.49  5048.4  889.45  5139.1  890.67  5174.7  891.89  5233.7  891.88
  5345.0  893.26  5411.0  894.91  5691.4  898.65  5935.3  903.37  5957.9  904.44
#Mann=5,-1,0
  3796.1    0.05       0  5024.3   0.033       0  5028.3    0.05       0
  5048.4    0.12       0  5139.1    0.05       0
Bank Sta=5024.3,5028.3
Exp/Cntr=0.3,0.1

Type RM Length L Ch R = 1,32634,301,301,301
BEGIN DESCRIPTION:
Harriet Creek Tributary 5 57.0
END DESCRIPTION:
XS GIS Cut Line= 3
      2297078.99      7081859.97      2296729.00      7080960.00
      2296178.98      7080359.97
#Sta/Elev= 30
  4016.8  897.93  4134.8  896.01  4177.7  896.46  4303.8  895.33  4358.2  893.39
  4363.6  894.18  4510.3  892.60  4521.1  892.02  4526.8  889.63  4556.7  891.59
  4596.2  890.81  4858.4  890.00  4937.6  889.05  4943.0  888.23  4961.0  889.52
  4972.8  887.74  5008.5  886.99  5008.7  886.49  5012.5  886.99  5032.1  888.18
  5074.6  888.39  5123.9  890.76  5152.3  890.33  5159.1  890.99  5166.5  890.29
  5173.3  891.26  5220.8  891.56  5364.4  893.64  5498.8  894.36  5796.4  898.56
#Mann=5,-1,0
  4016.8    0.05       0  4858.4    0.12       0  5008.5    0.07       0
  5012.5    0.12       0  5220.8    0.05       0
Bank Sta=5008.5,5012.5
Exp/Cntr=0.3,0.1

Type RM Length L Ch R = 1,32333,426,426,426
BEGIN DESCRIPTION:
Harriet Creek Tributary 5 56.0
END DESCRIPTION:
XS GIS Cut Line= 3
      2297044.19      7081363.07      2296966.08      7080863.98
      2296905.52      7080293.05
#Sta/Elev= 30
  4457.2  892.08  4683.0  891.81  4814.6  890.73  4824.7  889.94  4843.2  891.16
  4848.2  888.72  4855.1  887.90  4875.3  886.59  4895.5  886.44  4910.9  885.08
  4916.0  885.88  4944.1  882.24  4944.4  881.74  4948.1  882.24  4981.7  882.49
  4986.8  887.30  5006.6  887.11  5016.6  886.14  5036.8  889.56  5074.4  889.10
  5079.4  888.30  5113.1  888.31  5172.1  888.18  5227.8  890.84  5264.8  889.60
  5269.8  888.12  5308.3  888.35  5362.4  889.10  5428.7  891.58  5536.5  893.36
#Mann=5,-1,0
  4457.2    0.05       0  4944.1   0.033       0  4948.1    0.05       0
  5113.1    0.12       0  5428.7    0.05       0
Bank Sta=4944.1,4948.1
Exp/Cntr=0.3,0.1

Type RM Length L Ch R = 1,31907,313,313,313
BEGIN DESCRIPTION:
Harriet Creek Tributary 5 55.0
END DESCRIPTION:
XS GIS Cut Line= 3
      2297178.99      7081310.04      2297329.00      7080660.00
      2297079.02      7080360.03
#Sta/Elev= 30
  4340.6  892.03  4359.5  891.17  4433.0  890.29  4474.1  890.87  4535.6  890.41
  4583.5  890.73  4638.3  888.58  4771.7  887.04  4802.5  887.40  4812.7  886.57
  4864.0  886.29  4884.6  884.56  4898.3  884.76  4925.6  884.11  4956.4  884.54
  4976.9  883.43  4983.8  882.08  4988.9  882.05  4995.5  880.72  4995.7  880.22
  4999.2  880.22  4999.5  880.72  5011.0  881.18  5014.9  883.44  5021.4  883.79
  5150.3  883.16  5156.8  883.82  5163.9  885.61  5177.6  886.72  5398.2  891.24
#Mann=3,-1,0
  4340.6    0.05       0  4995.5   0.033       0  4999.5    0.05       0
Bank Sta=4995.5,4999.5
Exp/Cntr=0.3,0.1

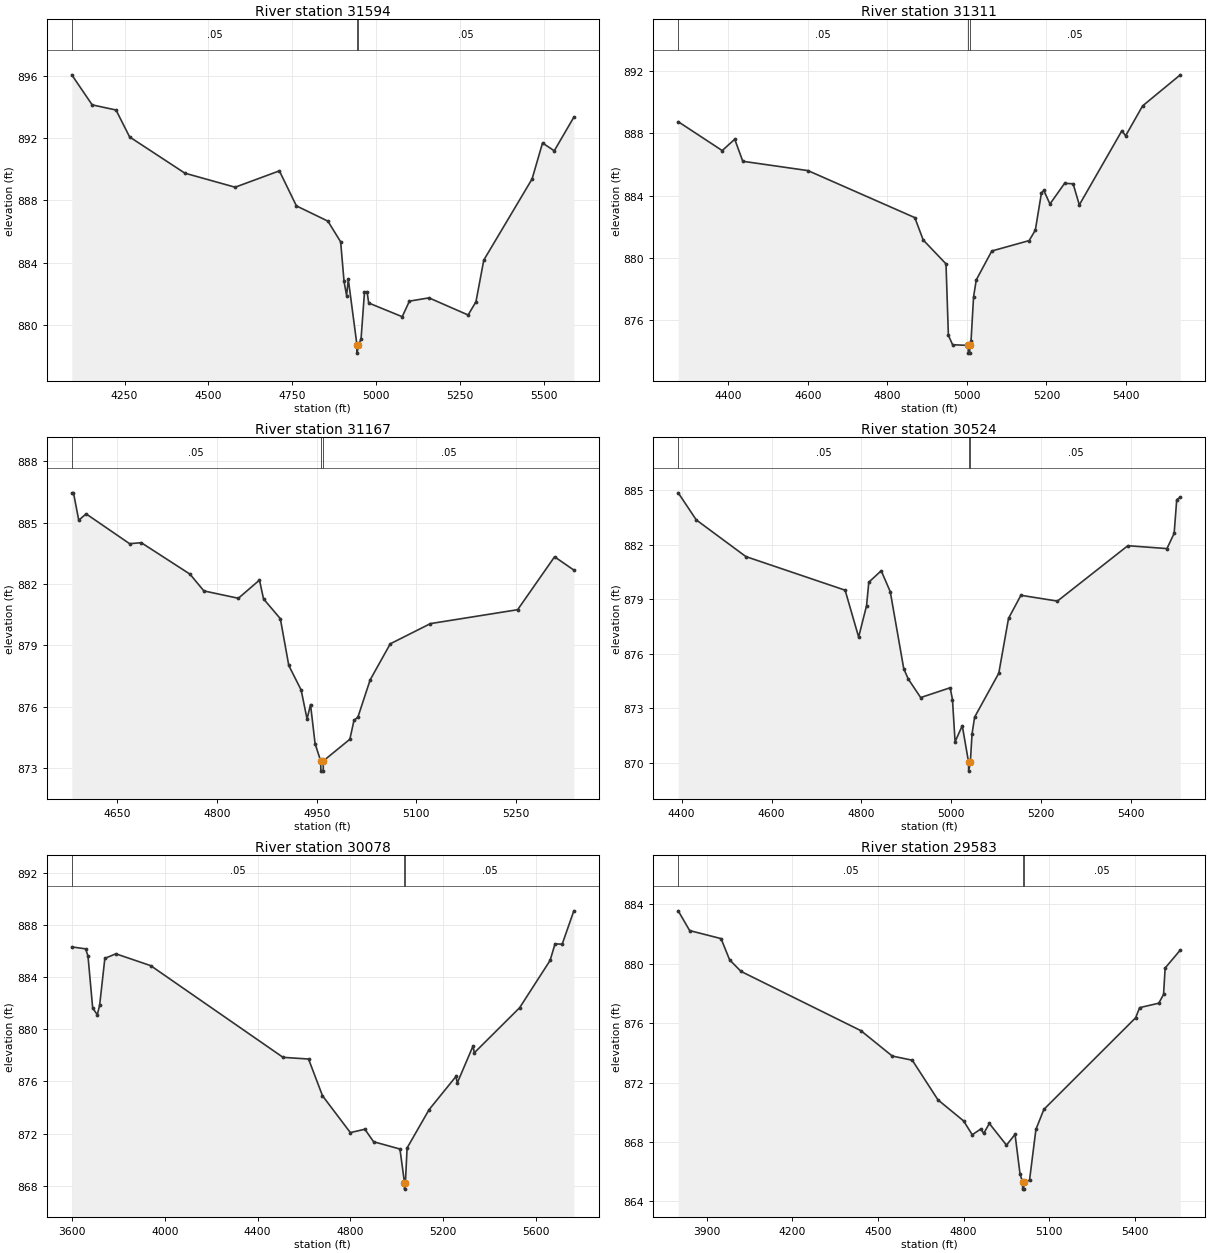
Type RM Length L Ch R = 1,31594,283,283,283
BEGIN DESCRIPTION:
Harriet Creek Tributary 5 54.0
END DESCRIPTION:
XS GIS Cut Line= 3
      2297429.00      7081559.99      2297579.00      7080660.00
      2297279.00      7080160.00
#Sta/Elev= 30
  4092.9  896.07  4153.7  894.14  4224.7  893.81  4265.2  892.08  4430.0  889.75
  4579.5  888.85  4711.3  889.90  4762.0  887.65  4855.8  886.67  4893.8  885.34
  4903.9  882.80  4911.5  881.89  4916.6  882.93  4942.5  878.69  4942.7  878.19
  4946.5  878.69  4954.6  879.11  4964.7  882.09  4972.4  882.14  4977.4  881.41
  5077.2  880.53  5098.6  881.53  5156.9  881.74  5273.5  880.64  5296.8  881.49
  5320.2  884.17  5464.0  889.38  5495.1  891.69  5530.1  891.19  5588.4  893.35
#Mann=3,-1,0
  4092.9    0.05       0  4942.5   0.033       0  4946.5    0.05       0
Bank Sta=4942.5,4946.5
Exp/Cntr=0.3,0.1

Type RM Length L Ch R = 1,31311,144,144,144
BEGIN DESCRIPTION:
Harriet Creek Tributary 5 53.0
END DESCRIPTION:
XS GIS Cut Line= 3
      2298007.75      7081193.88      2297769.03      7080482.04
      2297504.70      7080044.37
#Sta/Elev= 30
  4274.3  888.76  4384.8  886.90  4416.3  887.63  4436.6  886.21  4600.3  885.61
  4869.0  882.58  4890.1  881.14  4947.4  879.60  4953.4  875.00  4964.0  874.39
  5003.2  874.35  5003.4  873.85  5006.9  873.85  5007.2  874.35  5010.4  874.66
  5016.7  877.48  5023.5  878.57  5062.5  880.43  5156.4  881.10  5171.9  881.77
  5187.4  884.18  5193.2  884.33  5208.7  883.46  5245.6  884.79  5267.0  884.76
  5282.5  883.40  5389.6  888.18  5398.9  887.85  5441.6  889.78  5536.4  891.78
#Mann=3,-1,0
  4274.3    0.05       0  5003.2   0.033       0  5007.2    0.05       0
Bank Sta=5003.2,5007.2
Exp/Cntr=0.3,0.1

Type RM Length L Ch R = 1,31167,643,643,643
BEGIN DESCRIPTION:
Harriet Creek Tributary 5 52.0
END DESCRIPTION:
XS GIS Cut Line= 3
      2298029.01      7080860.03      2297903.58      7080451.65
      2297860.17      7080126.14
#Sta/Elev= 30
  4581.3  886.46  4583.9  886.46  4591.8  885.12  4602.9  885.43  4668.4  883.97
  4685.9  884.02  4759.2  882.48  4780.1  881.66  4832.0  881.30  4863.8  882.19
  4869.9  881.27  4895.2  880.30  4907.9  878.01  4926.5  876.81  4935.4  875.39
  4940.6  876.10  4947.5  874.18  4955.9  873.34  4956.2  872.84  4959.7  872.84
  4959.9  873.34  4999.8  874.40  5006.0  875.32  5011.9  875.48  5030.4  877.31
  5060.6  879.07  5121.1  880.06  5252.3  880.74  5307.9  883.33  5336.9  882.68
#Mann=3,-1,0
  4581.3    0.05       0  4955.9   0.033       0  4959.9    0.05       0
Bank Sta=4955.9,4959.9
Exp/Cntr=0.3,0.1

Type RM Length L Ch R = 1,30524,446,446,446
BEGIN DESCRIPTION:
Harriet Creek Tributary 5 51.0
END DESCRIPTION:
XS GIS Cut Line= 3
      2298379.00      7080859.96      2298429.00      7080260.00
      2297979.02      7080010.01
#Sta/Elev= 30
  4392.5  884.87  4432.6  883.38  4543.0  881.36  4763.7  879.51  4793.8  876.93
  4811.4  878.66  4816.4  879.95  4844.0  880.58  4864.1  879.43  4894.2  875.18
  4904.2  874.62  4931.8  873.60  4997.4  874.14  5002.5  873.49  5008.3  871.17
  5024.3  872.05  5038.3  870.05  5038.5  869.55  5042.3  870.05  5046.0  871.59
  5051.7  872.52  5105.5  874.94  5127.2  877.96  5154.7  879.23  5235.9  878.91
  5392.6  881.96  5479.6  881.80  5495.6  882.64  5501.3  884.49  5509.3  884.63
#Mann=3,-1,0
  4392.5    0.05       0  5038.3   0.033       0  5042.3    0.05       0
Bank Sta=5038.3,5042.3
Exp/Cntr=0.3,0.1

Type RM Length L Ch R = 1,30078,495,495,495
BEGIN DESCRIPTION:
Harriet Creek Tributary 5 50.0
END DESCRIPTION:
XS GIS Cut Line= 3
      2298779.00      7081359.99      2298729.00      7079960.00
      2298079.00      7079560.00
#Sta/Elev= 30
  3599.1  886.33  3659.1  886.18  3669.1  885.61  3689.2  881.64  3709.2  881.12
  3719.2  881.85  3741.7  885.45  3789.2  885.80  3939.3  884.89  4509.7  877.85
  4619.7  877.72  4679.8  874.90  4799.9  872.07  4862.4  872.33  4899.9  871.37
  5013.6  870.81  5033.2  868.23  5033.5  867.73  5037.2  868.23  5044.4  870.89
  5139.1  873.83  5255.0  876.38  5260.9  875.89  5328.4  878.71  5334.3  878.20
  5529.5  881.66  5660.8  885.29  5682.1  886.56  5712.9  886.54  5763.2  889.10
#Mann=3,-1,0
  3599.1    0.05       0  5033.2   0.033       0  5037.2    0.05       0
Bank Sta=5033.2,5037.2
Exp/Cntr=0.3,0.1

Type RM Length L Ch R = 1,29583,444,444,444
BEGIN DESCRIPTION:
Harriet Creek Tributary 5 49.0
END DESCRIPTION:
XS GIS Cut Line= 3
      2299079.00      7080809.97      2299079.00      7079610.00
      2298578.99      7079360.00
#Sta/Elev= 30
  3800.0  883.57  3840.0  882.24  3950.0  881.70  3980.0  880.27  4020.0  879.49
  4440.0  875.50  4550.0  873.79  4620.0  873.51  4710.0  870.84  4800.0  869.42
  4830.0  868.49  4860.0  868.88  4870.0  868.58  4890.0  869.25  4950.0  867.79
  4980.0  868.52  4997.5  865.84  5006.3  865.33  5006.6  864.83  5010.1  864.83
  5010.4  865.33  5030.7  865.42  5053.1  868.85  5081.0  870.20  5402.5  876.37
  5416.4  877.05  5483.5  877.35  5500.3  877.94  5505.9  879.72  5559.0  880.93
#Mann=3,-1,0
  3800.0    0.05       0  5006.3   0.033       0  5010.4    0.05       0
Bank Sta=5006.3,5010.4
Exp/Cntr=0.3,0.1

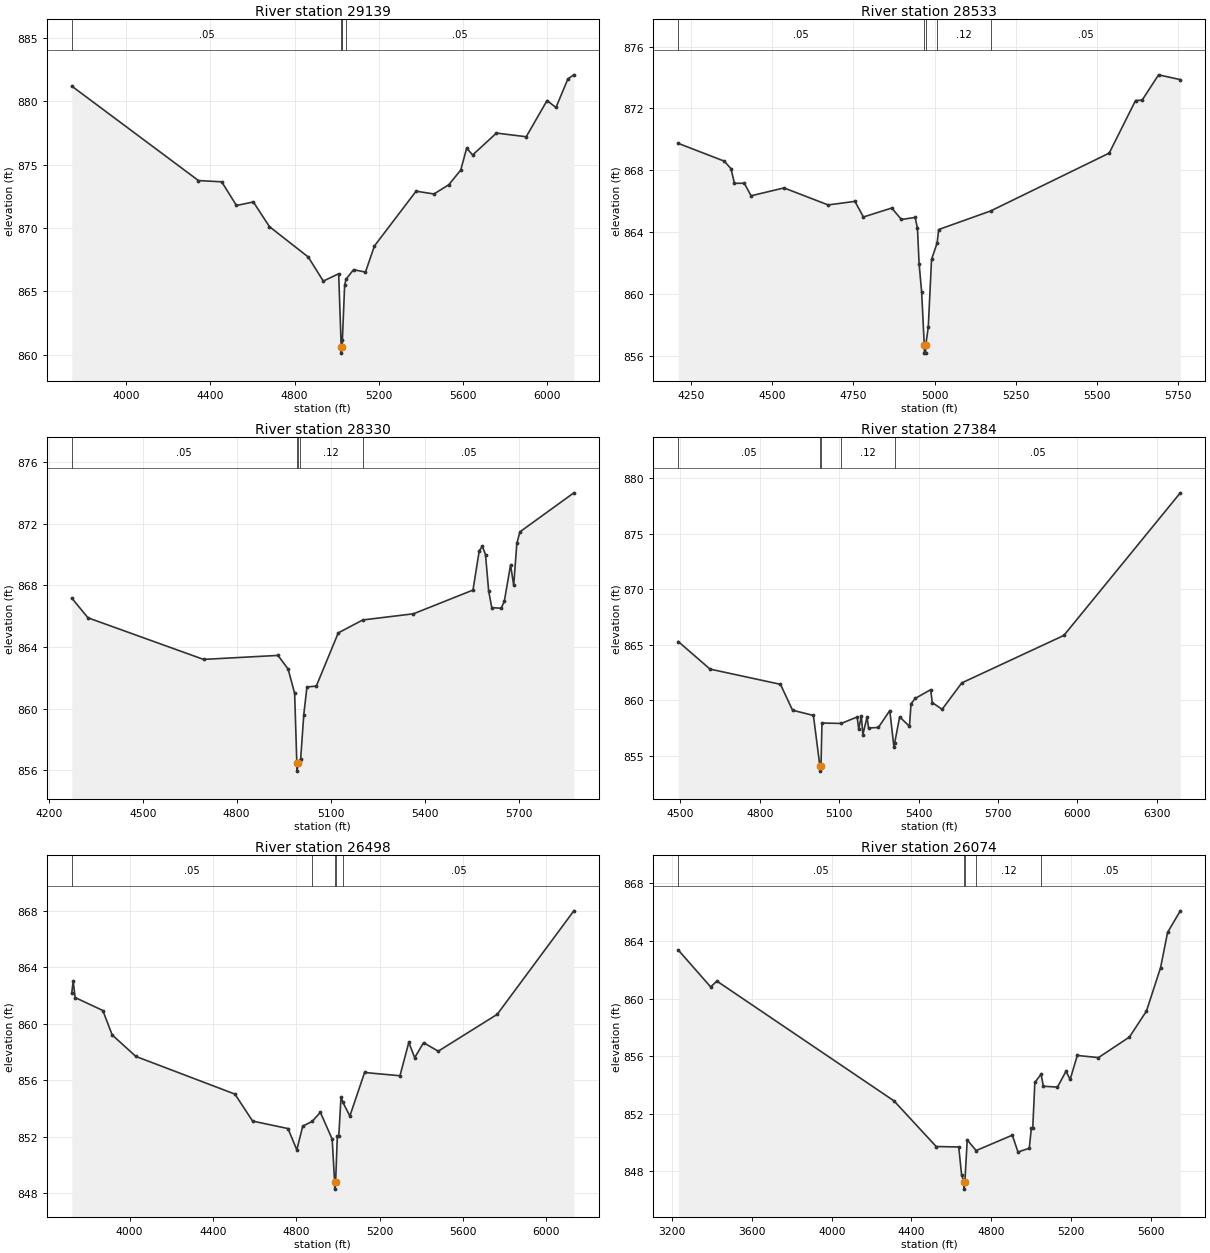
Type RM Length L Ch R = 1,29139,606,606,606
BEGIN DESCRIPTION:
Harriet Creek Tributary 5 48.0
END DESCRIPTION:
XS GIS Cut Line= 3
      2299329.00      7080659.99      2299429.00      7079410.00
      2298628.97      7078609.97
#Sta/Elev= 30
  3741.5  881.21  4343.4  873.75  4453.8  873.65  4524.0  871.78  4604.2  872.06
  4680.7  870.11  4865.1  867.71  4936.5  865.81  5009.6  866.39  5021.6  860.62
  5022.0  860.12  5025.9  860.62  5027.2  861.15  5037.9  865.48  5044.5  865.96
  5080.3  866.71  5136.9  866.52  5179.3  868.58  5377.3  872.91  5462.2  872.69
  5532.9  873.42  5589.5  874.58  5617.7  876.31  5646.0  875.77  5759.2  877.50
  5900.6  877.21  5999.6  880.07  6042.0  879.52  6098.6  881.78  6126.9  882.10
#Mann=5,-1,0
  3741.5    0.05       0  5021.6   0.033       0  5025.9    0.05       0
  5027.2    0.12       0  5044.5    0.05       0
Bank Sta=5021.6,5025.9
Exp/Cntr=0.3,0.1

Type RM Length L Ch R = 1,28533,203,203,203
BEGIN DESCRIPTION:
Harriet Creek Tributary 5 47.0
END DESCRIPTION:
XS GIS Cut Line= 3
      2300646.60      7079266.75      2299952.19      7079088.81
      2299132.90      7078950.09
#Sta/Elev= 30
  4209.7  869.74  4351.7  868.59  4372.4  868.10  4382.9  867.16  4413.4  867.16
  4434.3  866.35  4535.7  866.86  4671.8  865.76  4754.4  865.99  4780.5  864.98
  4867.9  865.56  4897.7  864.82  4939.9  864.95  4947.2  864.26  4952.2  861.97
  4960.2  860.10  4968.2  856.68  4968.6  856.18  4972.2  856.18  4972.6  856.68
  4980.5  857.86  4990.6  862.24  5007.7  863.29  5012.6  864.17  5172.8  865.37
  5538.3  869.11  5619.5  872.51  5639.7  872.53  5690.5  874.17  5757.5  873.86
#Mann=5,-1,0
  4209.7    0.05       0  4968.2   0.033       0  4972.6    0.05       0
  5007.7    0.12       0  5172.8    0.05       0
Bank Sta=4968.2,4972.6
Exp/Cntr=0.3,0.1

Type RM Length L Ch R = 1,28330,946,946,946
BEGIN DESCRIPTION:
Harriet Creek Tributary 5 46.0
END DESCRIPTION:
XS GIS Cut Line= 3
      2300707.35      7078969.10      2300002.49      7078911.21
      2299107.02      7078897.59
#Sta/Elev= 30
  4273.6  867.18  4325.4  865.90  4694.3  863.20  4931.9  863.46  4964.3  862.57
  4985.1  861.00  4992.1  856.45  4992.5  855.95  4996.6  856.45  5001.0  856.62
  5004.3  856.74  5014.3  859.62  5024.3  861.41  5054.3  861.47  5124.3  864.92
  5202.6  865.76  5364.4  866.16  5554.4  867.70  5574.4  870.25  5584.4  870.54
  5594.4  870.00  5604.4  867.65  5614.4  866.56  5644.4  866.52  5654.4  866.97
  5674.4  869.33  5684.4  868.01  5694.4  870.73  5704.4  871.48  5876.4  874.01
#Mann=5,-1,0
  4273.6    0.05       0  4992.1   0.033       0  4996.6    0.05       0
  5001.0    0.12       0  5202.6    0.05       0
Bank Sta=4992.1,4996.6
Exp/Cntr=0.3,0.1

Type RM Length L Ch R = 1,27384,886,886,886
BEGIN DESCRIPTION:
Harriet Creek Tributary 5 45.0
END DESCRIPTION:
XS GIS Cut Line= 3
      2300829.89      7078907.80      2300729.00      7078410.00
      2299528.97      7077709.98
#Sta/Elev= 30
  4492.1  865.28  4612.3  862.80  4878.4  861.43  4924.0  859.10  5002.9  858.63
  5027.1  854.12  5027.6  853.62  5031.6  854.12  5035.2  857.95  5107.9  857.91
  5168.3  858.49  5174.1  857.39  5184.0  858.60  5189.8  856.91  5205.5  858.48
  5211.3  857.50  5248.5  857.55  5291.5  859.07  5307.2  855.78  5310.2  856.18
  5328.7  858.50  5365.9  857.65  5371.7  859.68  5387.4  860.16  5446.2  860.95
  5451.9  859.79  5489.2  859.18  5563.6  861.56  5949.3  865.83  6389.3  878.66
#Mann=5,-1,0
  4492.1    0.05       0  5027.1   0.033       0  5031.6    0.05       0
  5107.9    0.12       0  5310.2    0.05       0
Bank Sta=5027.1,5031.6
Exp/Cntr=0.3,0.1

Type RM Length L Ch R = 1,26498,424,424,424
BEGIN DESCRIPTION:
Harriet Creek Tributary 5 44.0
END DESCRIPTION:
XS GIS Cut Line= 4
      2300962.69      7078754.58      2301272.89      7078103.89
      2300879.00      7077710.00      2300078.97      7076909.97
#Sta/Elev= 30
  3722.1  862.19  3728.9  863.04  3738.2  861.87  3871.2  860.95  3916.0  859.22
  4029.5  857.70  4505.0  855.03  4589.9  853.12  4759.6  852.59  4802.0  851.08
  4830.3  852.76  4875.3  853.09  4915.1  853.74  4971.7  851.84  4983.5  848.80
  4984.0  848.30  4988.2  848.80  4996.5  852.06  5003.5  852.06  5014.1  854.83
  5023.4  854.44  5056.6  853.48  5127.3  856.56  5297.0  856.33  5339.4  858.69
  5367.7  857.61  5410.1  858.67  5480.8  858.07  5763.7  860.68  6131.4  868.01
#Mann=5,-1,0
  3722.1    0.05       0  4875.3    0.12       0  4983.5    0.07       0
  4988.2    0.12       0  5023.4    0.05       0
Bank Sta=4983.5,4988.2
Exp/Cntr=0.3,0.1

Type RM Length L Ch R = 1,26074,957,957,957
BEGIN DESCRIPTION:
Harriet Creek Tributary 5 43.0
END DESCRIPTION:
XS GIS Cut Line= 4
      2301020.58      7078911.18      2301442.33      7077723.33
      2301079.00      7077360.00      2300529.02      7076860.02
#Sta/Elev= 30
  3230.4  863.38  3393.1  860.81  3424.0  861.22  4312.6  852.89  4523.9  849.72
  4637.0  849.69  4651.2  847.76  4663.0  847.26  4663.5  846.76  4667.7  847.26
  4679.5  850.18  4724.1  849.44  4905.7  850.51  4934.0  849.34  4990.6  849.60
  5001.2  851.01  5008.1  851.01  5018.6  854.17  5049.8  854.75  5061.2  853.91
  5132.1  853.85  5174.7  854.95  5195.6  854.38  5231.4  856.05  5337.5  855.90
  5492.9  857.33  5578.1  859.13  5649.0  862.15  5684.2  864.60  5748.0  866.10
#Mann=5,-1,0
  3230.4    0.05       0  4663.0    0.07       0  4667.7    0.05       0
  4724.1    0.12       0  5049.8    0.05       0
Bank Sta=4663,4667.7
Exp/Cntr=0.3,0.1

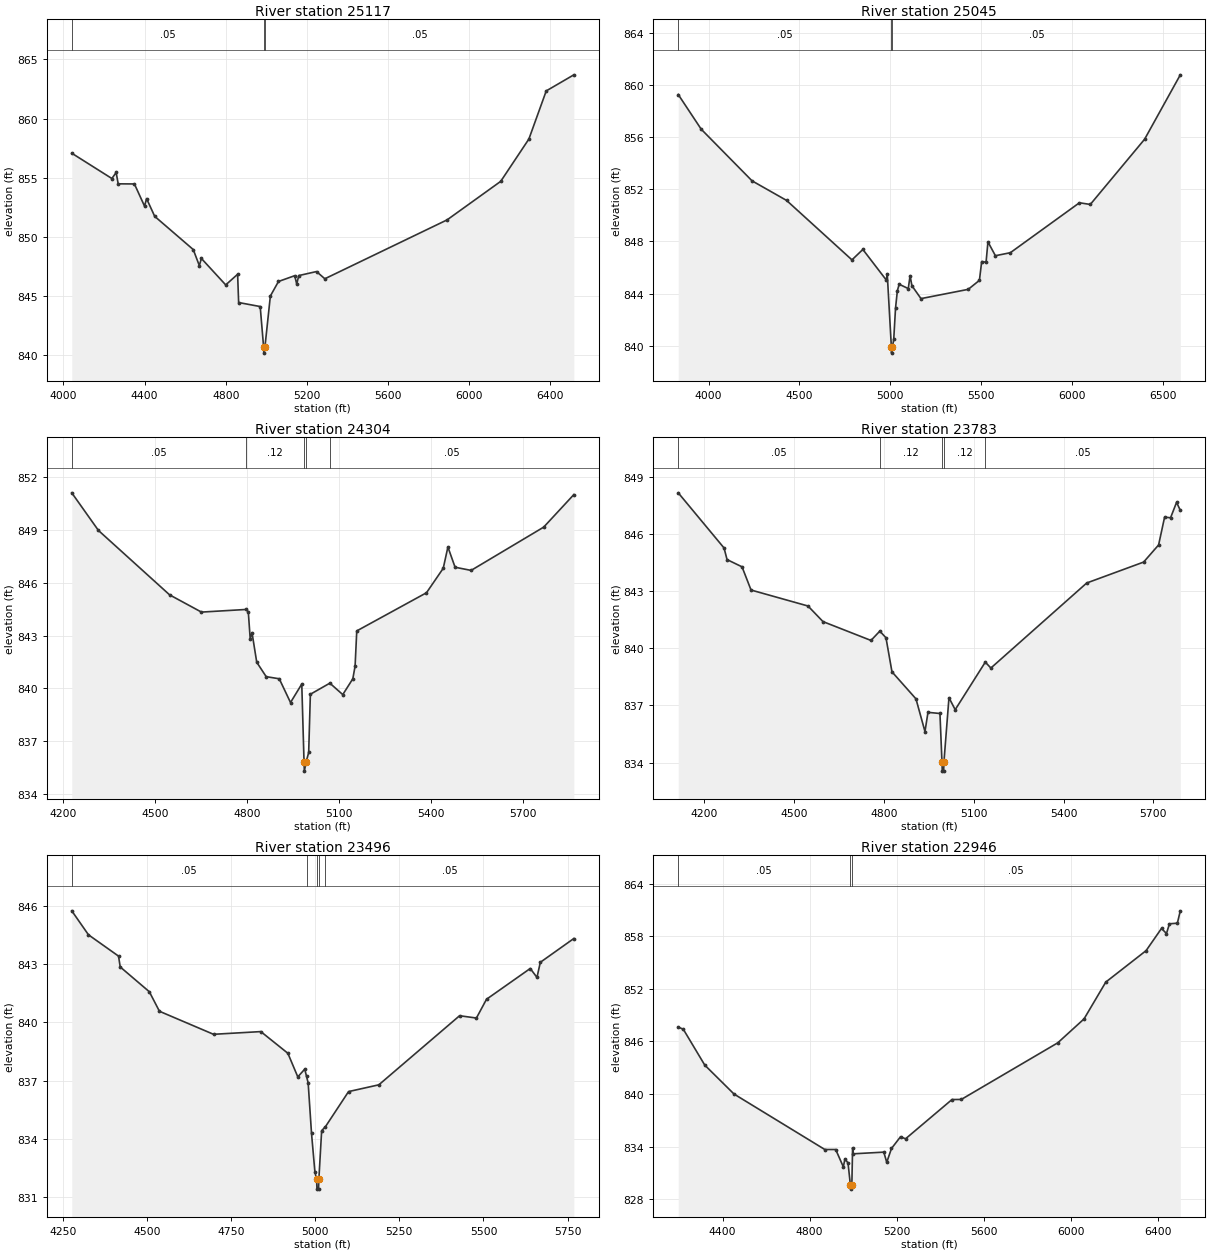
Type RM Length L Ch R = 1,25117,72,72,72
BEGIN DESCRIPTION:
Harriet Creek Tributary 5 42.0
END DESCRIPTION:
XS GIS Cut Line= 4
      2301939.91      7078318.76      2301950.13      7077814.81
      2301936.51      7077109.99      2300751.59      7076663.94
#Sta/Elev= 30
  4041.2  857.07  4238.9  854.93  4260.0  855.44  4270.0  854.48  4350.0  854.47
  4400.0  852.59  4410.0  853.23  4450.0  851.73  4640.1  848.92  4670.1  847.56
  4680.1  848.17  4800.1  845.93  4858.8  846.83  4863.8  844.44  4970.1  844.10
  4987.0  840.66  4988.0  840.16  4993.3  840.66  5020.2  844.99  5060.2  846.22
  5140.2  846.71  5150.2  846.00  5160.2  846.72  5247.7  847.06  5288.8  846.45
  5891.4  851.43  6155.8  854.69  6294.7  858.27  6380.2  862.34  6516.3  863.70
#Mann=3,-1,0
  4041.2    0.05       0  4987.0   0.033       0  4993.3    0.05       0
Bank Sta=4987,4993.3
Exp/Cntr=0.3,0.1

Type RM Length L Ch R = 1,25045,741,741,741
BEGIN DESCRIPTION:
Harriet Creek Tributary 5 41.0
END DESCRIPTION:
XS GIS Cut Line= 3
      2302035.25      7078526.43      2302004.61      7076868.23
      2300928.96      7076609.99
#Sta/Elev= 30
  3833.0  859.26  3959.5  856.60  4239.5  852.64  4429.5  851.14  4789.6  846.58
  4849.6  847.38  4978.9  845.03  4983.9  845.52  5006.5  839.93  5007.5  839.43
  5012.8  839.93  5019.6  840.48  5029.6  842.89  5039.6  844.21  5049.6  844.71
  5099.7  844.38  5109.7  845.37  5119.7  844.60  5169.7  843.61  5429.7  844.32
  5491.5  845.01  5503.9  846.45  5528.1  846.40  5538.4  847.96  5579.5  846.90
  5661.8  847.13  6042.3  850.96  6102.0  850.83  6401.0  855.83  6597.7  860.77
#Mann=3,-1,0
  3833.0    0.05       0  5006.5   0.033       0  5012.8    0.05       0
Bank Sta=5006.5,5012.8
Exp/Cntr=0.3,0.1

Type RM Length L Ch R = 1,24304,521,521,521
BEGIN DESCRIPTION:
Harriet Creek Tributary 5 40.0
END DESCRIPTION:
XS GIS Cut Line= 3
      2302779.02      7077410.03      2302379.00      7076760.00
      2301578.97      7076409.99
#Sta/Elev= 30
  4229.6  851.12  4316.6  848.98  4548.5  845.32  4652.3  844.34  4797.9  844.49
  4805.0  844.35  4811.2  842.82  4817.1  843.17  4832.5  841.49  4863.3  840.67
  4905.9  840.55  4942.6  839.20  4979.3  840.25  4986.7  835.80  4987.7  835.30
  4993.2  835.80  5001.8  836.36  5007.3  839.67  5070.8  840.30  5112.9  839.65
  5145.7  840.55  5153.1  841.27  5158.5  843.27  5385.8  845.44  5440.4  846.83
  5455.6  848.04  5479.0  846.89  5531.2  846.71  5767.8  849.17  5866.1  851.02
#Mann=5,-1,0
  4229.6    0.05       0  4797.9    0.12       0  4986.7    0.07       0
  4993.2    0.12       0  5070.8    0.05       0
Bank Sta=4986.7,4993.2
Exp/Cntr=0.3,0.1

Type RM Length L Ch R = 1,23783,287,287,287
BEGIN DESCRIPTION:
Harriet Creek Tributary 5 39.0
END DESCRIPTION:
XS GIS Cut Line= 3
      2303611.75      7076449.42      2302692.41      7076401.75
      2301936.52      7076394.94
#Sta/Elev= 30
  4113.4  848.18  4266.4  845.28  4276.4  844.67  4326.4  844.29  4356.5  843.07
  4546.7  842.23  4596.8  841.41  4757.0  840.42  4786.5  840.91  4807.1  840.56
  4827.1  838.77  4907.2  837.35  4937.3  835.63  4947.3  836.64  4987.3  836.58
  4994.0  834.05  4995.1  833.55  4999.6  833.55  5000.7  834.05  5017.4  837.41
  5038.2  836.78  5138.7  839.28  5157.4  838.97  5477.4  843.44  5667.4  844.54
  5717.4  845.44  5737.4  846.90  5757.4  846.87  5777.4  847.68  5789.9  847.26
#Mann=5,-1,0
  4113.4    0.05       0  4786.5    0.12       0  4994.0    0.07       0
  5000.7    0.12       0  5138.7    0.05       0
Bank Sta=4994,5000.7
Exp/Cntr=0.3,0.1

Type RM Length L Ch R = 1,23496,550,550,550
BEGIN DESCRIPTION:
Harriet Creek Tributary 5 38.0
END DESCRIPTION:
XS GIS Cut Line= 3
      2303648.46      7076318.40      2302917.17      7076249.53
      2302159.44      7076241.15
#Sta/Elev= 30
  4276.3  845.77  4326.0  844.53  4415.3  843.43  4420.3  842.87  4506.8  841.59
  4536.9  840.58  4697.6  839.39  4838.2  839.53  4918.6  838.41  4948.1  837.19
  4968.8  837.59  4974.0  837.22  4978.9  836.88  4988.9  834.27  4998.9  832.29
  5004.0  831.89  5005.1  831.39  5009.7  831.39  5010.7  831.89  5019.0  834.41
  5030.4  834.62  5099.0  836.43  5189.0  836.78  5429.0  840.35  5479.0  840.23
  5509.0  841.20  5639.0  842.79  5659.0  842.33  5669.0  843.11  5768.6  844.34
#Mann=5,-1,0
  4276.3    0.05       0  4974.0    0.12       0  5004.0    0.07       0
  5010.7    0.12       0  5030.4    0.05       0
Bank Sta=5004,5010.7
Exp/Cntr=0.3,0.1

Type RM Length L Ch R = 1,22946,468,468,468
BEGIN DESCRIPTION:
Harriet Creek Tributary 5 37.0
END DESCRIPTION:
XS GIS Cut Line= 3
      2303727.53      7076354.09      2303129.00      7075810.00
      2301928.98      7074909.98
#Sta/Elev= 30
  4195.6  847.63  4218.9  847.38  4317.6  843.29  4452.1  839.99  4869.7  833.66
  4919.7  833.66  4954.8  831.68  4962.2  832.58  4976.4  832.13  4987.2  829.64
  4988.3  829.14  4994.0  829.64  4997.4  833.86  5001.1  833.17  5140.9  833.36
  5154.5  832.20  5176.3  833.78  5218.0  835.12  5240.9  834.88  5454.5  839.36
  5497.2  839.37  5940.9  845.83  6061.8  848.56  6161.8  852.76  6347.2  856.35
  6418.0  858.88  6440.9  858.30  6454.5  859.41  6490.9  859.48  6504.5  860.89
#Mann=3,-1,0
  4195.6    0.05       0  4987.2   0.033       0  4994.0    0.05       0
Bank Sta=4987.2,4994
Exp/Cntr=0.3,0.1

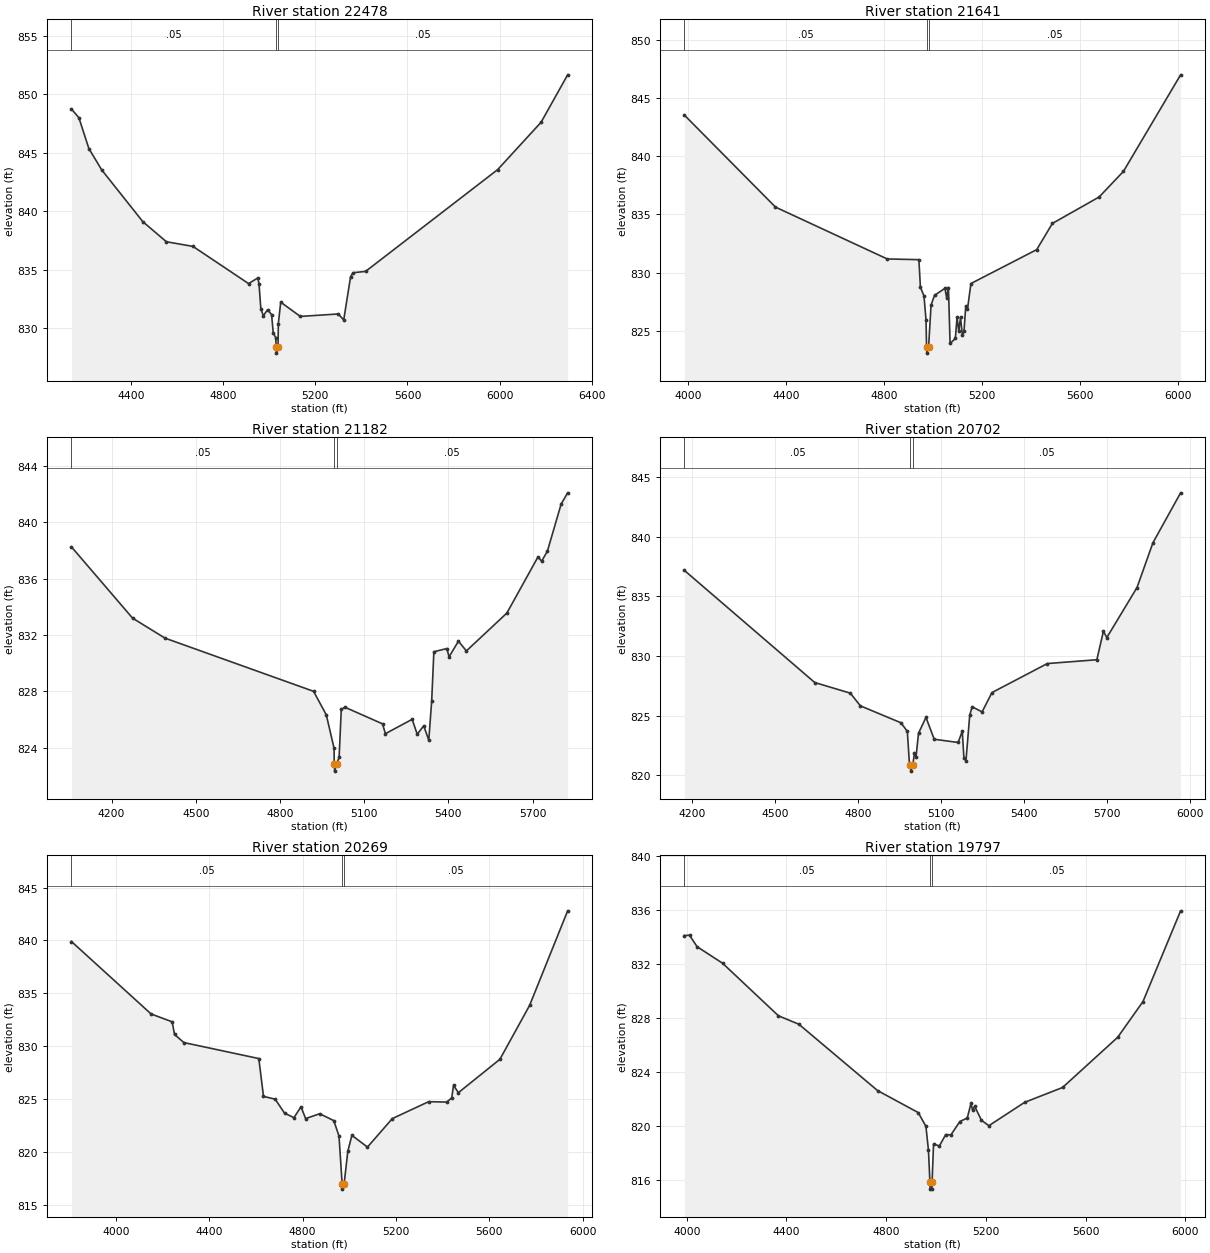
Type RM Length L Ch R = 1,22478,837,837,837
BEGIN DESCRIPTION:
Harriet Creek Tributary 5 36.0
END DESCRIPTION:
XS GIS Cut Line= 3
      2303778.99      7076359.98      2303479.00      7075560.00
      2302278.98      7075059.99
#Sta/Elev= 30
  4141.2  848.74  4173.2  848.01  4216.8  845.36  4272.0  843.55  4450.9  839.11
  4553.2  837.39  4668.9  836.99  4910.1  833.81  4950.2  834.29  4955.5  833.78
  4963.5  831.65  4974.2  831.06  4992.9  831.58  5010.2  831.15  5017.2  829.60
  5028.1  829.18  5030.1  828.36  5031.3  827.86  5038.0  828.36  5039.5  830.39
  5049.7  832.22  5134.8  831.00  5299.5  831.21  5323.3  830.70  5353.1  834.40
  5363.9  834.74  5418.1  834.85  5991.7  843.56  6180.2  847.61  6295.6  851.67
#Mann=3,-1,0
  4141.2    0.05       0  5030.1    0.04       0  5038.0    0.05       0
Bank Sta=5030.1,5038
Exp/Cntr=0.3,0.1

Type RM Length L Ch R = 1,21641,459,459,459
BEGIN DESCRIPTION:
Harriet Creek Tributary 5 35.0
END DESCRIPTION:
XS GIS Cut Line= 3
      2304328.98      7075959.97      2303729.00      7075160.00
      2303028.98      7074409.98
#Sta/Elev= 30
  3984.0  843.51  4355.8  835.62  4812.1  831.17  4941.3  831.11  4947.5  828.75
  4962.1  827.99  4970.4  825.94  4972.6  823.59  4973.8  823.09  4980.8  823.59
  4991.0  827.21  5005.2  828.05  5047.7  828.65  5054.6  827.85  5061.9  828.72
  5068.7  823.92  5090.2  824.35  5097.1  826.17  5104.4  824.96  5111.2  826.17
  5118.6  824.66  5125.4  824.95  5132.7  827.15  5139.6  826.84  5153.7  829.06
  5422.4  831.97  5486.4  834.22  5677.4  836.49  5776.6  838.69  6009.9  846.97
#Mann=3,-1,0
  3984.0    0.05       0  4972.6    0.04       0  4980.8    0.05       0
Bank Sta=4972.6,4980.8
Exp/Cntr=0.3,0.1

Type RM Length L Ch R = 1,21182,480,480,480
BEGIN DESCRIPTION:
Harriet Creek Tributary 5 34.0
END DESCRIPTION:
XS GIS Cut Line= 3
      2304479.00      7075659.99      2303979.00      7074860.00
      2303779.00      7074060.01
#Sta/Elev= 30
  4057.0  838.26  4274.6  833.20  4390.1  831.78  4919.6  828.00  4965.0  826.33
  4992.7  823.95  4993.3  822.83  4994.6  822.33  5001.5  822.83  5010.7  823.31
  5018.4  826.72  5031.3  826.87  5165.3  825.69  5175.6  824.99  5271.0  826.01
  5289.0  824.95  5312.2  825.55  5330.2  824.53  5340.5  827.30  5348.3  830.81
  5394.7  831.04  5402.4  830.45  5435.9  831.56  5464.2  830.87  5608.5  833.56
  5719.4  837.55  5732.2  837.24  5752.9  837.96  5801.8  841.30  5825.0  842.10
#Mann=3,-1,0
  4057.0    0.05       0  4993.3   0.033       0  5001.5    0.05       0
Bank Sta=4993.3,5001.5
Exp/Cntr=0.3,0.1

Type RM Length L Ch R = 1,20702,433,433,433
BEGIN DESCRIPTION:
Harriet Creek Tributary 5 33.0
END DESCRIPTION:
XS GIS Cut Line= 3
      2304629.00      7075560.00      2304429.00      7074760.00
      2303879.02      7073960.04
#Sta/Elev= 30
  4171.4  837.17  4643.0  827.78  4771.8  826.89  4807.9  825.83  4954.8  824.41
  4978.0  823.69  4985.7  820.92  4989.2  820.86  4990.4  820.36  4997.7  820.86
  5003.5  821.86  5009.5  821.57  5018.4  823.53  5045.4  824.86  5075.2  823.03
  5161.8  822.76  5176.7  823.70  5182.7  821.47  5190.2  821.25  5203.7  825.04
  5212.5  825.75  5248.4  825.32  5284.2  826.94  5484.5  829.37  5663.7  829.69
  5687.5  832.08  5699.9  831.55  5809.1  835.74  5866.7  839.49  5966.8  843.67
#Mann=3,-1,0
  4171.4    0.05       0  4989.2   0.033       0  4997.7    0.05       0
Bank Sta=4989.2,4997.7
Exp/Cntr=0.3,0.1

Type RM Length L Ch R = 1,20269,472,472,472
BEGIN DESCRIPTION:
Harriet Creek Tributary 5 32.0
END DESCRIPTION:
XS GIS Cut Line= 3
      2304829.00      7075659.98      2304729.00      7074460.00
      2304028.99      7073859.99
#Sta/Elev= 30
  3809.5  839.90  4150.7  833.06  4241.0  832.32  4251.0  831.13  4291.1  830.36
  4612.2  828.85  4632.3  825.28  4682.5  825.01  4722.6  823.69  4762.8  823.27
  4792.9  824.29  4812.9  823.18  4873.1  823.64  4933.4  822.99  4955.9  821.53
  4969.2  817.02  4970.5  816.52  4977.8  817.02  4993.6  820.09  5011.1  821.60
  5077.8  820.49  5184.3  823.18  5340.2  824.78  5418.1  824.74  5438.9  825.15
  5446.6  826.31  5467.5  825.63  5645.3  828.78  5772.6  833.87  5935.6  842.80
#Mann=3,-1,0
  3809.5    0.05       0  4969.2   0.033       0  4977.8    0.05       0
Bank Sta=4969.2,4977.8
Exp/Cntr=0.3,0.1

Type RM Length L Ch R = 1,19797,472,472,472
BEGIN DESCRIPTION:
Harriet Creek Tributary 5 31.0
END DESCRIPTION:
XS GIS Cut Line= 3
      2305278.99      7075259.96      2305079.00      7074260.00
      2304278.99      7073709.99
#Sta/Elev= 30
  3990.9  834.08  4011.3  834.10  4041.8  833.25  4143.8  832.03  4368.2  828.13
  4449.8  827.51  4765.9  822.59  4929.1  820.96  4959.7  819.94  4969.9  818.18
  4975.8  815.79  4977.0  815.29  4983.1  815.29  4984.4  815.79  4990.3  818.63
  5013.7  818.49  5039.1  819.33  5060.0  819.31  5095.9  820.30  5125.7  820.56
  5140.6  821.65  5146.6  821.17  5155.5  821.42  5182.5  820.39  5212.3  819.99
  5355.7  821.72  5507.9  822.82  5729.1  826.54  5830.6  829.19  5981.5  835.91
#Mann=3,-1,0
  3990.9    0.05       0  4975.8   0.033       0  4984.4    0.05       0
Bank Sta=4975.8,4984.4
Exp/Cntr=0.3,0.1