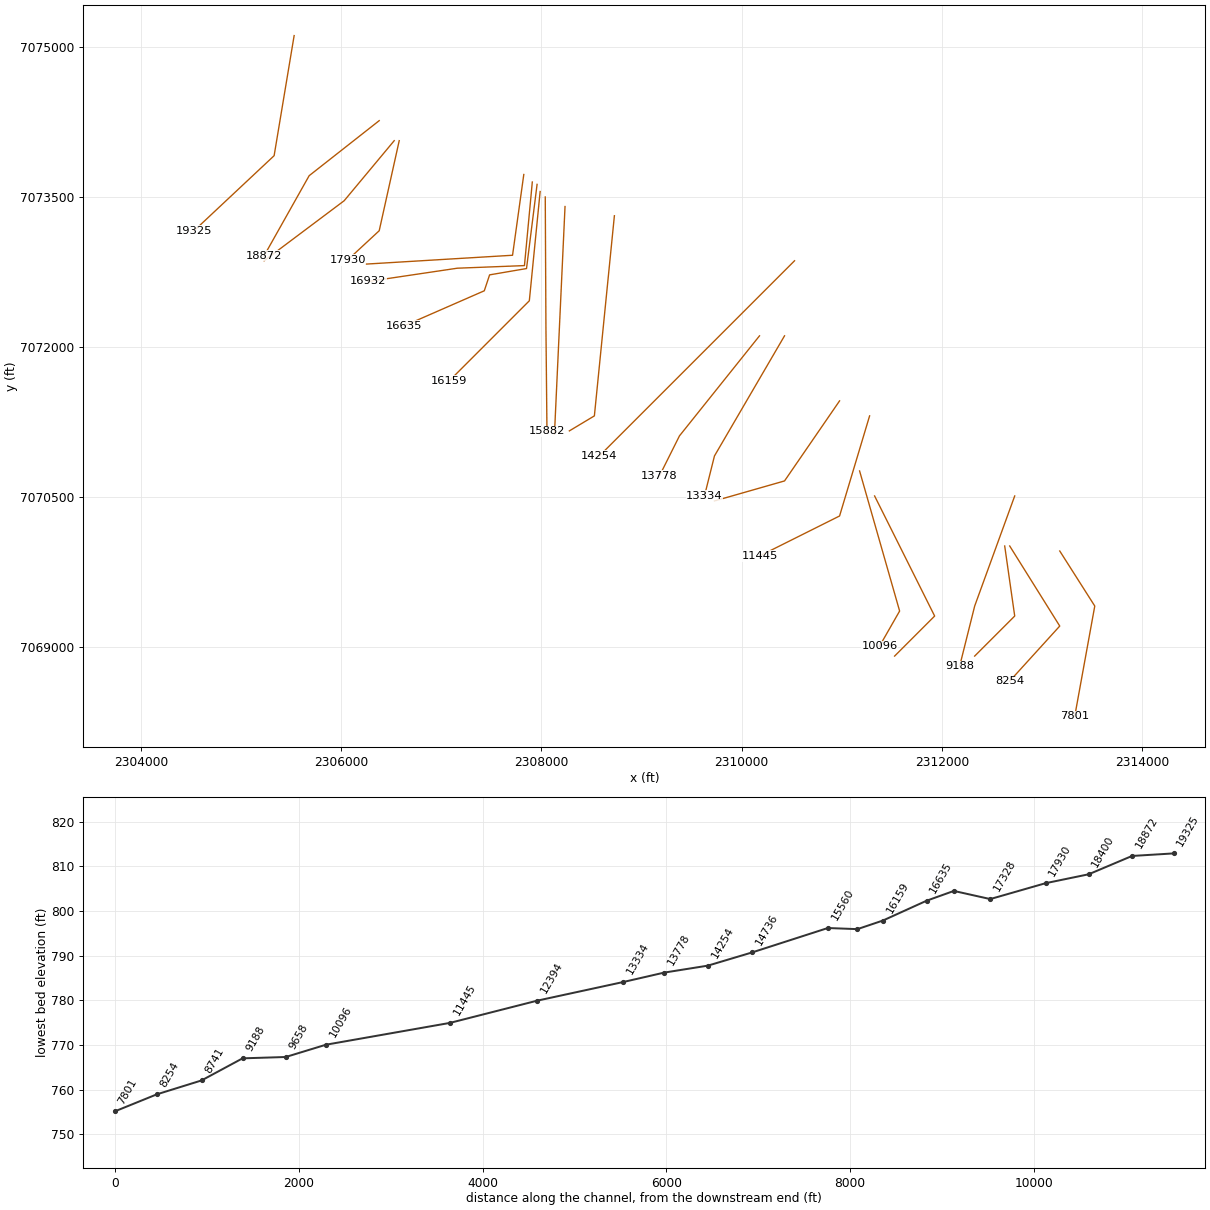
HEC-RAS study Harriet Creek Tributary 5.prj: Harriet Creek Tributary 5 Base Level Engineering

--- Harriet Creek Tributary 5.g01 (geometry) --- (continued)

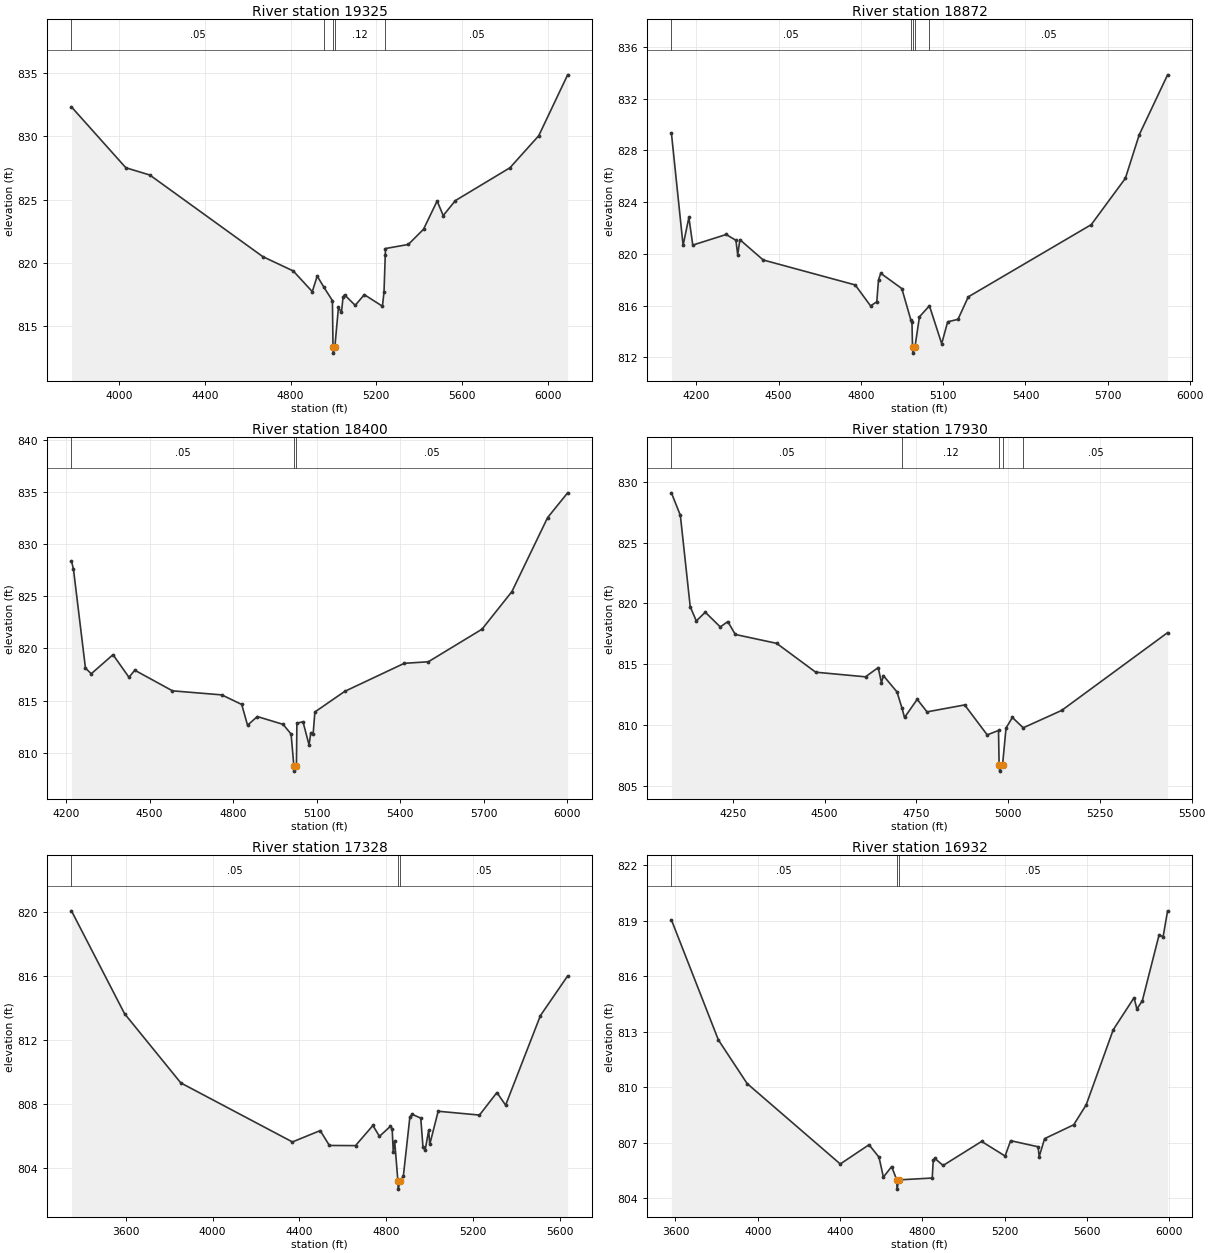
Type RM Length L Ch R = 1,19325,453,453,453
BEGIN DESCRIPTION:
Harriet Creek Tributary 5 30.0
END DESCRIPTION:
XS GIS Cut Line= 3
      2305529.00      7075110.02      2305329.00      7073910.00
      2304528.97      7073159.97
#Sta/Elev= 30
  3778.7  832.31  4032.2  827.51  4143.7  826.94  4670.9  820.50  4812.8  819.37
  4901.5  817.74  4924.3  818.97  4956.3  818.07  4995.3  817.03  4998.0  813.39
  4999.3  812.89  5006.7  813.39  5023.4  816.50  5037.5  816.10  5044.8  817.30
  5051.7  817.49  5101.5  816.66  5144.0  817.50  5228.5  816.59  5235.8  817.71
  5241.7  820.64  5242.7  821.14  5349.1  821.46  5420.0  822.66  5483.5  824.89
  5511.8  823.74  5568.5  824.92  5823.0  827.51  5957.3  830.04  6091.9  834.84
#Mann=5,-1,0
  3778.7    0.05       0  4956.3    0.12       0  4998.0    0.07       0
  5006.7    0.12       0  5241.7    0.05       0
Bank Sta=4998,5006.7
Exp/Cntr=0.3,0.1

Type RM Length L Ch R = 1,18872,472,472,472
BEGIN DESCRIPTION:
Harriet Creek Tributary 5 29.0
END DESCRIPTION:
XS GIS Cut Line= 3
      2306379.00      7074260.00      2305679.00      7073710.00
      2305229.00      7072910.01
#Sta/Elev= 30
  4109.8  829.31  4152.3  820.65  4173.4  822.81  4187.6  820.67  4309.5  821.49
  4344.8  821.04  4351.4  819.92  4359.2  821.09  4444.2  819.52  4779.5  817.59
  4835.6  815.97  4858.1  816.29  4864.5  817.99  4872.6  818.49  4949.4  817.31
  4982.1  814.90  4986.4  814.70  4988.3  812.82  4989.6  812.32  4997.4  812.82
  5013.7  815.13  5050.0  815.98  5094.7  813.05  5116.4  814.74  5154.0  814.93
  5191.6  816.67  5639.7  822.25  5764.0  825.83  5814.6  829.20  5917.9  833.83
#Mann=5,-1,0
  4109.8    0.05       0  4982.1    0.12       0  4988.3    0.07       0
  4997.4    0.12       0  5050.0    0.05       0
Bank Sta=4988.3,4997.4
Exp/Cntr=0.3,0.1

Type RM Length L Ch R = 1,18400,470,470,470
BEGIN DESCRIPTION:
Harriet Creek Tributary 5 28.0
END DESCRIPTION:
XS GIS Cut Line= 3
      2306529.03      7074060.03      2306029.00      7073460.00
      2305228.98      7072859.98
#Sta/Elev= 30
  4219.4  828.39  4226.6  827.60  4269.6  818.11  4290.4  817.57  4368.5  819.40
  4425.8  817.23  4446.6  817.91  4582.0  815.93  4759.0  815.54  4830.6  814.62
  4851.4  812.63  4886.6  813.46  4979.0  812.71  5007.8  811.78  5017.7  808.72
  5019.0  808.22  5026.9  808.72  5028.6  812.82  5050.5  812.96  5072.3  810.73
  5078.6  811.92  5086.9  811.79  5093.2  813.90  5200.5  815.88  5414.0  818.57
  5500.5  818.72  5693.2  821.85  5800.5  825.46  5928.6  832.56  6000.5  834.94
#Mann=3,-1,0
  4219.4    0.05       0  5017.7   0.033       0  5026.9    0.05       0
Bank Sta=5017.7,5026.9
Exp/Cntr=0.3,0.1

Type RM Length L Ch R = 1,17930,602,602,602
BEGIN DESCRIPTION:
Harriet Creek Tributary 5 27.0
END DESCRIPTION:
XS GIS Cut Line= 3
      2306578.99      7074059.96      2306379.00      7073160.00
      2306063.64      7072867.70
#Sta/Elev= 30
  4082.5  829.09  4106.8  827.24  4133.7  819.73  4150.3  818.56  4174.7  819.28
  4215.6  818.07  4236.1  818.51  4256.6  817.45  4369.3  816.72  4475.6  814.35
  4611.3  813.97  4645.9  814.73  4654.8  813.48  4660.0  814.07  4697.1  812.73
  4710.7  811.40  4717.6  810.63  4752.2  812.12  4779.0  811.09  4881.5  811.66
  4942.9  809.20  4973.7  809.56  4975.4  806.72  4976.8  806.22  4984.7  806.72
  4994.2  809.76  5011.5  810.63  5041.0  809.78  5145.9  811.21  5434.4  817.60
#Mann=5,-1,0
  4082.5    0.05       0  4710.7    0.12       0  4975.4    0.07       0
  4984.7    0.12       0  5041.0    0.05       0
Bank Sta=4975.4,4984.7
Exp/Cntr=0.3,0.1

Type RM Length L Ch R = 1,17328,396,396,396
BEGIN DESCRIPTION:
Harriet Creek Tributary 5 26.0
END DESCRIPTION:
XS GIS Cut Line= 3
      2307823.69      7073722.07      2307711.33      7072915.07
      2306243.88      7072826.55
#Sta/Elev= 30
  3350.3  820.07  3594.7  813.64  3853.9  809.31  4367.8  805.62  4495.7  806.33
  4538.1  805.40  4658.3  805.39  4738.5  806.65  4768.5  805.97  4818.6  806.59
  4827.1  806.46  4832.1  805.02  4838.6  805.69  4853.6  803.17  4855.0  802.67
  4863.8  803.17  4878.7  803.49  4908.8  807.19  4918.8  807.35  4958.9  807.11
  4968.9  805.32  4978.9  805.10  4995.3  806.35  5000.3  805.47  5039.0  807.54
  5229.3  807.30  5309.5  808.71  5349.6  807.92  5509.9  813.52  5635.2  816.00
#Mann=3,-1,0
  3350.3    0.05       0  4853.6   0.033       0  4863.8    0.05       0
Bank Sta=4853.6,4863.8
Exp/Cntr=0.3,0.1

Type RM Length L Ch R = 1,16932,297,297,297
BEGIN DESCRIPTION:
Harriet Creek Tributary 5 25.0
END DESCRIPTION:
XS GIS Cut Line= 4
      2307908.82      7073647.16      2307830.28      7072811.72
      2307159.72      7072785.68      2306267.63      7072652.89
#Sta/Elev= 30
  3580.5  819.05  3808.7  812.56  3948.4  810.20  4401.3  805.85  4541.0  806.89
  4589.5  806.22  4611.0  805.14  4651.1  805.71  4675.9  804.99  4677.3  804.49
  4686.3  804.99  4848.4  805.09  4853.4  806.06  4861.2  806.15  4901.3  805.77
  5088.5  807.07  5202.6  806.28  5229.5  807.11  5363.2  806.78  5368.2  806.24
  5394.7  807.22  5536.3  807.97  5596.9  809.05  5728.4  813.11  5829.5  814.84
  5843.5  814.23  5869.9  814.68  5950.8  818.22  5971.0  818.15  5992.6  819.54
#Mann=3,-1,0
  3580.5    0.05       0  4675.9   0.033       0  4686.3    0.05       0
Bank Sta=4675.9,4686.3
Exp/Cntr=0.3,0.1

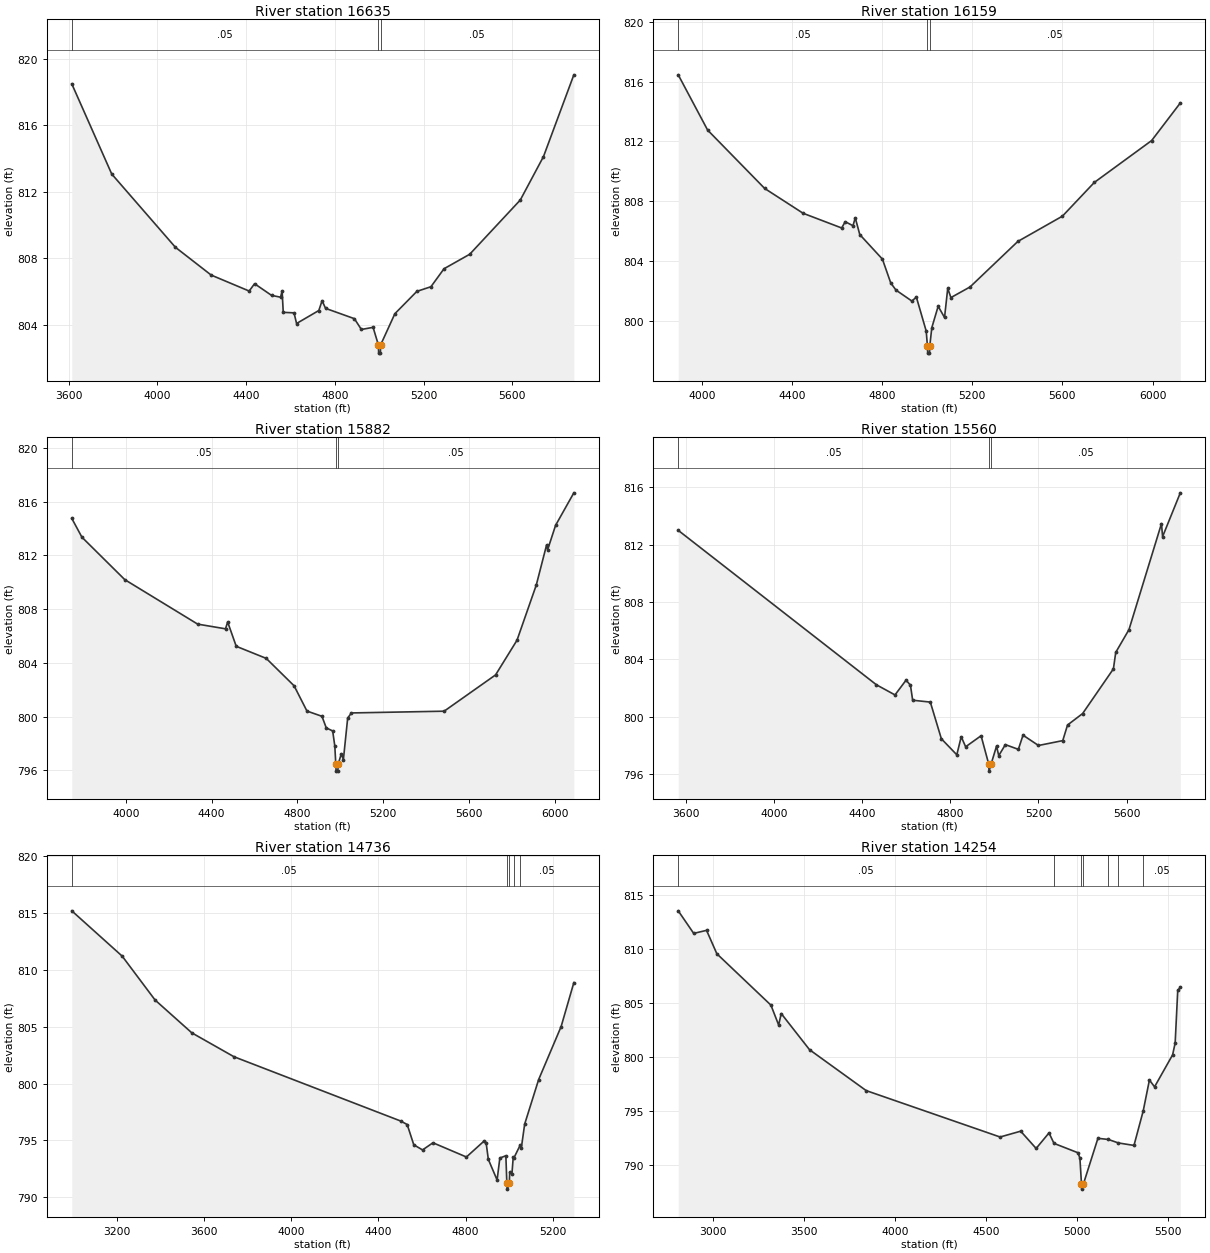
Type RM Length L Ch R = 1,16635,476,476,476
BEGIN DESCRIPTION:
Harriet Creek Tributary 5 24.0
END DESCRIPTION:
XS GIS Cut Line= 5
      2307956.49      7073623.32      2307850.93      7072782.28
      2307482.03      7072719.10      2307429.00      7072560.00
      2306629.03      7072210.01
#Sta/Elev= 30
  3614.5  818.48  3794.6  813.06  4081.5  808.66  4242.7  806.99  4414.0  806.03
  4438.4  806.47  4514.8  805.77  4555.4  805.66  4562.5  806.03  4567.6  804.75
  4616.3  804.72  4627.6  804.08  4727.9  804.86  4742.7  805.45  4758.3  804.99
  4888.2  804.37  4919.8  803.72  4972.5  803.85  4996.2  802.80  4997.7  802.30
  5005.3  802.30  5006.7  802.80  5070.8  804.67  5169.8  806.01  5233.3  806.29
  5292.2  807.37  5408.0  808.24  5636.0  811.50  5740.5  814.11  5877.3  819.02
#Mann=3,-1,0
  3614.5    0.05       0  4996.2   0.033       0  5006.7    0.05       0
Bank Sta=4996.2,5006.7
Exp/Cntr=0.3,0.1

Type RM Length L Ch R = 1,16159,277,277,277
BEGIN DESCRIPTION:
Harriet Creek Tributary 5 23.0
END DESCRIPTION:
XS GIS Cut Line= 3
      2307987.13      7073551.84      2307879.00      7072460.00
      2307079.03      7071660.03
#Sta/Elev= 30
  3894.9  816.45  4025.3  812.76  4278.6  808.86  4449.4  807.20  4620.3  806.22
  4636.1  806.64  4670.5  806.37  4680.6  806.90  4700.7  805.78  4801.1  804.14
  4838.1  802.55  4861.4  802.07  4931.8  801.34  4951.9  801.60  4995.6  799.33
  5000.8  798.36  5002.3  797.86  5010.1  797.86  5011.6  798.36  5020.4  799.56
  5048.6  800.99  5076.9  800.24  5091.1  802.19  5105.2  801.57  5190.1  802.28
  5402.2  805.32  5600.2  807.01  5741.6  809.26  5996.2  812.06  6123.4  814.57
#Mann=3,-1,0
  3894.9    0.05       0  5000.8   0.033       0  5011.6    0.05       0
Bank Sta=5000.8,5011.6
Exp/Cntr=0.3,0.1

Type RM Length L Ch R = 1,15882,322,322,322
BEGIN DESCRIPTION:
Harriet Creek Tributary 5 22.0
END DESCRIPTION:
XS GIS Cut Line= 3
      2308038.20      7073497.28      2308045.01      7072189.81
      2308055.23      7071154.85
#Sta/Elev= 30
  3747.6  814.75  3794.9  813.35  3994.9  810.19  4334.9  806.88  4464.9  806.53
  4474.9  807.04  4514.9  805.23  4654.9  804.33  4784.9  802.29  4844.9  800.41
  4914.9  800.02  4934.9  799.16  4964.9  798.93  4974.9  797.80  4979.5  796.44
  4981.0  795.94  4988.8  795.94  4990.3  796.44  5004.9  797.22  5014.9  796.80
  5034.9  799.89  5052.5  800.27  5484.9  800.40  5724.9  803.10  5824.9  805.68
  5914.9  809.79  5962.9  812.77  5967.9  812.42  6004.9  814.23  6090.1  816.65
#Mann=3,-1,0
  3747.6    0.05       0  4979.5   0.033       0  4990.3    0.05       0
Bank Sta=4979.5,4990.3
Exp/Cntr=0.3,0.1

Type RM Length L Ch R = 1,15560,824,824,824
BEGIN DESCRIPTION:
Harriet Creek Tributary 5 21.5
END DESCRIPTION:
XS GIS Cut Line= 2
      2308235.69      7073401.95      2308130.14      7071127.50
#Sta/Elev= 30
  3566.5  813.00  4465.1  802.22  4549.5  801.51  4599.6  802.54  4619.6  802.19
  4629.6  801.14  4709.7  801.01  4759.7  798.45  4829.8  797.33  4849.8  798.59
  4869.9  797.89  4939.9  798.66  4974.4  796.69  4976.0  796.19  4985.5  796.69
  5010.0  797.94  5020.0  797.27  5050.0  798.04  5109.0  797.71  5130.1  798.70
  5200.2  797.98  5310.3  798.32  5332.0  799.41  5400.4  800.21  5540.0  803.33
  5550.6  804.48  5610.6  806.07  5758.0  813.47  5763.0  812.56  5843.4  815.62
#Mann=3,-1,0
  3566.5    0.05       0  4974.4   0.033       0  4985.5    0.05       0
Bank Sta=4974.4,4985.5
Exp/Cntr=0.3,0.1

Type RM Length L Ch R = 1,14736,482,482,482
BEGIN DESCRIPTION:
Harriet Creek Tributary 5 21.0
END DESCRIPTION:
XS GIS Cut Line= 3
      2308729.00      7073310.02      2308529.00      7071310.00
      2308279.03      7071160.02
#Sta/Elev= 30
  2994.5  815.16  3225.7  811.18  3376.4  807.33  3544.7  804.45  3738.2  802.35
  4502.0  796.71  4532.1  796.40  4562.3  794.62  4602.5  794.17  4650.2  794.80
  4803.5  793.55  4883.9  794.94  4893.9  794.80  4904.0  793.34  4944.2  791.53
  4956.8  793.46  4984.4  793.66  4988.9  791.23  4990.4  790.73  5000.0  791.23
  5002.0  792.22  5012.3  792.09  5018.1  793.52  5021.3  793.47  5049.2  794.56
  5055.0  794.31  5070.6  796.44  5134.7  800.35  5237.7  805.00  5296.0  808.86
#Mann=5,-1,0
  2994.5    0.05       0  4988.9   0.033       0  5000.0    0.05       0
  5021.3    0.12       0  5049.2    0.05       0
Bank Sta=4988.9,5000
Exp/Cntr=0.3,0.1

Type RM Length L Ch R = 1,14254,476,476,476
BEGIN DESCRIPTION:
Harriet Creek Tributary 5 20.0
END DESCRIPTION:
XS GIS Cut Line= 3
      2310529.00      7072860.00      2308979.00      7071310.00
      2308579.01      7070910.01
#Sta/Elev= 30
  2808.1  813.56  2893.0  811.47  2963.7  811.75  3020.2  809.58  3317.2  804.82
  3359.6  802.98  3373.8  804.04  3529.3  800.69  3840.5  796.90  4575.9  792.60
  4689.0  793.14  4773.9  791.54  4844.6  792.98  4871.9  792.01  5003.7  791.14
  5014.3  790.64  5022.9  788.27  5024.4  787.77  5034.0  788.27  5113.3  792.48
  5171.1  792.37  5225.3  792.05  5311.3  791.82  5362.1  795.02  5396.1  797.88
  5424.4  797.25  5523.4  800.21  5537.5  801.31  5551.7  806.19  5565.8  806.46
#Mann=7,-1,0
  2808.1    0.05       0  4871.9    0.12       0  5022.9    0.07       0
  5034.0    0.12       0  5171.1    0.05       0  5225.3    0.12       0
  5362.1    0.05       0
Bank Sta=5022.9,5034
Exp/Cntr=0.3,0.1

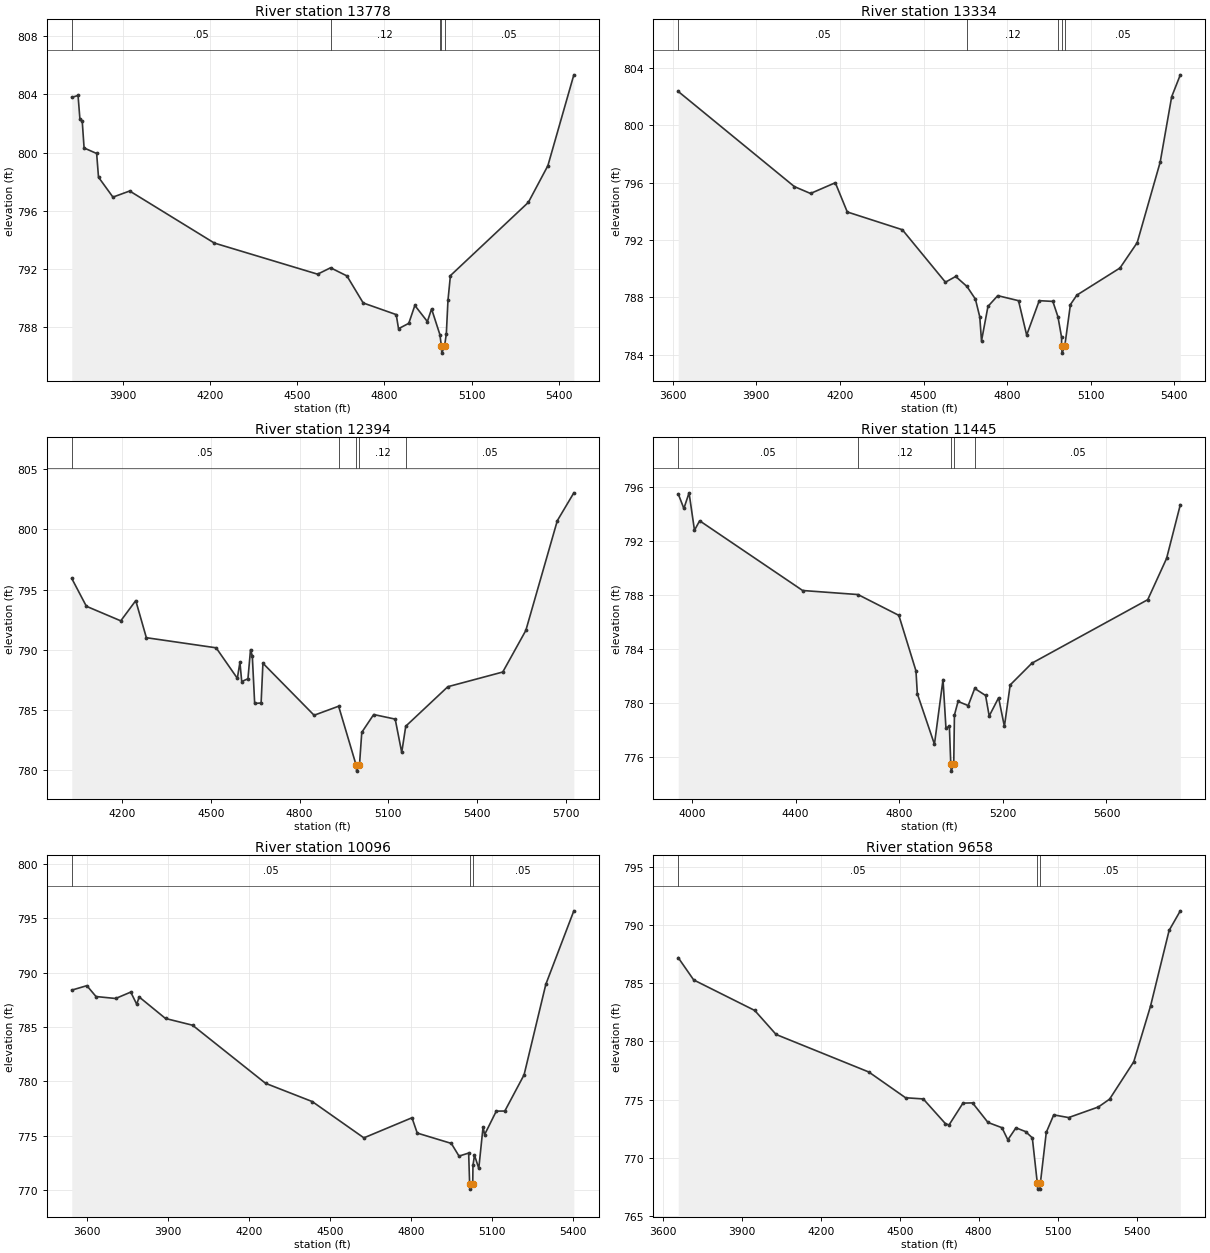
Type RM Length L Ch R = 1,13778,444,444,444
BEGIN DESCRIPTION:
Harriet Creek Tributary 5 19.0
END DESCRIPTION:
XS GIS Cut Line= 3
      2310178.99      7072109.99      2309379.00      7071110.00
      2309179.01      7070710.03
#Sta/Elev= 30
  3724.2  803.80  3745.8  803.93  3752.2  802.32  3760.2  802.16  3766.6  800.32
  3809.8  799.94  3816.2  798.31  3865.9  796.94  3923.5  797.36  4214.8  793.78
  4570.2  791.64  4614.8  792.08  4671.1  791.52  4727.1  789.66  4840.7  788.86
  4848.7  787.89  4884.0  788.26  4904.8  789.49  4948.0  788.38  4962.4  789.25
  4991.1  787.48  4996.0  786.71  4997.6  786.21  5007.2  786.71  5013.2  787.54
  5018.8  789.83  5027.2  791.54  5295.5  796.58  5362.6  799.10  5452.0  805.35
#Mann=5,-1,0
  3724.2    0.05       0  4614.8    0.12       0  4991.1    0.05       0
  4996.0   0.033       0  5007.2    0.05       0
Bank Sta=4996,5007.2
Exp/Cntr=0.3,0.1

Type RM Length L Ch R = 1,13334,940,940,940
BEGIN DESCRIPTION:
Harriet Creek Tributary 5 18.0
END DESCRIPTION:
XS GIS Cut Line= 3
      2310429.00      7072110.00      2309729.00      7070910.00
      2309628.99      7070509.96
#Sta/Elev= 30
  3619.8  802.37  4036.6  795.73  4094.5  795.25  4183.4  796.00  4226.4  793.96
  4424.0  792.72  4578.6  789.06  4615.4  789.46  4655.9  788.76  4686.1  787.88
  4701.8  786.64  4708.0  784.96  4731.2  787.37  4766.3  788.12  4840.8  787.77
  4870.1  785.37  4915.2  787.77  4964.0  787.72  4982.4  786.64  4995.4  785.21
  4995.5  784.61  4997.1  784.11  5006.8  784.61  5027.1  787.50  5050.3  788.16
  5204.9  790.05  5266.7  791.82  5349.2  797.44  5390.4  802.00  5421.4  803.53
#Mann=5,-1,0
  3619.8    0.05       0  4655.9    0.12       0  4982.4    0.05       0
  4995.5   0.033       0  5006.8    0.05       0
Bank Sta=4995.5,5006.8
Exp/Cntr=0.3,0.1

Type RM Length L Ch R = 1,12394,949,949,949
BEGIN DESCRIPTION:
Harriet Creek Tributary 5 17.0
END DESCRIPTION:
XS GIS Cut Line= 3
      2310979.02      7071460.04      2310429.00      7070660.00
      2309728.98      7070459.99
#Sta/Elev= 30
  4029.3  795.92  4078.7  793.61  4195.1  792.40  4245.8  794.08  4281.7  791.00
  4517.8  790.16  4589.5  787.63  4598.3  788.95  4604.4  787.36  4625.4  787.59
  4634.2  790.01  4640.2  789.48  4648.2  785.54  4670.0  785.58  4676.1  788.88
  4849.3  784.56  4932.3  785.31  4991.5  780.42  4993.0  779.92  5002.8  780.42
  5010.6  783.14  5050.9  784.62  5123.7  784.24  5145.8  781.47  5159.4  783.65
  5301.8  786.93  5487.7  788.15  5565.7  791.60  5672.3  800.72  5728.2  803.03
#Mann=5,-1,0
  4029.3    0.05       0  4932.3    0.12       0  4991.5    0.07       0
  5002.8    0.12       0  5159.4    0.05       0
Bank Sta=4991.5,5002.8
Exp/Cntr=0.3,0.1

Type RM Length L Ch R = 1,11445,1349,1349,1349
BEGIN DESCRIPTION:
Harriet Creek Tributary 5 16.0
END DESCRIPTION:
XS GIS Cut Line= 3
      2311279.01      7071310.03      2310979.00      7070310.00
      2310178.99      7069909.99
#Sta/Elev= 30
  3946.6  795.47  3968.4  794.39  3988.4  795.55  4009.3  792.78  4029.3  793.48
  4426.9  788.32  4640.6  788.02  4798.4  786.48  4864.5  782.37  4869.7  780.68
  4935.8  776.94  4968.9  781.73  4980.2  778.14  4993.5  778.27  4998.9  775.45
  5000.5  774.95  5010.3  775.45  5013.0  779.10  5027.0  780.11  5066.1  779.80
  5091.3  781.07  5133.2  780.55  5147.2  779.03  5183.5  780.38  5205.9  778.26
  5228.2  781.33  5312.1  782.94  5759.3  787.64  5832.0  790.69  5885.1  794.67
#Mann=5,-1,0
  3946.6    0.05       0  4640.6    0.12       0  4998.9    0.07       0
  5010.3    0.12       0  5091.3    0.05       0
Bank Sta=4998.9,5010.3
Exp/Cntr=0.3,0.1

Type RM Length L Ch R = 1,10096,438,438,438
BEGIN DESCRIPTION:
Harriet Creek Tributary 5 15.0
END DESCRIPTION:
XS GIS Cut Line= 3
      2311178.99      7070760.04      2311579.00      7069360.00
      2311378.99      7069009.98
#Sta/Elev= 30
  3543.9  788.39  3599.8  788.80  3633.6  787.80  3706.4  787.62  3762.3  788.21
  3784.4  787.09  3793.5  787.76  3891.0  785.78  3991.1  785.16  4261.6  779.81
  4434.5  778.13  4625.6  774.79  4803.7  776.64  4823.2  775.23  4949.3  774.28
  4977.9  773.11  5013.6  773.39  5017.2  770.57  5018.8  770.07  5028.7  770.57
  5029.5  772.25  5035.2  773.19  5051.1  771.98  5066.9  775.79  5072.7  775.09
  5115.9  777.25  5147.5  777.26  5218.8  780.59  5299.4  788.93  5403.1  795.69
#Mann=3,-1,0
  3543.9    0.05       0  5017.2   0.033       0  5028.7    0.05       0
Bank Sta=5017.2,5028.7
Exp/Cntr=0.3,0.1

Type RM Length L Ch R = 1,9658,470,470,470
BEGIN DESCRIPTION:
Harriet Creek Tributary 5 14.0
END DESCRIPTION:
XS GIS Cut Line= 3
      2311328.98      7070510.03      2311929.00      7069310.00
      2311528.97      7068909.97
#Sta/Elev= 30
  3658.7  787.18  3717.4  785.27  3949.4  782.65  4030.5  780.59  4382.7  777.37
  4522.4  775.16  4589.5  775.06  4673.3  772.95  4687.3  772.82  4740.4  774.70
  4776.8  774.72  4835.5  773.04  4888.6  772.59  4910.9  771.55  4941.7  772.58
  4978.0  772.26  5003.9  771.72  5022.9  767.82  5024.5  767.32  5032.8  767.32
  5034.4  767.82  5056.9  772.19  5085.2  773.69  5141.8  773.46  5254.9  774.37
  5297.4  775.04  5389.3  778.25  5452.9  783.02  5523.6  789.52  5566.1  791.20
#Mann=3,-1,0
  3658.7    0.05       0  5022.9   0.033       0  5034.4    0.05       0
Bank Sta=5022.9,5034.4
Exp/Cntr=0.3,0.1

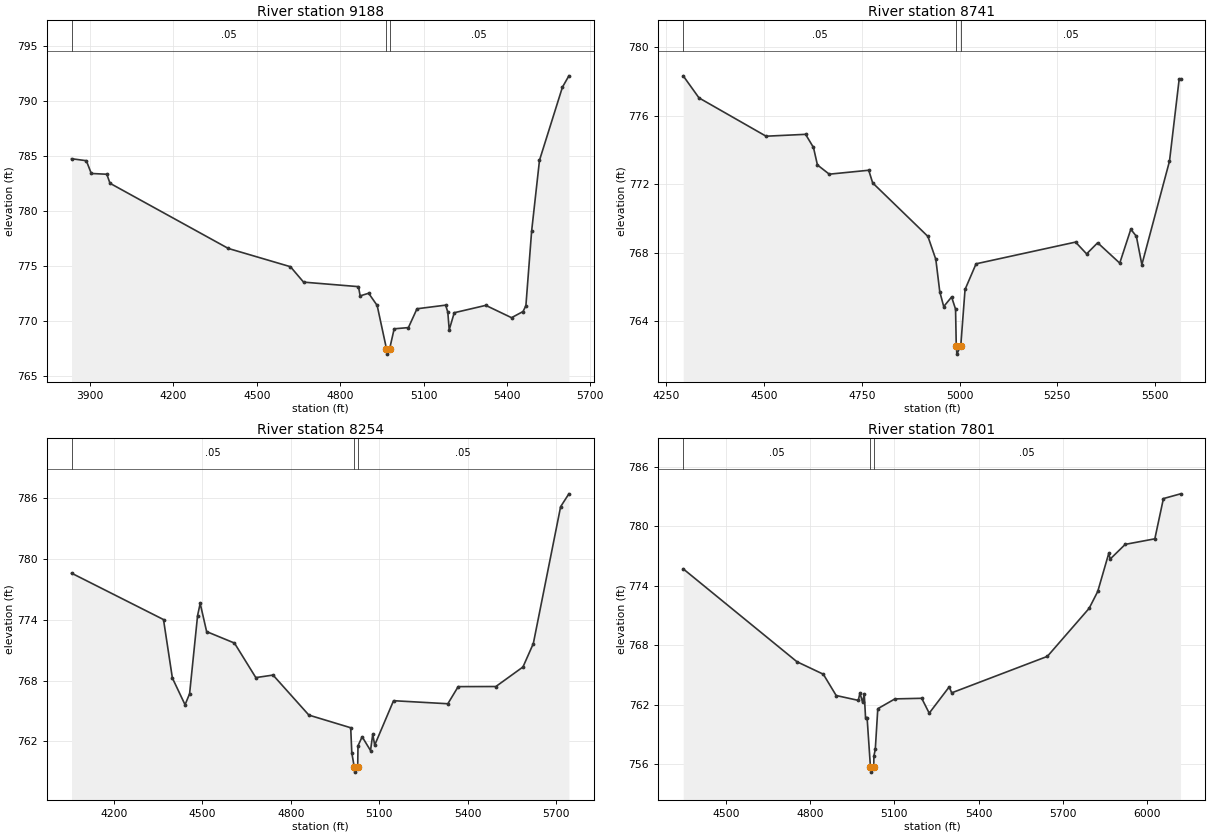
Type RM Length L Ch R = 1,9188,447,447,447
BEGIN DESCRIPTION:
Harriet Creek Tributary 5 13.0
END DESCRIPTION:
XS GIS Cut Line= 3
      2312728.99      7070509.96      2312329.00      7069410.00
      2312179.00      7068810.00
#Sta/Elev= 30
  3833.7  784.77  3886.9  784.59  3904.8  783.43  3960.7  783.36  3972.0  782.54
  4397.6  776.62  4621.1  774.96  4668.3  773.56  4865.8  773.15  4871.8  772.31
  4902.4  772.55  4933.0  771.44  4966.4  767.52  4968.0  767.02  4978.0  767.52
  4994.2  769.32  5045.4  769.43  5076.3  771.14  5179.4  771.47  5187.1  770.83
  5192.2  769.23  5210.3  770.78  5323.7  771.45  5416.4  770.33  5457.7  770.89
  5468.0  771.42  5488.6  778.19  5516.9  784.63  5599.4  791.27  5622.6  792.30
#Mann=3,-1,0
  3833.7    0.05       0  4966.4   0.033       0  4978.0    0.05       0
Bank Sta=4966.4,4978
Exp/Cntr=0.3,0.1

Type RM Length L Ch R = 1,8741,487,487,487
BEGIN DESCRIPTION:
Harriet Creek Tributary 5 12.0
END DESCRIPTION:
XS GIS Cut Line= 3
      2312629.00      7070010.01      2312729.00      7069310.00
      2312329.00      7068910.00
#Sta/Elev= 30
  4292.8  778.34  4333.2  777.05  4504.9  774.81  4606.0  774.92  4626.2  774.15
  4636.3  773.13  4666.6  772.59  4767.6  772.82  4777.7  772.08  4919.1  768.95
  4939.3  767.61  4949.4  765.72  4959.5  764.85  4979.7  765.41  4989.8  764.70
  4991.6  762.57  4993.2  762.07  5003.2  762.57  5014.1  765.85  5042.3  767.35
  5296.9  768.62  5325.2  767.93  5353.5  768.58  5410.0  767.39  5438.3  769.37
  5452.5  768.96  5466.6  767.30  5537.3  773.35  5562.1  778.15  5565.6  778.15
#Mann=3,-1,0
  4292.8    0.05       0  4991.6   0.033       0  5003.2    0.05       0
Bank Sta=4991.6,5003.2
Exp/Cntr=0.3,0.1

Type RM Length L Ch R = 1,8254,453,453,453
BEGIN DESCRIPTION:
Harriet Creek Tributary 5 11.0
END DESCRIPTION:
XS GIS Cut Line= 3
      2312678.99      7070010.01      2313179.00      7069210.00
      2312679.01      7068660.01
#Sta/Elev= 30
  4056.0  778.60  4367.9  774.02  4398.0  768.25  4441.0  765.61  4456.4  766.70
  4483.5  774.42  4492.3  775.61  4514.2  772.83  4608.5  771.70  4681.0  768.29
  4739.4  768.54  4860.9  764.59  5002.8  763.34  5006.5  760.87  5014.8  759.46
  5016.5  758.96  5026.5  759.46  5027.5  761.56  5041.6  762.45  5070.0  761.09
  5077.5  762.70  5084.2  761.63  5148.1  766.01  5332.2  765.71  5367.3  767.40
  5495.1  767.41  5587.0  769.34  5622.1  771.65  5714.7  785.16  5742.7  786.43
#Mann=3,-1,0
  4056.0    0.05       0  5014.8   0.033       0  5026.5    0.05       0
Bank Sta=5014.8,5026.5
Exp/Cntr=0.3,0.1

Type RM Length L Ch R = 1,7801,468,468,468
BEGIN DESCRIPTION:
Harriet Creek Tributary 5 10.0
END DESCRIPTION:
XS GIS Cut Line= 3
      2313179.02      7069959.97      2313529.00      7069410.00
      2313329.00      7068310.02
#Sta/Elev= 30
  4348.6  775.69  4753.3  766.32  4847.2  765.06  4893.0  762.91  4971.7  762.42
  4977.6  763.16  4986.9  762.23  4992.9  763.07  4997.5  760.68  5003.0  760.68
  5015.0  755.68  5016.6  755.18  5026.7  755.68  5027.2  756.80  5032.2  757.48
  5041.1  761.58  5102.1  762.57  5197.4  762.63  5224.1  761.13  5295.2  763.78
  5304.1  763.18  5644.6  766.86  5793.3  771.71  5823.8  773.41  5863.1  777.26
  5868.2  776.68  5921.6  778.16  6027.0  778.72  6057.5  782.78  6118.5  783.26
#Mann=3,-1,0
  4348.6    0.05       0  5015.0   0.033       0  5026.7    0.05       0
Bank Sta=5015,5026.7
Exp/Cntr=0.3,0.1