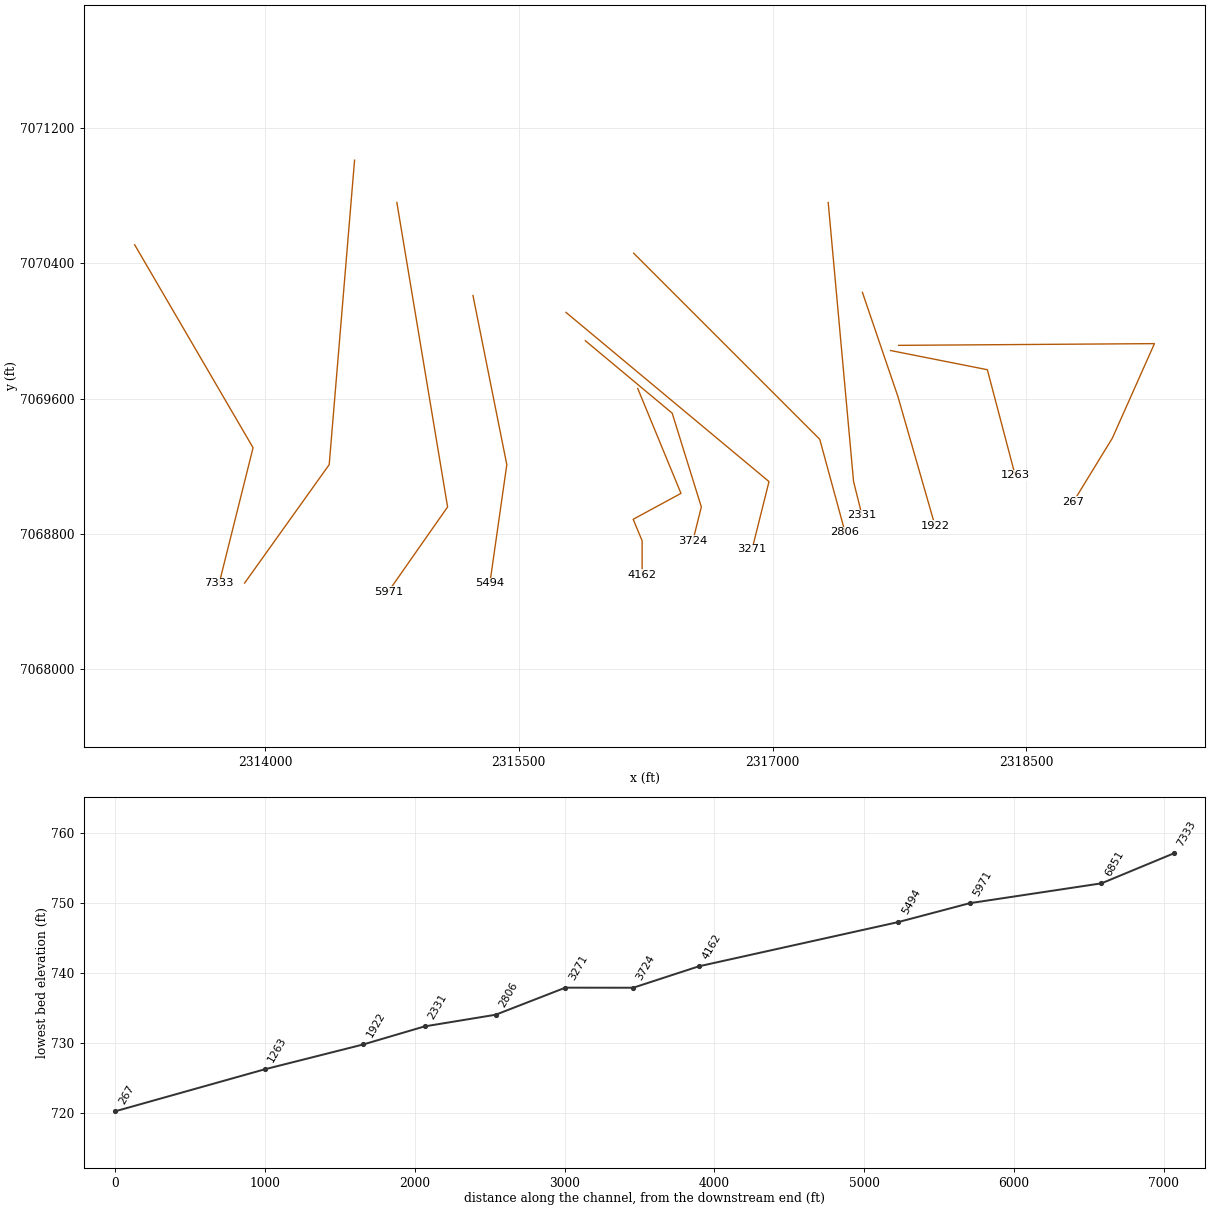
HEC-RAS study Harriet Creek Tributary 5.prj: Harriet Creek Tributary 5 Base Level Engineering

--- Harriet Creek Tributary 5.g01 (geometry) --- (continued)

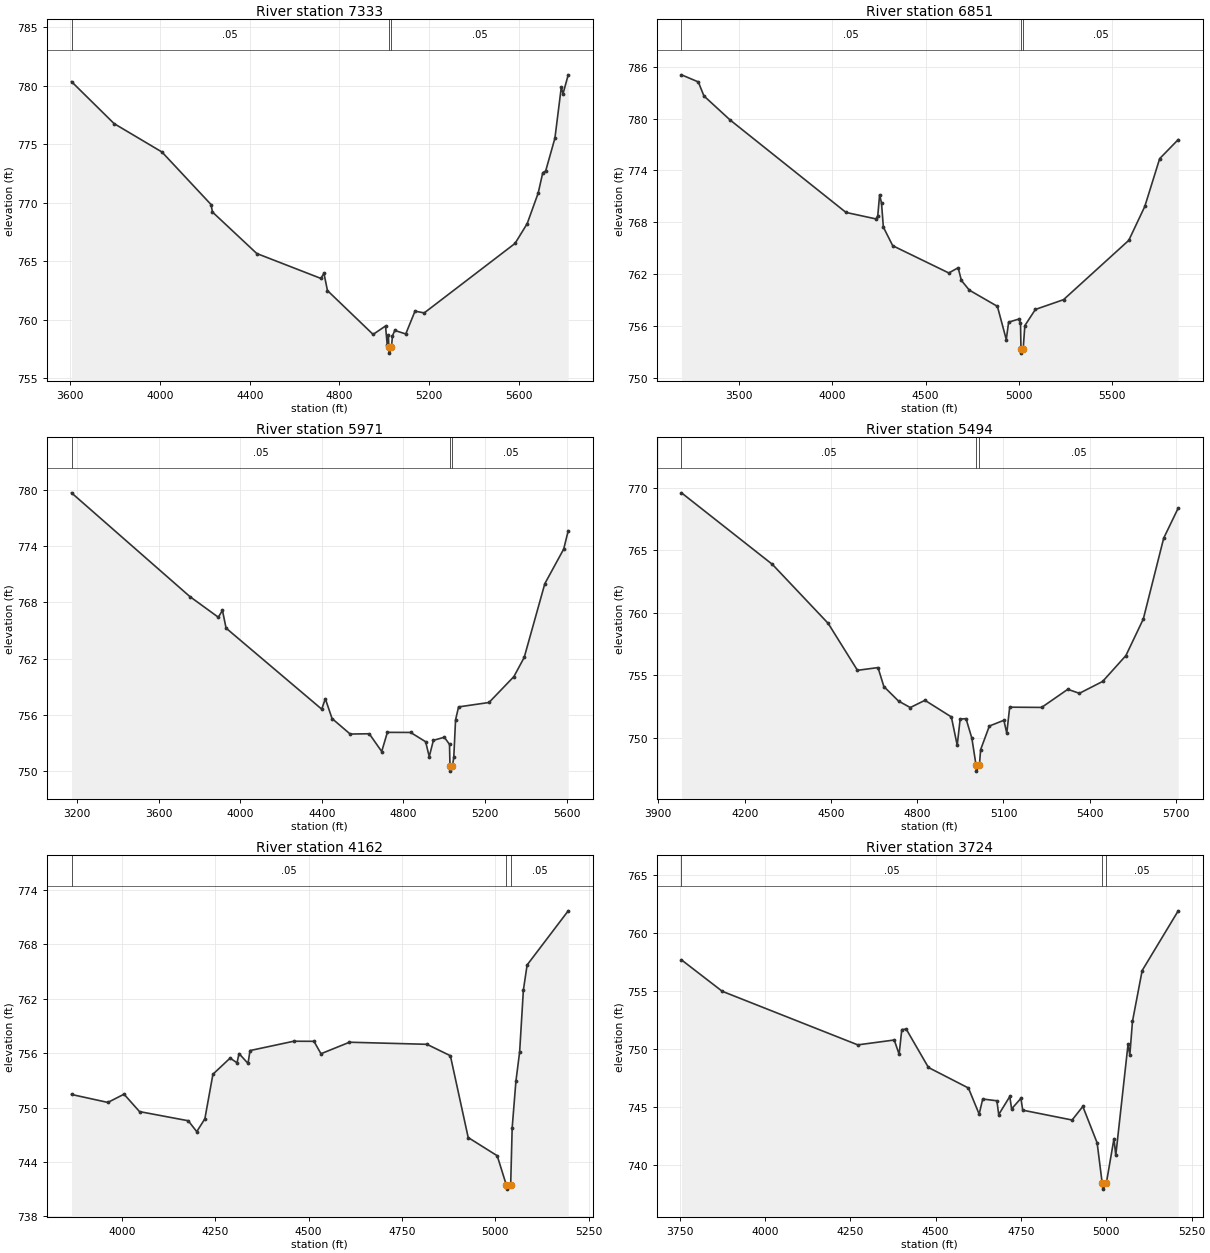
Type RM Length L Ch R = 1,7333,482,482,482
BEGIN DESCRIPTION:
Harriet Creek Tributary 5 9.0
END DESCRIPTION:
XS GIS Cut Line= 3
      2313228.99      7070510.01      2313929.00      7069310.00
      2313729.00      7068509.98
#Sta/Elev= 30
  3605.7  780.37  3795.5  776.78  4008.8  774.35  4228.0  769.85  4233.8  769.22
  4431.4  765.67  4717.1  763.54  4730.8  763.98  4746.5  762.50  4949.9  758.75
  5005.3  759.47  5013.0  757.84  5018.2  758.72  5020.0  757.65  5021.6  757.15
  5031.7  757.65  5036.2  758.62  5046.5  759.09  5095.5  758.79  5136.7  760.74
  5177.9  760.59  5582.5  766.53  5636.6  768.22  5685.6  770.83  5706.2  772.58
  5719.1  772.73  5760.3  775.53  5788.7  779.89  5796.4  779.33  5819.6  780.95
#Mann=3,-1,0
  3605.7    0.05       0  5020.0   0.033       0  5031.7    0.05       0
Bank Sta=5020,5031.7
Exp/Cntr=0.3,0.1

Type RM Length L Ch R = 1,6851,880,880,880
BEGIN DESCRIPTION:
Harriet Creek Tributary 5 8.0
END DESCRIPTION:
XS GIS Cut Line= 3
      2314529.00      7071009.96      2314379.00      7069210.00
      2313879.02      7068510.02
#Sta/Elev= 30
  3189.8  785.05  3280.1  784.23  3310.2  782.61  3450.7  779.83  4072.8  769.14
  4233.4  768.39  4243.4  768.75  4253.4  771.19  4263.5  770.22  4273.5  767.44
  4323.7  765.29  4624.7  762.14  4674.9  762.74  4692.4  761.27  4735.1  760.15
  4885.6  758.28  4933.3  754.44  4945.8  756.45  4999.1  756.80  5009.5  756.41
  5012.2  753.37  5013.8  752.87  5024.1  753.37  5032.9  756.05  5089.4  757.92
  5240.5  759.05  5590.8  765.91  5676.8  769.83  5756.7  775.36  5856.2  777.56
#Mann=3,-1,0
  3189.8    0.05       0  5012.2    0.04       0  5024.1    0.05       0
Bank Sta=5012.2,5024.1
Exp/Cntr=0.3,0.1

Type RM Length L Ch R = 1,5971,477,477,477
BEGIN DESCRIPTION:
Harriet Creek Tributary 5 7.0
END DESCRIPTION:
XS GIS Cut Line= 3
      2314779.01      7070759.97      2315079.00      7068960.00
      2314729.01      7068460.02
#Sta/Elev= 30
  3173.0  779.67  3753.4  768.62  3892.8  766.42  3913.0  767.15  3930.8  765.26
  4399.7  756.63  4417.4  757.74  4450.3  755.63  4539.1  753.98  4632.8  754.01
  4693.7  752.12  4721.5  754.16  4835.6  754.15  4909.1  753.16  4926.8  751.57
  4947.1  753.31  5000.8  753.64  5026.1  752.88  5028.5  750.53  5030.1  750.03
  5040.4  750.53  5047.1  751.52  5055.8  755.49  5070.6  756.87  5219.7  757.34
  5341.8  760.10  5392.3  762.14  5493.5  770.00  5585.9  773.68  5608.1  775.63
#Mann=3,-1,0
  3173.0    0.05       0  5028.5    0.04       0  5040.4    0.05       0
Bank Sta=5028.5,5040.4
Exp/Cntr=0.3,0.1

Type RM Length L Ch R = 1,5494,1332,1332,1332
BEGIN DESCRIPTION:
Harriet Creek Tributary 5 6.0
END DESCRIPTION:
XS GIS Cut Line= 3
      2315229.01      7070209.96      2315429.00      7069210.00
      2315329.00      7068509.97
#Sta/Elev= 30
  3980.5  769.61  4296.6  763.88  4490.4  759.16  4592.3  755.40  4663.7  755.62
  4684.1  754.10  4735.1  752.94  4775.9  752.42  4826.9  753.00  4918.7  751.67
  4939.1  749.40  4949.3  751.50  4969.7  751.53  4990.1  749.96  5004.4  747.83
  5006.1  747.33  5016.3  747.83  5020.5  749.05  5050.8  750.94  5101.3  751.40
  5111.4  750.37  5121.5  752.45  5232.6  752.43  5323.5  753.88  5363.9  753.56
  5444.7  754.51  5525.5  756.58  5586.1  759.51  5656.9  765.98  5707.4  768.39
#Mann=3,-1,0
  3980.5    0.05       0  5004.4    0.04       0  5016.3    0.05       0
Bank Sta=5004.4,5016.3
Exp/Cntr=0.3,0.1

Type RM Length L Ch R = 1,4162,438,438,438
BEGIN DESCRIPTION:
Harriet Creek Tributary 5 5.0
END DESCRIPTION:
XS GIS Cut Line= 5
      2316203.30      7069659.95      2316458.68      7069040.22
      2316176.07      7068887.00      2316229.00      7068760.00
      2316229.00      7068559.95
#Sta/Elev= 30
  3865.6  751.44  3962.9  750.56  4006.2  751.47  4047.6  749.55  4178.1  748.54
  4200.8  747.34  4222.5  748.75  4244.1  753.67  4290.1  755.45  4308.6  754.93
  4314.0  755.95  4338.0  754.86  4343.4  756.28  4460.4  757.31  4514.5  757.30
  4533.3  755.93  4609.6  757.20  4816.9  756.97  4879.6  755.71  4927.3  746.69
  5005.0  744.68  5029.0  741.50  5030.6  741.00  5041.0  741.50  5045.0  747.76
  5055.0  752.89  5065.0  756.14  5075.0  762.96  5085.0  765.72  5195.0  771.69
#Mann=3,-1,0
  3865.6    0.05       0  5029.0   0.033       0  5041.0    0.05       0
Bank Sta=5029,5041
Exp/Cntr=0.3,0.1

Type RM Length L Ch R = 1,3724,453,453,453
BEGIN DESCRIPTION:
Harriet Creek Tributary 5 4.0
END DESCRIPTION:
XS GIS Cut Line= 4
      2315893.49      7069942.51      2316406.61      7069514.49
      2316579.00      7068960.00      2316529.01      7068760.03
#Sta/Elev= 30
  3755.5  757.71  3874.9  755.00  4271.9  750.38  4378.7  750.80  4393.0  749.57
  4400.8  751.70  4413.8  751.74  4478.9  748.43  4596.0  746.66  4627.4  744.41
  4637.9  745.71  4679.4  745.56  4684.7  744.37  4717.2  745.93  4722.5  744.86
  4749.8  745.77  4755.0  744.75  4899.7  743.90  4931.1  745.07  4973.0  741.93
  4987.9  738.44  4989.6  737.94  4999.9  738.44  5022.4  742.30  5027.6  740.85
  5063.6  750.44  5068.8  749.51  5076.5  752.40  5104.9  756.79  5210.5  761.94
#Mann=3,-1,0
  3755.5    0.05       0  4987.9   0.033       0  4999.9    0.05       0
Bank Sta=4987.9,4999.9
Exp/Cntr=0.3,0.1

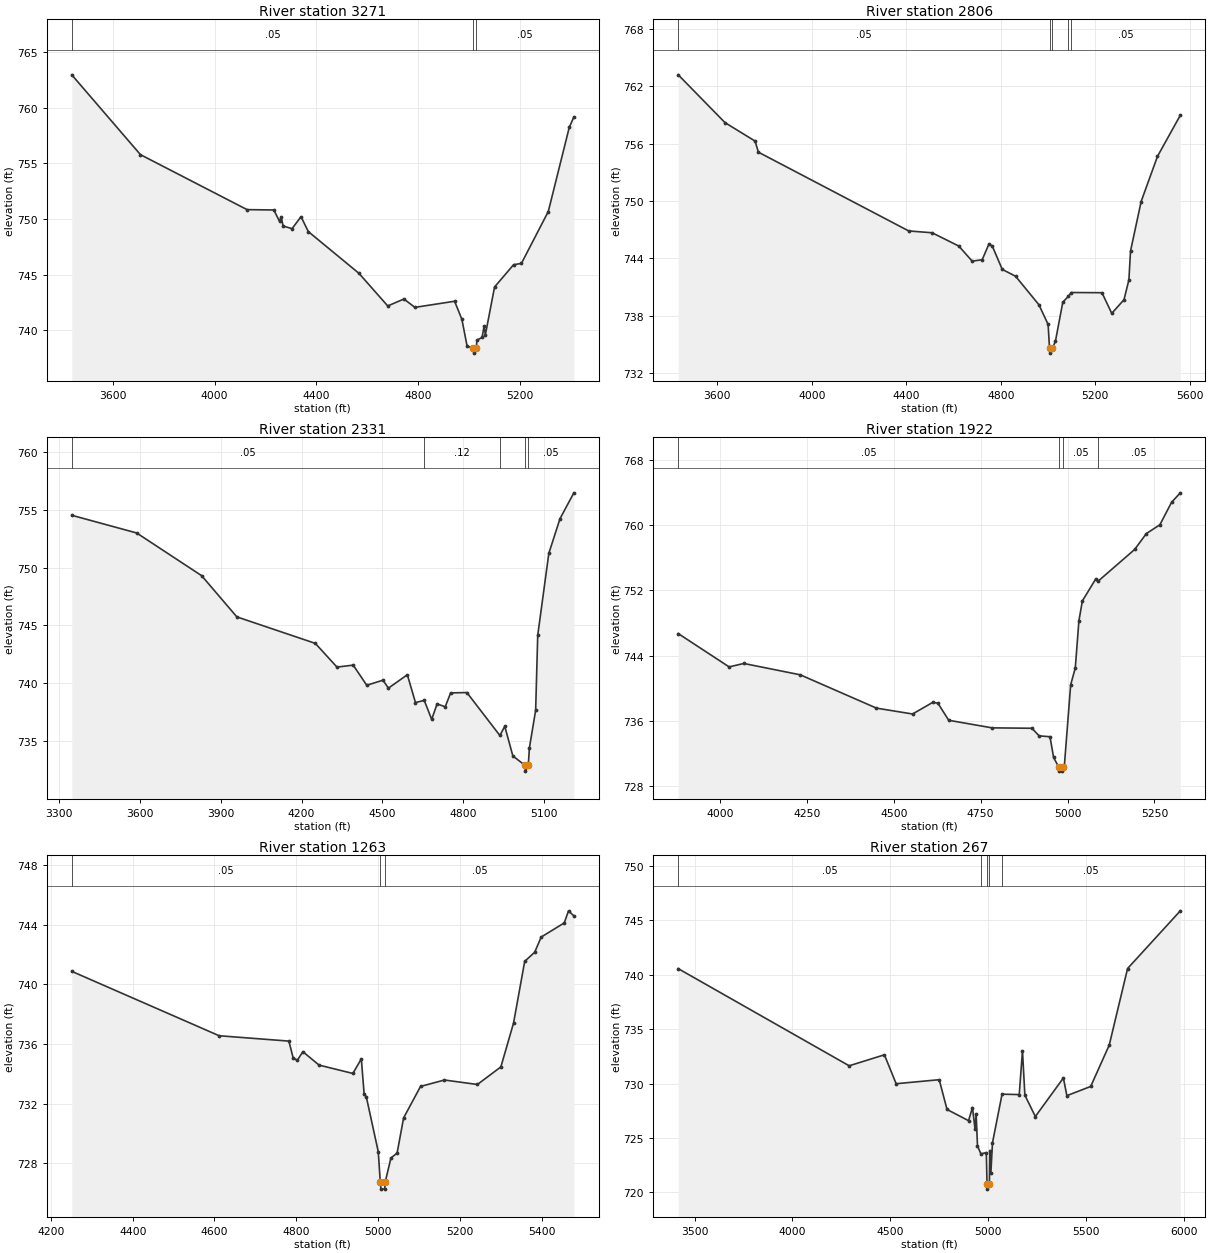
Type RM Length L Ch R = 1,3271,465,465,465
BEGIN DESCRIPTION:
Harriet Creek Tributary 5 3.0
END DESCRIPTION:
XS GIS Cut Line= 3
      2315778.97      7070110.03      2316979.00      7069110.00
      2316879.00      7068710.00
#Sta/Elev= 30
  3438.4  762.95  3708.5  755.78  4127.7  750.84  4233.1  750.81  4255.3  749.79
  4261.8  750.19  4269.6  749.37  4304.7  749.13  4339.9  750.21  4368.5  748.87
  4567.7  745.12  4680.9  742.19  4744.7  742.81  4787.7  742.06  4943.9  742.61
  4972.5  740.99  4993.3  738.55  5017.6  738.45  5019.3  737.95  5029.7  738.45
  5031.4  739.11  5052.0  739.36  5059.8  740.38  5064.9  739.60  5101.0  743.89
  5175.7  745.89  5206.6  746.01  5312.3  750.67  5394.8  758.23  5412.8  759.16
#Mann=3,-1,0
  3438.4    0.05       0  5017.6   0.033       0  5029.7    0.05       0
Bank Sta=5017.6,5029.7
Exp/Cntr=0.3,0.1

Type RM Length L Ch R = 1,2806,475,475,475
BEGIN DESCRIPTION:
Harriet Creek Tributary 5 2.0
END DESCRIPTION:
XS GIS Cut Line= 3
      2316179.01      7070459.99      2317279.00      7069360.00
      2317429.00      7068810.01
#Sta/Elev= 30
  3434.4  763.19  3632.4  758.19  3759.7  756.26  3773.8  755.10  4410.2  746.86
  4509.2  746.67  4622.3  745.28  4678.9  743.70  4721.3  743.85  4749.6  745.48
  4763.7  745.30  4806.2  742.84  4862.7  742.12  4961.7  739.13  5000.4  737.08
  5006.4  734.58  5008.1  734.08  5018.5  734.58  5031.5  735.34  5062.6  739.41
  5085.7  740.01  5099.4  740.42  5228.4  740.40  5269.9  738.24  5321.7  739.67
  5342.4  741.74  5349.3  744.76  5394.3  749.94  5463.4  754.66  5560.1  758.96
#Mann=5,-1,0
  3434.4    0.05       0  5006.4   0.033       0  5018.5    0.05       0
  5085.7    0.12       0  5099.4    0.05       0
Bank Sta=5006.4,5018.5
Exp/Cntr=0.3,0.1

Type RM Length L Ch R = 1,2331,409,409,409
BEGIN DESCRIPTION:
Harriet Creek Tributary 5 1.0
END DESCRIPTION:
XS GIS Cut Line= 3
      2317329.00      7070759.96      2317479.00      7069110.00
      2317529.00      7068910.02
#Sta/Elev= 30
  3347.4  754.52  3588.3  752.99  3829.3  749.30  3959.9  745.74  4251.1  743.45
  4331.4  741.40  4391.6  741.57  4441.9  739.83  4502.1  740.27  4522.2  739.58
  4592.5  740.74  4622.6  738.34  4655.3  738.52  4682.8  736.88  4702.9  738.22
  4733.1  737.97  4753.1  739.17  4813.4  739.20  4935.8  735.49  4954.0  736.28
  4984.1  733.72  5029.0  732.91  5030.7  732.41  5041.2  732.91  5045.4  734.42
  5068.6  737.67  5076.3  744.15  5117.5  751.23  5158.8  754.22  5210.3  756.46
#Mann=5,-1,0
  3347.4    0.05       0  4655.3    0.12       0  4935.8    0.05       0
  5029.0   0.033       0  5041.2    0.05       0
Bank Sta=5029,5041.2
Exp/Cntr=0.3,0.1

Type RM Length L Ch R = 1,1922,659,659,659
BEGIN DESCRIPTION:
Harriet Creek Tributary 5 0.7
END DESCRIPTION:
XS GIS Cut Line= 3
      2317531.23      7070228.59      2317741.37      7069611.97
      2317960.55      7068849.59
#Sta/Elev= 30
  3879.9  746.71  4026.3  742.62  4068.6  743.04  4230.9  741.65  4450.3  737.56
  4554.2  736.84  4612.3  738.27  4627.0  738.17  4658.2  736.07  4783.1  735.14
  4897.6  735.09  4918.4  734.16  4949.6  734.05  4960.0  731.51  4974.7  730.33
  4976.4  729.83  4985.2  729.83  4986.9  730.33  4991.2  730.63  5009.1  740.42
  5022.4  742.49  5032.8  748.27  5042.8  750.72  5081.7  753.44  5087.0  753.10
  5193.2  757.03  5226.9  758.98  5265.8  760.06  5299.5  762.82  5324.6  763.98
#Mann=4,-1,0
  3879.9    0.05       0  4974.7    0.07       0  4986.9    0.05       0
  5087.0    0.05       0
Bank Sta=4974.7,4986.9
Exp/Cntr=0.3,0.1

Type RM Length L Ch R = 1,1263,996,996,996
BEGIN DESCRIPTION:
Harriet Creek Tributary 5 0.5
END DESCRIPTION:
XS GIS Cut Line= 3
      2317698.08      7069884.66      2318269.82      7069771.31
      2318434.27      7069147.39
#Sta/Elev= 30
  4250.9  740.88  4611.4  736.56  4782.0  736.20  4792.2  735.10  4802.3  734.90
  4816.2  735.49  4855.8  734.59  4938.5  734.03  4959.2  735.01  4966.1  732.63
  4971.3  732.47  5000.6  728.78  5005.5  726.77  5007.2  726.27  5016.0  726.27
  5017.8  726.77  5031.6  728.36  5046.7  728.69  5062.6  731.05  5104.0  733.16
  5162.5  733.59  5243.1  733.29  5300.5  734.47  5331.5  737.41  5358.8  741.55
  5383.2  742.16  5399.1  743.18  5455.6  744.13  5466.0  744.94  5479.0  744.60
#Mann=3,-1,0
  4250.9    0.05       0  5005.5   0.033       0  5017.8    0.05       0
Bank Sta=5005.5,5017.8
Exp/Cntr=0.3,0.1

Type RM Length L Ch R = 1,267,0,0,0
BEGIN DESCRIPTION:
Harriet Creek Tributary 5 0.2
END DESCRIPTION:
XS GIS Cut Line= 4
      2317745.80      7069915.30      2319257.56      7069925.51
      2319009.00      7069367.10      2318778.27      7068990.25
#Sta/Elev= 30
  3416.5  740.57  4289.7  731.63  4469.7  732.64  4529.7  729.98  4749.7  730.35
  4789.7  727.61  4899.7  726.58  4919.7  727.79  4933.0  725.78  4938.4  727.19
  4945.3  724.26  4962.5  723.53  4990.4  723.64  4993.9  720.78  4995.6  720.28
  5006.2  720.78  5008.1  723.82  5013.6  721.75  5021.9  724.55  5070.8  729.02
  5158.5  728.98  5175.1  733.00  5187.3  728.93  5240.8  726.96  5384.1  730.51
  5401.9  728.88  5523.6  729.73  5618.2  733.53  5712.0  740.58  5981.4  745.89
#Mann=5,-1,0
  3416.5    0.05       0  4962.5    0.12       0  4993.9    0.07       0
  5006.2    0.12       0  5070.8    0.05       0
Bank Sta=4993.9,5006.2
Exp/Cntr=0.3,0.1

Chan Stop Cuts=-1