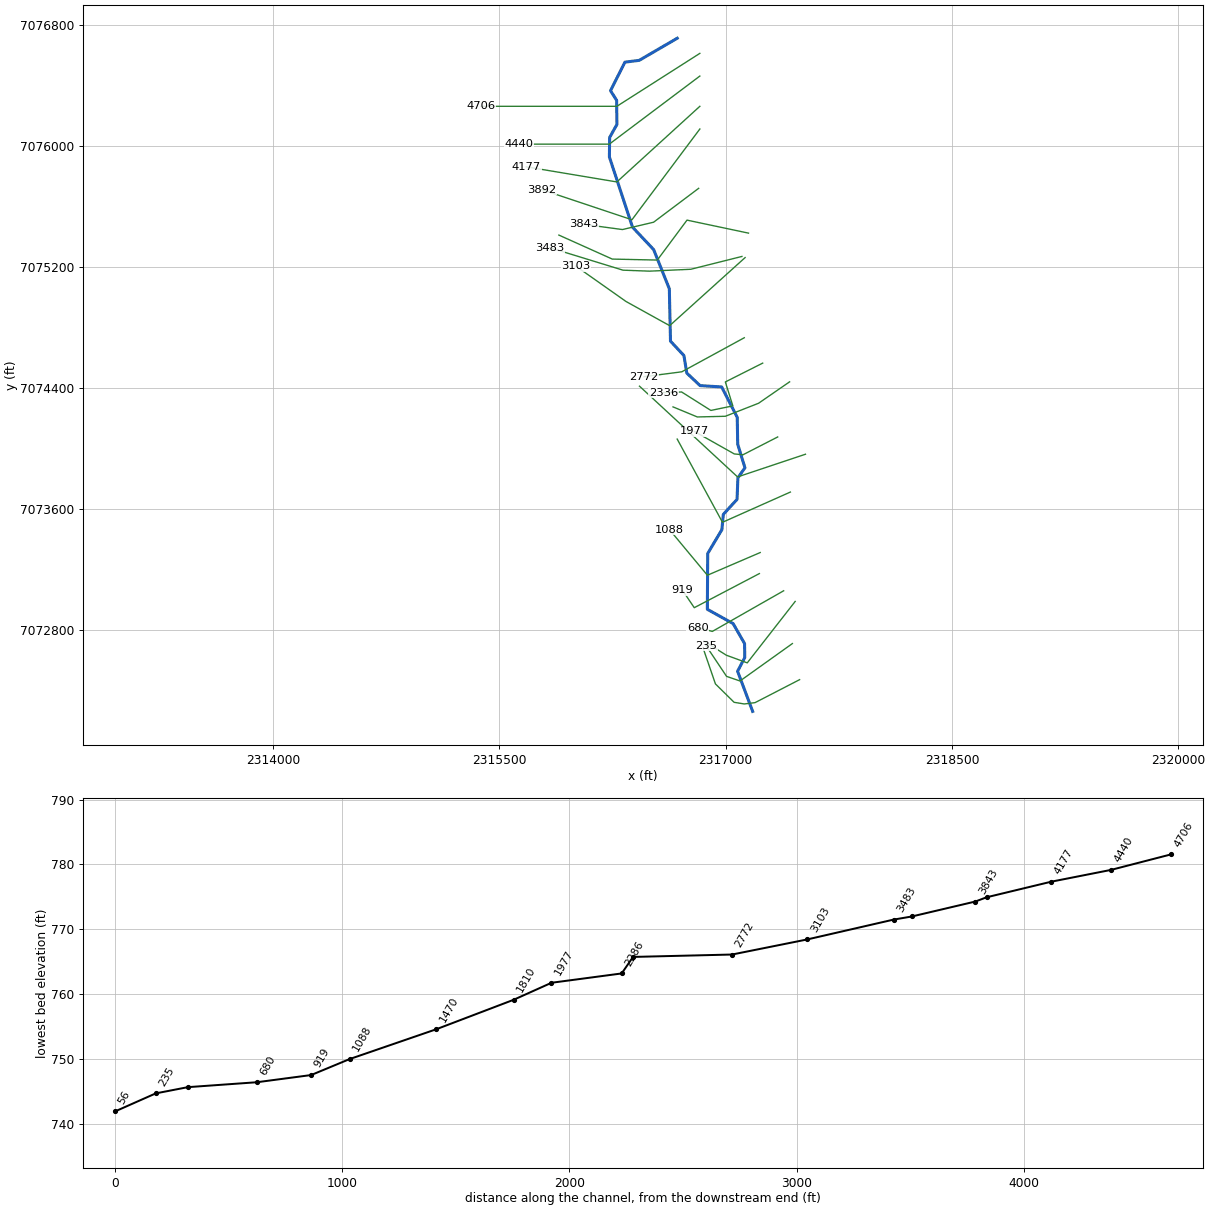
--- Harriet Creek Tributary 7.prj (project) ---

Proj Title=Harriet Creek Tributary 7 Base Level Engineering
Current Plan=p01
Default Exp/Contr=0.3,0.1
English Units
Geom File=g01
Flow File=f01
Plan File=p01
BEGIN DESCRIPTION:
Harriet Creek Tributary 7
END DESCRIPTION:

--- Harriet Creek Tributary 7.p01 (plan) ---

Plan Title=Multiple Run
Short Identifier=Multiple
Geom File=g01
Flow File=f01
Subcritical Flow
K Sum by GR= 0
Std Step Tol= 0.01
Critical Tol= 0.01
Num of Std Step Trials= 20
Max Error Tol= 0.3
Flow Tol Ratio= 0.001
Split Flow NTrial= 30
Split Flow Tol= 0.02
Split Flow Ratio= 0.02
Log Output Level= 0
Friction Slope Method= 1
Unsteady Friction Slope Method= 2
Unsteady Bridges Friction Slope Method= 1
Parabolic Critical Depth
Global Vel Dist=  1 , 1 , 1
Global Log Level= 0
CheckData=True
Encroach Param= -1, 0, 0, 0
BEGIN DESCRIPTION:
Multiple Run
END DESCRIPTION:

--- Harriet Creek Tributary 7.f01 (steady flow) ---

Flow Title=Multiple
Number of Profiles=7
Profile Names=10-year,25-year,50-year,1pct_min,100-year,1pct_plu,500-year
River Rch & RM= Harriet Creek Tr,Reach-1,4706
     351     464     553     328     654    1310     918
River Rch & RM= Harriet Creek Tr,Reach-1,2336
     407     542     651     388     775    1550    1100
Boundary for River Rch & Prof#=Harriet Creek Tr,Reach-1,1
Up Type=0
Dn Type=3
Dn Slope=0.005
Boundary for River Rch & Prof#=Harriet Creek Tr,Reach-1,2
Up Type=0
Dn Type=3
Dn Slope=0.005
Boundary for River Rch & Prof#=Harriet Creek Tr,Reach-1,3
Up Type=0
Dn Type=3
Dn Slope=0.005
Boundary for River Rch & Prof#=Harriet Creek Tr,Reach-1,4
Up Type=0
Dn Type=3
Dn Slope=0.005
Boundary for River Rch & Prof#=Harriet Creek Tr,Reach-1,5
Up Type=0
Dn Type=3
Dn Slope=0.005
Boundary for River Rch & Prof#=Harriet Creek Tr,Reach-1,6
Up Type=0
Dn Type=3
Dn Slope=0.005
Boundary for River Rch & Prof#=Harriet Creek Tr,Reach-1,7
Up Type=0
Dn Type=3
Dn Slope=0.005

--- Harriet Creek Tributary 7.g01 (geometry) ---

Geom Title=Existing Conditions

River Reach=Harriet Creek Tr,Reach-1
Reach XY= 30
      2316679.00      7076710.00      2316427.34      7076563.86
      2316332.38      7076551.85      2316237.04      7076363.32
      2316277.62      7076299.56      2316279.36      7076139.85
      2316231.25      7076054.06      2316229.50      7075925.22
      2316382.61      7075461.50      2316523.17      7075312.30
      2316626.74      7075054.06      2316634.47      7074707.55
      2316723.46      7074612.42      2316742.39      7074496.67
      2316830.46      7074413.54      2316973.59      7074404.82
      2317076.76      7074204.07      2317079.96      7074025.96
      2317127.80      7073870.52      2317081.27      7073804.06
      2317075.44      7073661.47      2316984.54      7073562.42
      2316975.17      7073461.59      2316881.24      7073304.07
      2316878.67      7072934.78      2317049.48      7072840.38
      2317125.33      7072708.42      2317126.81      7072615.97
      2317079.09      7072525.39      2317179.00      7072260.00

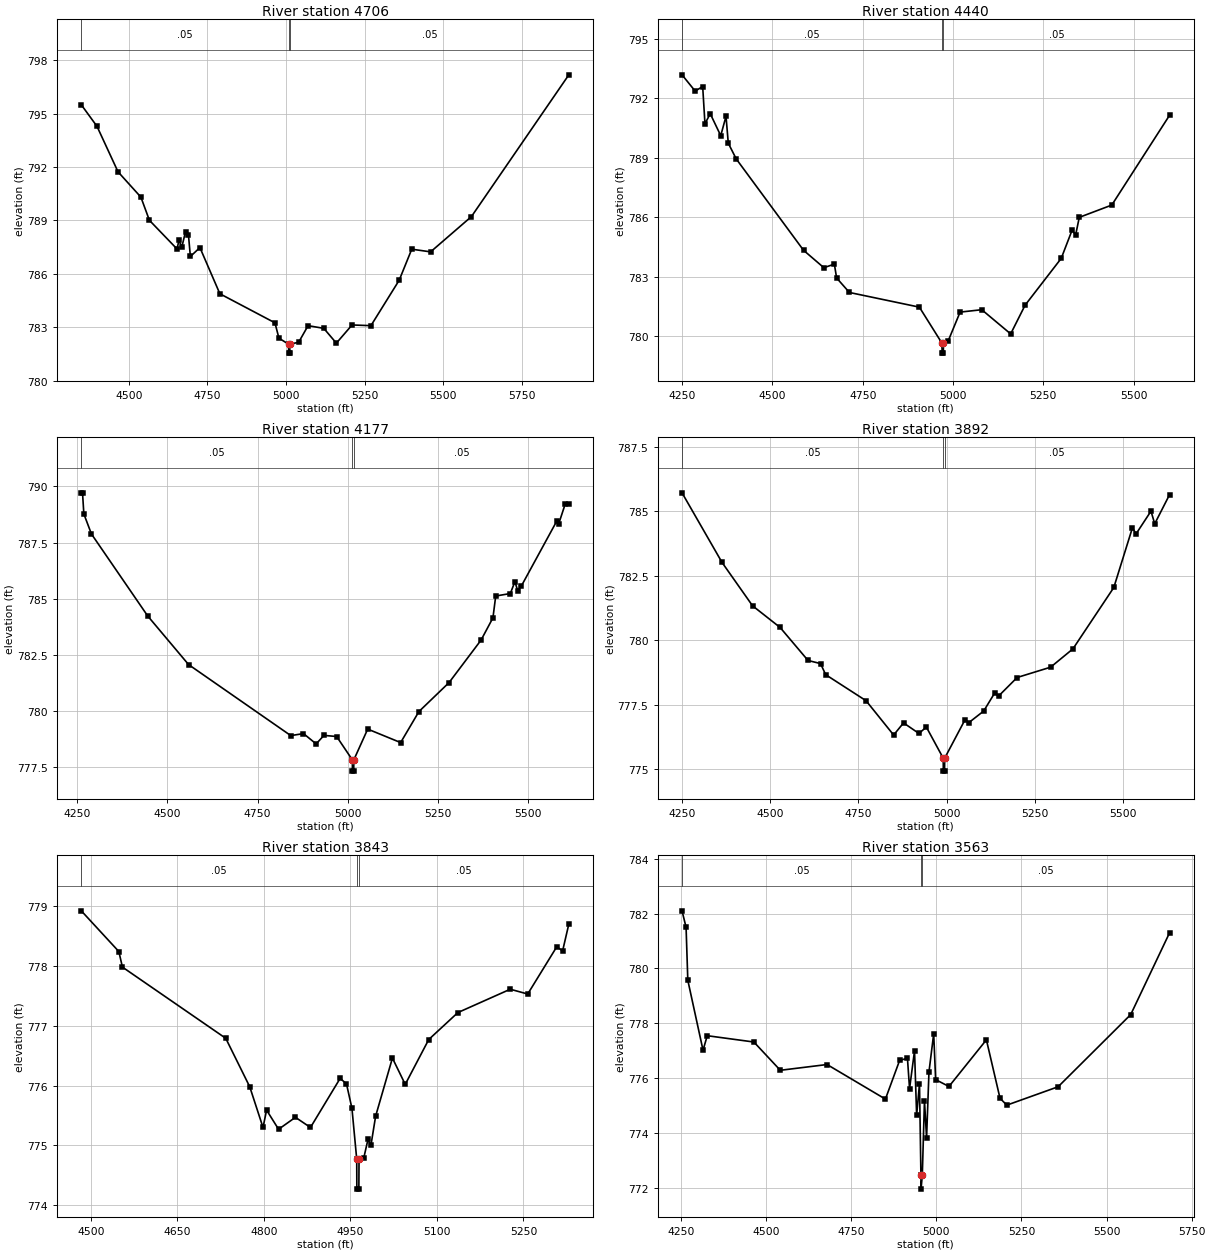
Type RM Length L Ch R = 1,4706,266,266,266
BEGIN DESCRIPTION:
Harriet Creek Tributary 7 9.0
END DESCRIPTION:
XS GIS Cut Line= 3
      2316829.02      7076610.01      2316279.00      7076260.00
      2315379.05      7076260.00
#Sta/Elev= 30
  4348.5  795.49  4398.5  794.28  4465.4  791.73  4538.2  790.31  4565.3  789.01
  4653.3  787.40  4659.2  787.88  4668.6  787.52  4680.4  788.38  4689.7  788.17
  4695.7  786.98  4726.1  787.48  4789.6  784.89  4964.9  783.26  4977.6  782.40
  5008.4  782.06  5008.7  781.56  5012.2  781.56  5012.4  782.06  5040.4  782.17
  5070.4  783.10  5120.4  782.95  5160.4  782.12  5210.4  783.14  5270.4  783.10
  5360.4  785.65  5400.4  787.39  5460.4  787.24  5590.4  789.22  5900.4  797.17
#Mann=3,-1,0
  4348.5    0.05       0  5008.4   0.033       0  5012.4    0.05       0
Bank Sta=5008.4,5012.4
Exp/Cntr=0.3,0.1

Type RM Length L Ch R = 1,4440,263,263,263
BEGIN DESCRIPTION:
Harriet Creek Tributary 7 8.0
END DESCRIPTION:
XS GIS Cut Line= 3
      2316828.96      7076459.97      2316229.00      7076010.00
      2315628.96      7076010.00
#Sta/Elev= 30
  4249.6  793.19  4286.0  792.37  4306.8  792.60  4313.1  790.72  4327.7  791.23
  4356.8  790.12  4371.4  791.10  4377.7  789.74  4399.6  788.95  4586.0  784.34
  4642.3  783.46  4671.4  783.64  4677.7  782.94  4713.1  782.21  4906.8  781.47
  4969.4  779.65  4969.7  779.15  4973.2  779.15  4973.4  779.65  4986.0  779.74
  5019.6  781.22  5079.6  781.34  5159.6  780.12  5199.6  781.57  5299.6  783.93
  5329.6  785.35  5339.6  785.12  5349.6  786.00  5439.6  786.62  5599.6  791.15
#Mann=3,-1,0
  4249.6    0.05       0  4969.4   0.033       0  4973.4    0.05       0
Bank Sta=4969.4,4973.4
Exp/Cntr=0.3,0.1

Type RM Length L Ch R = 1,4177,285,285,285
BEGIN DESCRIPTION:
Harriet Creek Tributary 7 7.0
END DESCRIPTION:
XS GIS Cut Line= 3
      2316829.02      7076260.02      2316279.00      7075760.00
      2315679.01      7075860.00
#Sta/Elev= 30
  4261.2  789.71  4264.6  789.71  4268.3  788.77  4289.3  787.88  4445.4  784.23
  4558.6  782.07  4842.0  778.91  4877.2  779.00  4912.3  778.54  4933.9  778.92
  4969.1  778.87  5012.7  777.83  5012.9  777.33  5016.4  777.33  5016.7  777.83
  5055.2  779.20  5146.5  778.60  5197.2  779.98  5280.8  781.27  5369.5  783.16
  5402.4  784.15  5410.1  785.12  5450.6  785.23  5463.3  785.76  5470.9  785.36
  5481.0  785.56  5579.9  788.47  5584.9  788.34  5602.7  789.21  5612.8  789.21
#Mann=3,-1,0
  4261.2    0.05       0  5012.7   0.033       0  5016.7    0.05       0
Bank Sta=5012.7,5016.7
Exp/Cntr=0.3,0.1

Type RM Length L Ch R = 1,3892,49,49,49
BEGIN DESCRIPTION:
Harriet Creek Tributary 7 6.0
END DESCRIPTION:
XS GIS Cut Line= 3
      2316828.98      7076109.97      2316379.00      7075510.00
      2315779.01      7075710.00
#Sta/Elev= 30
  4250.0  785.71  4363.5  783.01  4450.0  781.33  4528.1  780.49  4607.3  779.21
  4642.7  779.09  4657.3  778.66  4771.8  777.65  4850.0  776.32  4878.1  776.79
  4921.8  776.38  4942.7  776.63  4990.7  775.42  4990.9  774.92  4994.4  774.92
  4994.7  775.42  5052.7  776.92  5063.2  776.80  5105.4  777.25  5137.0  777.96
  5147.5  777.83  5200.2  778.55  5295.1  778.95  5358.4  779.66  5474.3  782.04
  5527.0  784.35  5537.5  784.12  5579.7  785.00  5590.3  784.51  5632.4  785.64
#Mann=3,-1,0
  4250.0    0.05       0  4990.7   0.033       0  4994.7    0.05       0
Bank Sta=4990.7,4994.7
Exp/Cntr=0.3,0.1

Type RM Length L Ch R = 1,3843,280,280,280
BEGIN DESCRIPTION:
1663
END DESCRIPTION:
XS GIS Cut Line= 4
      2316821.10      7075717.75      2316522.46      7075493.77
      2316315.91      7075445.28      2316058.31      7075480.05
#Sta/Elev= 30
  4483.3  778.92  4548.4  778.24  4554.6  777.98  4733.8  776.79  4775.4  775.98
  4798.4  775.30  4804.6  775.59  4825.4  775.27  4854.6  775.47  4880.7  775.30
  4932.1  776.12  4943.1  776.03  4952.6  775.62  4960.9  774.77  4961.1  774.27
  4964.6  774.27  4964.9  774.77  4973.1  774.79  4980.4  775.10  4985.5  775.00
  4993.7  775.49  5022.8  776.46  5045.0  776.02  5085.8  776.77  5136.3  777.22
  5227.1  777.61  5257.4  777.53  5307.8  778.32  5317.9  778.25  5328.7  778.70
#Mann=3,-1,0
  4483.3    0.05       0  4960.9   0.033       0  4964.9    0.05       0
Bank Sta=4960.9,4964.9
Exp/Cntr=0.3,0.1

Type RM Length L Ch R = 1,3563,80,80,80
BEGIN DESCRIPTION:
Harriet Creek Tributary 7 5.0
END DESCRIPTION:
XS GIS Cut Line= 5
      2317151.46      7075421.65      2316743.87      7075507.59
      2316547.12      7075243.55      2316248.74      7075250.09
      2315894.92      7075408.63
#Sta/Elev= 30
  4253.1  782.10  4265.0  781.50  4270.1  779.57  4314.8  777.02  4327.2  777.55
  4464.2  777.32  4541.8  776.29  4679.1  776.50  4850.5  775.24  4892.2  776.65
  4915.2  776.73  4921.4  775.62  4936.0  777.00  4942.2  774.65  4950.6  775.80
  4954.8  772.46  4955.1  771.96  4958.8  772.46  4965.2  775.18  4971.4  773.83
  4978.4  776.23  4992.3  777.62  4998.0  775.95  5037.1  775.70  5147.1  777.40
  5187.1  775.27  5207.1  775.02  5357.8  775.69  5571.0  778.32  5685.1  781.30
#Mann=3,-1,0
  4253.1    0.05       0  4954.8   0.033       0  4958.8    0.05       0
Bank Sta=4954.8,4958.8
Exp/Cntr=0.3,0.1

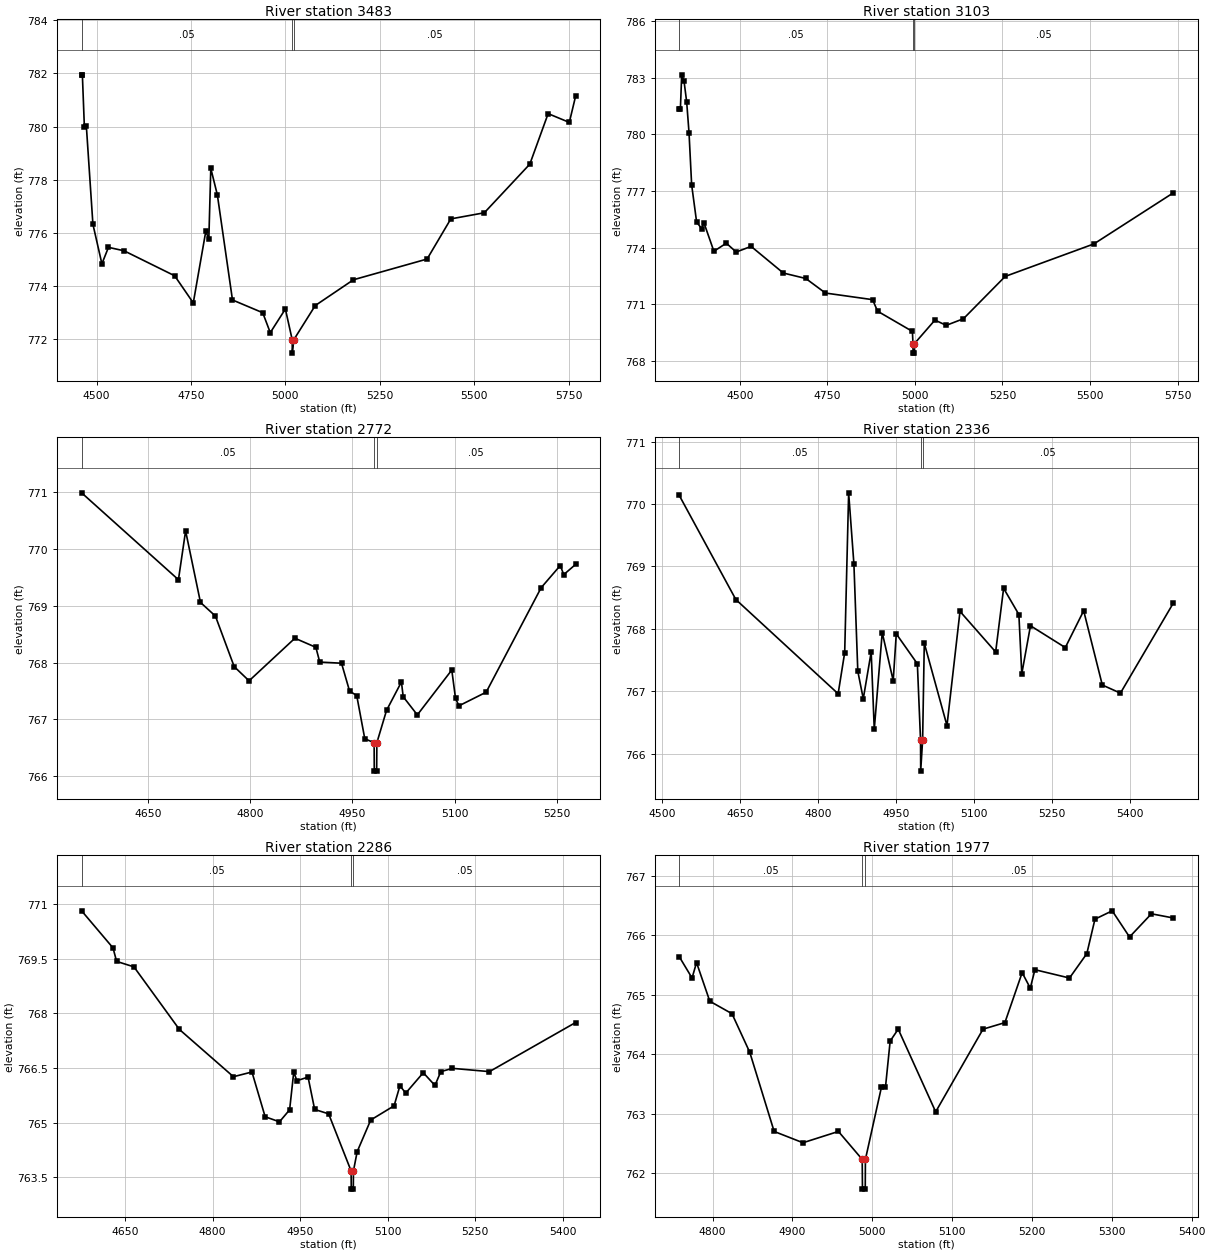
Type RM Length L Ch R = 1,3483,380,380,380
BEGIN DESCRIPTION:
1662
END DESCRIPTION:
XS GIS Cut Line= 5
      2317107.99      7075267.57      2316769.39      7075182.76
      2316496.09      7075170.27      2316320.03      7075176.68
      2315832.99      7075325.86
#Sta/Elev= 30
  4460.5  781.95  4462.5  781.95  4467.8  779.99  4473.0  780.03  4490.4  776.33
  4514.2  774.84  4531.6  775.46  4572.9  775.33  4706.9  774.39  4756.2  773.37
  4789.3  776.06  4797.4  775.78  4802.6  778.43  4820.0  777.43  4860.0  773.48
  4940.1  773.00  4960.1  772.25  5000.1  773.14  5018.2  771.98  5018.4  771.48
  5022.2  771.98  5079.2  773.27  5180.3  774.24  5375.4  775.02  5438.2  776.53
  5526.9  776.76  5647.4  778.59  5695.9  780.49  5752.0  780.16  5768.7  781.15
#Mann=3,-1,0
  4460.5    0.05       0  5018.2   0.033       0  5022.2    0.05       0
Bank Sta=5018.2,5022.2
Exp/Cntr=0.3,0.1

Type RM Length L Ch R = 1,3103,331,331,331
BEGIN DESCRIPTION:
Harriet Creek Tributary 7 4.0
END DESCRIPTION:
XS GIS Cut Line= 4
      2317129.01      7075260.01      2316629.00      7074810.00
      2316340.16      7074969.46      2316006.84      7075203.83
#Sta/Elev= 30
  4327.2  781.35  4330.6  781.35  4334.3  783.15  4341.0  782.81  4348.5  781.72
  4355.2  780.09  4362.7  777.33  4376.9  775.36  4391.1  775.01  4397.8  775.32
  4426.2  773.81  4461.7  774.24  4489.8  773.77  4532.4  774.07  4624.3  772.66
  4688.6  772.37  4744.6  771.60  4879.2  771.25  4893.4  770.64  4992.8  769.57
  4994.5  768.92  4994.8  768.42  4998.3  768.42  4998.5  768.92  5057.2  770.17
  5089.3  769.89  5138.5  770.24  5257.7  772.48  5510.9  774.20  5737.3  776.90
#Mann=3,-1,0
  4327.2    0.05       0  4994.5   0.033       0  4998.5    0.05       0
Bank Sta=4994.5,4998.5
Exp/Cntr=0.3,0.1

Type RM Length L Ch R = 1,2772,436,436,436
BEGIN DESCRIPTION:
1661
END DESCRIPTION:
XS GIS Cut Line= 3
      2317123.59      7074730.11      2316709.46      7074504.88
      2316458.96      7074472.48
#Sta/Elev= 30
  4553.1  770.99  4695.0  769.46  4705.5  770.32  4727.3  769.06  4749.2  768.82
  4776.7  767.93  4798.5  767.68  4865.7  768.43  4896.4  768.27  4902.1  768.01
  4934.0  767.99  4945.8  767.50  4956.3  767.42  4968.1  766.66  4981.8  766.59
  4982.0  766.09  4985.5  766.09  4985.8  766.59  5000.0  767.16  5021.8  767.66
  5024.4  767.40  5045.1  767.08  5095.6  767.87  5101.1  767.37  5106.1  767.24
  5146.0  767.48  5226.6  769.32  5254.6  769.71  5259.7  769.55  5277.1  769.73
#Mann=3,-1,0
  4553.1    0.05       0  4981.8   0.033       0  4985.8    0.05       0
Bank Sta=4981.8,4985.8
Exp/Cntr=0.3,0.1

Type RM Length L Ch R = 1,2336,50,50,50
BEGIN DESCRIPTION:
1664
END DESCRIPTION:
XS GIS Cut Line= 6
      2317245.47      7074562.31      2316998.01      7074437.89
      2317047.63      7074279.66      2316902.14      7074249.49
      2316708.38      7074371.52      2316587.65      7074367.49
#Sta/Elev= 30
  4533.2  770.14  4642.0  768.47  4838.5  766.96  4851.1  767.62  4858.7  770.18
  4868.8  769.04  4876.3  767.32  4886.8  766.88  4902.0  767.63  4907.9  766.39
  4923.2  767.94  4944.3  767.17  4950.2  767.92  4990.7  767.44  4996.8  766.22
  4997.1  765.72  5000.8  766.22  5004.0  767.77  5047.6  766.45  5072.6  768.28
  5141.1  767.63  5156.4  768.65  5185.7  768.23  5191.3  767.28  5208.0  768.05
  5274.9  767.70  5310.2  768.29  5346.0  767.10  5380.8  766.97  5482.2  768.41
#Mann=3,-1,0
  4533.2    0.05       0  4996.8    0.04       0  5000.8    0.05       0
Bank Sta=4996.8,5000.8
Exp/Cntr=0.3,0.1

Type RM Length L Ch R = 1,2286,309,309,309
BEGIN DESCRIPTION:
1660
END DESCRIPTION:
XS GIS Cut Line= 5
      2317423.83      7074438.60      2317218.20      7074297.01
      2316997.91      7074210.90      2316812.29      7074206.39
      2316651.37      7074272.96
#Sta/Elev= 30
  4575.8  770.82  4629.6  769.80  4635.7  769.43  4665.4  769.28  4743.2  767.56
  4835.8  766.26  4867.5  766.39  4890.1  765.16  4914.6  765.02  4932.0  765.35
  4939.1  766.39  4944.5  766.15  4963.6  766.25  4974.9  765.36  4998.8  765.24
  5037.3  763.67  5037.6  763.17  5041.1  763.17  5041.3  763.67  5047.7  764.20
  5070.9  765.07  5110.9  765.46  5120.9  766.01  5130.9  765.81  5160.9  766.37
  5180.9  766.02  5190.9  766.40  5210.9  766.49  5274.2  766.40  5421.8  767.75
#Mann=3,-1,0
  4575.8    0.05       0  5037.3    0.04       0  5041.3    0.05       0
Bank Sta=5037.3,5041.3
Exp/Cntr=0.3,0.1

Type RM Length L Ch R = 1,1977,167,167,167
BEGIN DESCRIPTION:
1659
END DESCRIPTION:
XS GIS Cut Line= 4
      2317344.79      7074074.16      2317114.87      7073956.44
      2317057.18      7073961.97      2316793.63      7074110.31
#Sta/Elev= 30
  4758.2  765.64  4774.3  765.28  4779.9  765.54  4796.5  764.89  4824.3  764.68
  4846.6  764.03  4877.1  762.70  4913.2  762.51  4957.6  762.70  4987.4  762.23
  4987.7  761.73  4991.2  761.73  4991.4  762.23  5011.4  763.44  5016.5  763.44
  5022.4  764.22  5032.5  764.42  5079.4  763.03  5138.7  764.42  5166.1  764.53
  5187.7  765.37  5197.9  765.11  5203.7  765.42  5247.0  765.28  5268.7  765.69
  5278.9  766.27  5300.5  766.41  5322.2  765.97  5349.6  766.36  5376.9  766.29
#Mann=3,-1,0
  4758.2    0.05       0  4987.4    0.04       0  4991.4    0.05       0
Bank Sta=4987.4,4991.4
Exp/Cntr=0.3,0.1

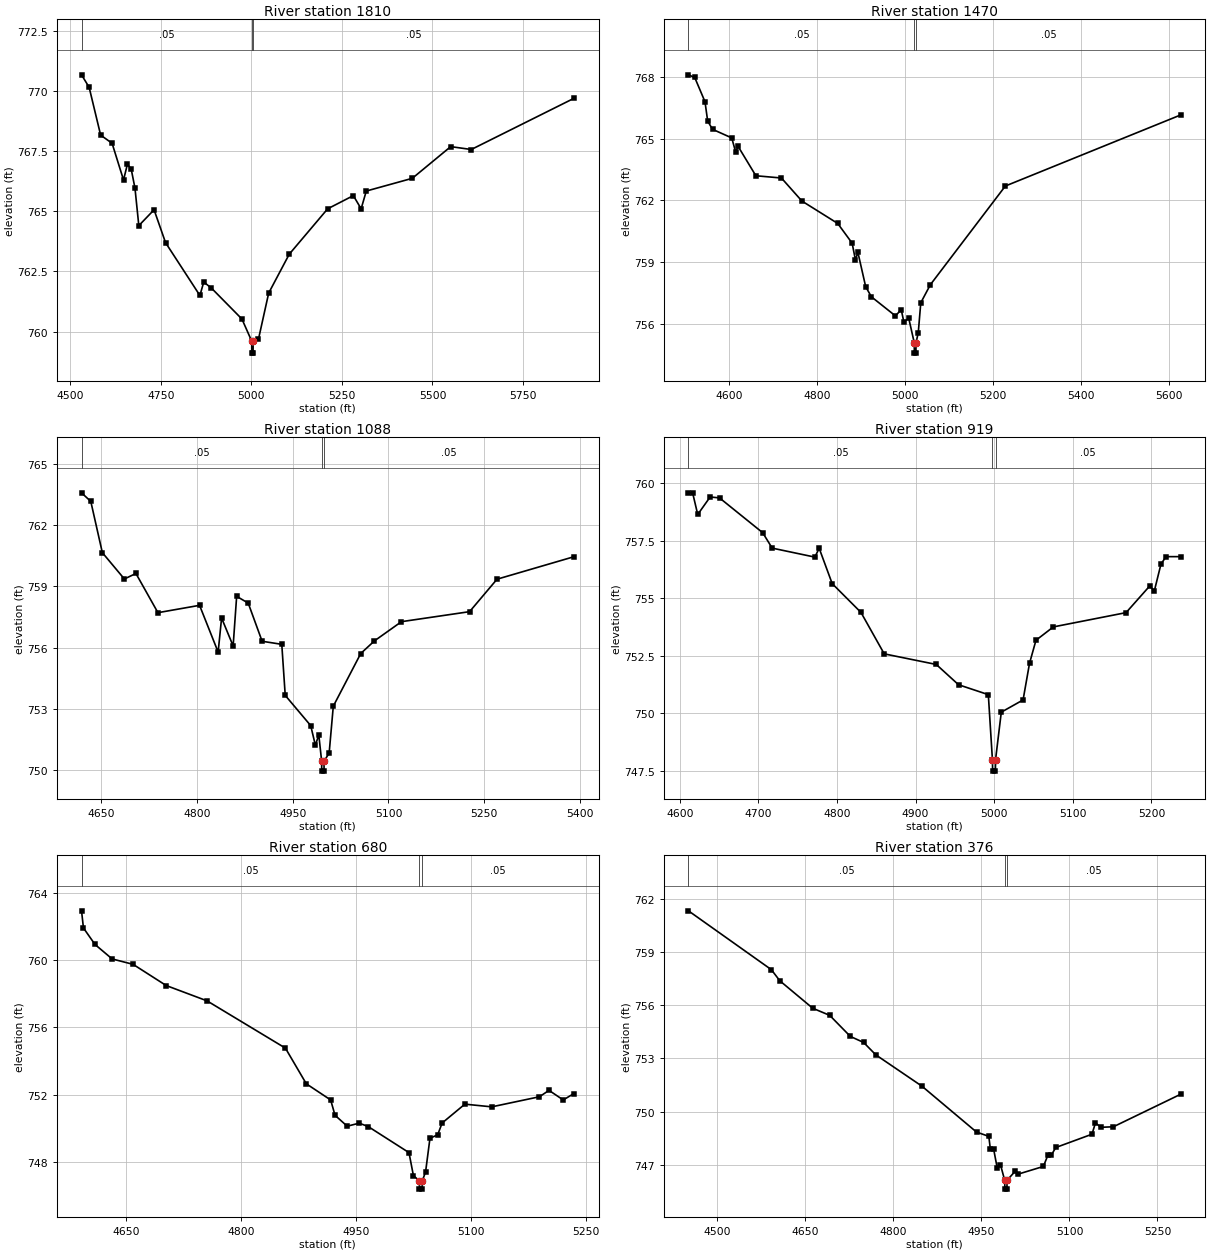
Type RM Length L Ch R = 1,1810,340,340,340
BEGIN DESCRIPTION:
Harriet Creek Tributary 7 3.0
END DESCRIPTION:
XS GIS Cut Line= 3
      2317528.96      7073959.99      2317079.00      7073810.00
      2316428.99      7074410.01
#Sta/Elev= 30
  4531.5  770.69  4552.5  770.17  4584.2  768.18  4615.8  767.84  4647.4  766.31
  4658.0  766.96  4668.5  766.77  4679.0  765.97  4689.6  764.41  4731.7  765.07
  4763.4  763.70  4858.2  761.50  4868.8  762.06  4889.9  761.81  4974.2  760.52
  5001.2  759.60  5001.4  759.10  5004.9  759.10  5005.2  759.60  5019.7  759.67
  5048.0  761.60  5104.8  763.22  5210.8  765.11  5281.7  765.66  5303.2  765.11
  5317.4  765.85  5444.4  766.38  5550.4  767.70  5607.2  767.58  5890.4  769.71
#Mann=3,-1,0
  4531.5    0.05       0  5001.2    0.04       0  5005.2    0.05       0
Bank Sta=5001.2,5005.2
Exp/Cntr=0.3,0.1

Type RM Length L Ch R = 1,1470,382,382,382
BEGIN DESCRIPTION:
Harriet Creek Tributary 7 2.0
END DESCRIPTION:
XS GIS Cut Line= 3
      2317428.96      7073709.98      2316979.00      7073510.00
      2316679.00      7074060.00
#Sta/Elev= 30
  4507.5  768.10  4521.8  767.97  4545.1  766.79  4551.2  765.85  4562.2  765.45
  4605.9  765.03  4614.8  764.34  4620.3  764.62  4660.7  763.19  4718.8  763.08
  4765.3  761.96  4846.7  760.87  4879.5  759.91  4887.0  759.09  4892.5  759.47
  4910.3  757.79  4923.3  757.30  4978.0  756.37  4991.0  756.68  4997.2  756.06
  5008.0  756.27  5020.7  755.06  5020.9  754.56  5024.4  754.56  5024.7  755.06
  5029.8  755.56  5035.5  757.01  5057.3  757.89  5227.7  762.69  5626.4  766.15
#Mann=3,-1,0
  4507.5    0.05       0  5020.7    0.04       0  5024.7    0.05       0
Bank Sta=5020.7,5024.7
Exp/Cntr=0.3,0.1

Type RM Length L Ch R = 1,1088,169,169,169
BEGIN DESCRIPTION:
Harriet Creek Tributary 7 1.0
END DESCRIPTION:
XS GIS Cut Line= 3
      2317228.99      7073310.00      2316879.00      7073160.00
      2316628.99      7073460.01
#Sta/Elev= 30
  4619.2  763.58  4633.7  763.16  4651.8  760.65  4686.3  759.36  4704.4  759.63
  4738.9  757.71  4804.1  758.07  4833.2  755.78  4838.6  757.45  4856.7  756.08
  4862.2  758.51  4880.3  758.18  4902.1  756.31  4932.9  756.16  4938.3  753.66
  4978.2  752.18  4985.5  751.22  4990.9  751.72  4995.3  750.45  4995.5  749.95
  4999.0  749.95  4999.3  750.45  5007.1  750.83  5013.6  753.13  5056.6  755.71
  5078.1  756.33  5120.4  757.27  5227.1  757.76  5270.1  759.35  5390.5  760.45
#Mann=3,-1,0
  4619.2    0.05       0  4995.3   0.033       0  4999.3    0.05       0
Bank Sta=4995.3,4999.3
Exp/Cntr=0.3,0.1

Type RM Length L Ch R = 1,919,239,239,239
BEGIN DESCRIPTION:
Harriet Creek Tributary 7 0.7
END DESCRIPTION:
XS GIS Cut Line= 3
      2317223.42      7073170.99      2316792.02      7072945.49
      2316713.78      7073060.88
#Sta/Elev= 30
  4611.1  759.57  4616.4  759.57  4622.9  758.63  4638.7  759.39  4650.6  759.35
  4705.5  757.84  4717.6  757.17  4771.8  756.78  4777.4  757.16  4793.9  755.63
  4830.5  754.38  4860.1  752.58  4926.3  752.12  4954.6  751.24  4992.5  750.81
  4997.7  747.99  4998.0  747.49  5001.5  747.49  5001.7  747.99  5009.0  750.05
  5036.7  750.58  5044.9  752.17  5053.1  753.17  5075.2  753.75  5167.7  754.37
  5197.6  755.52  5203.7  755.32  5212.1  756.48  5218.6  756.80  5237.3  756.80
#Mann=3,-1,0
  4611.1    0.05       0  4997.7   0.033       0  5001.7    0.05       0
Bank Sta=4997.7,5001.7
Exp/Cntr=0.3,0.1

Type RM Length L Ch R = 1,680,304,304,304
BEGIN DESCRIPTION:
Harriet Creek Tributary 7 0.5
END DESCRIPTION:
XS GIS Cut Line= 3
      2317384.27      7073057.28      2316911.64      7072788.61
      2316815.53      7072814.11
#Sta/Elev= 30
  4591.5  762.92  4594.0  761.90  4609.1  760.92  4631.5  760.06  4658.8  759.74
  4702.1  758.48  4755.4  757.57  4857.8  754.76  4885.1  752.64  4916.9  751.68
  4922.6  750.77  4938.5  750.12  4954.2  750.30  4965.9  750.10  5019.2  748.55
  5025.0  747.18  5032.7  746.88  5032.9  746.38  5036.4  746.38  5036.7  746.88
  5040.9  747.41  5046.6  749.40  5056.7  749.61  5062.5  750.31  5092.2  751.43
  5127.3  751.27  5189.6  751.87  5202.1  752.25  5220.7  751.68  5234.6  752.06
#Mann=3,-1,0
  4591.5    0.05       0  5032.7   0.033       0  5036.7    0.05       0
Bank Sta=5032.7,5036.7
Exp/Cntr=0.3,0.1

Type RM Length L Ch R = 1,376,141,141,141
BEGIN DESCRIPTION:
Harriet Creek Tributary 7 0.2
END DESCRIPTION:
XS GIS Cut Line= 4
      2317460.75      7072986.71      2317143.04      7072580.74
      2317003.81      7072631.73      2316855.41      7072725.45
#Sta/Elev= 30
  4450.5  761.33  4591.8  758.01  4606.3  757.38  4662.4  755.83  4691.3  755.43
  4726.5  754.24  4749.1  753.90  4769.9  753.20  4848.6  751.43  4941.6  748.84
  4962.5  748.60  4965.2  747.87  4970.8  747.87  4977.0  746.79  4982.3  747.01
  4989.6  746.12  4989.9  745.62  4993.4  745.62  4993.6  746.12  5007.5  746.63
  5012.9  746.47  5055.5  746.90  5063.2  747.53  5068.6  747.52  5076.8  747.97
  5138.4  748.72  5144.3  749.36  5153.7  749.11  5174.9  749.14  5289.8  750.98
#Mann=3,-1,0
  4450.5    0.05       0  4989.6    0.04       0  4993.6    0.05       0
Bank Sta=4989.6,4993.6
Exp/Cntr=0.3,0.1

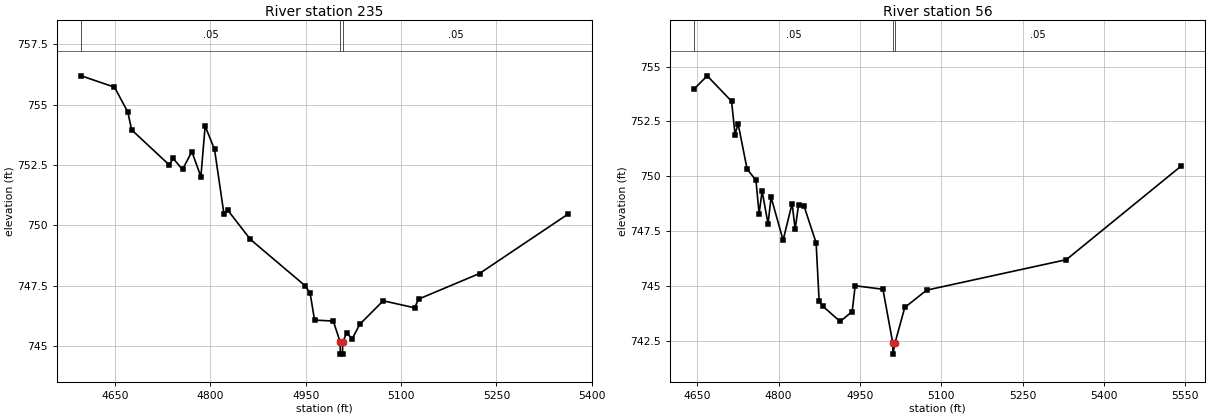
Type RM Length L Ch R = 1,235,179,179,179
BEGIN DESCRIPTION:
Harriet Creek Tributary 7 0.1
END DESCRIPTION:
XS GIS Cut Line= 4
      2317442.31      7072708.41      2317095.10      7072461.03
      2317006.13      7072491.41      2316869.53      7072695.22
#Sta/Elev= 30
  4596.8  756.19  4649.1  755.72  4670.0  754.69  4676.1  753.95  4735.2  752.50
  4741.3  752.77  4756.1  752.31  4770.8  753.05  4785.0  752.01  4791.7  754.11
  4806.5  753.14  4821.2  750.48  4827.4  750.62  4863.0  749.41  4949.1  747.49
  4956.9  747.18  4963.8  746.07  4993.3  746.03  5004.1  745.16  5004.3  744.66
  5007.8  744.66  5008.1  745.16  5014.2  745.53  5023.1  745.30  5035.1  745.90
  5071.8  746.87  5121.2  746.58  5127.5  746.94  5223.3  748.00  5362.5  750.46
#Mann=3,-1,0
  4596.8    0.05       0  5004.1    0.04       0  5008.1    0.05       0
Bank Sta=5004.1,5008.1
Exp/Cntr=0.3,0.1

Type RM Length L Ch R = 1,56,0,0,0
BEGIN DESCRIPTION:
Harriet Creek Tributary 7 0.05
END DESCRIPTION:
XS GIS Cut Line= 6
      2317490.10      7072469.73      2317194.93      7072317.80
      2317123.32      7072309.12      2317056.04      7072319.97
      2316932.34      7072441.50      2316849.89      7072680.19
#Sta/Elev= 30
  4644.4  753.99  4668.1  754.58  4713.1  753.42  4719.5  751.90  4725.1  752.40
  4741.7  750.33  4758.1  749.81  4763.9  748.29  4769.5  749.32  4780.4  747.83
  4786.0  749.04  4808.2  747.08  4824.8  748.75  4830.4  747.59  4836.8  748.70
  4846.9  748.63  4869.1  746.96  4874.7  744.30  4881.8  744.06  4913.4  743.37
  4935.6  743.82  4941.2  745.00  4992.4  744.84  5010.6  742.38  5010.8  741.88
  5014.6  742.38  5032.7  744.01  5073.1  744.80  5330.8  746.19  5542.6  750.46
#Mann=3,-1,0
  4644.4    0.05       0  5010.6    0.04       0  5014.6    0.05       0
Bank Sta=5010.6,5014.6
Exp/Cntr=0.3,0.1

Chan Stop Cuts=-1