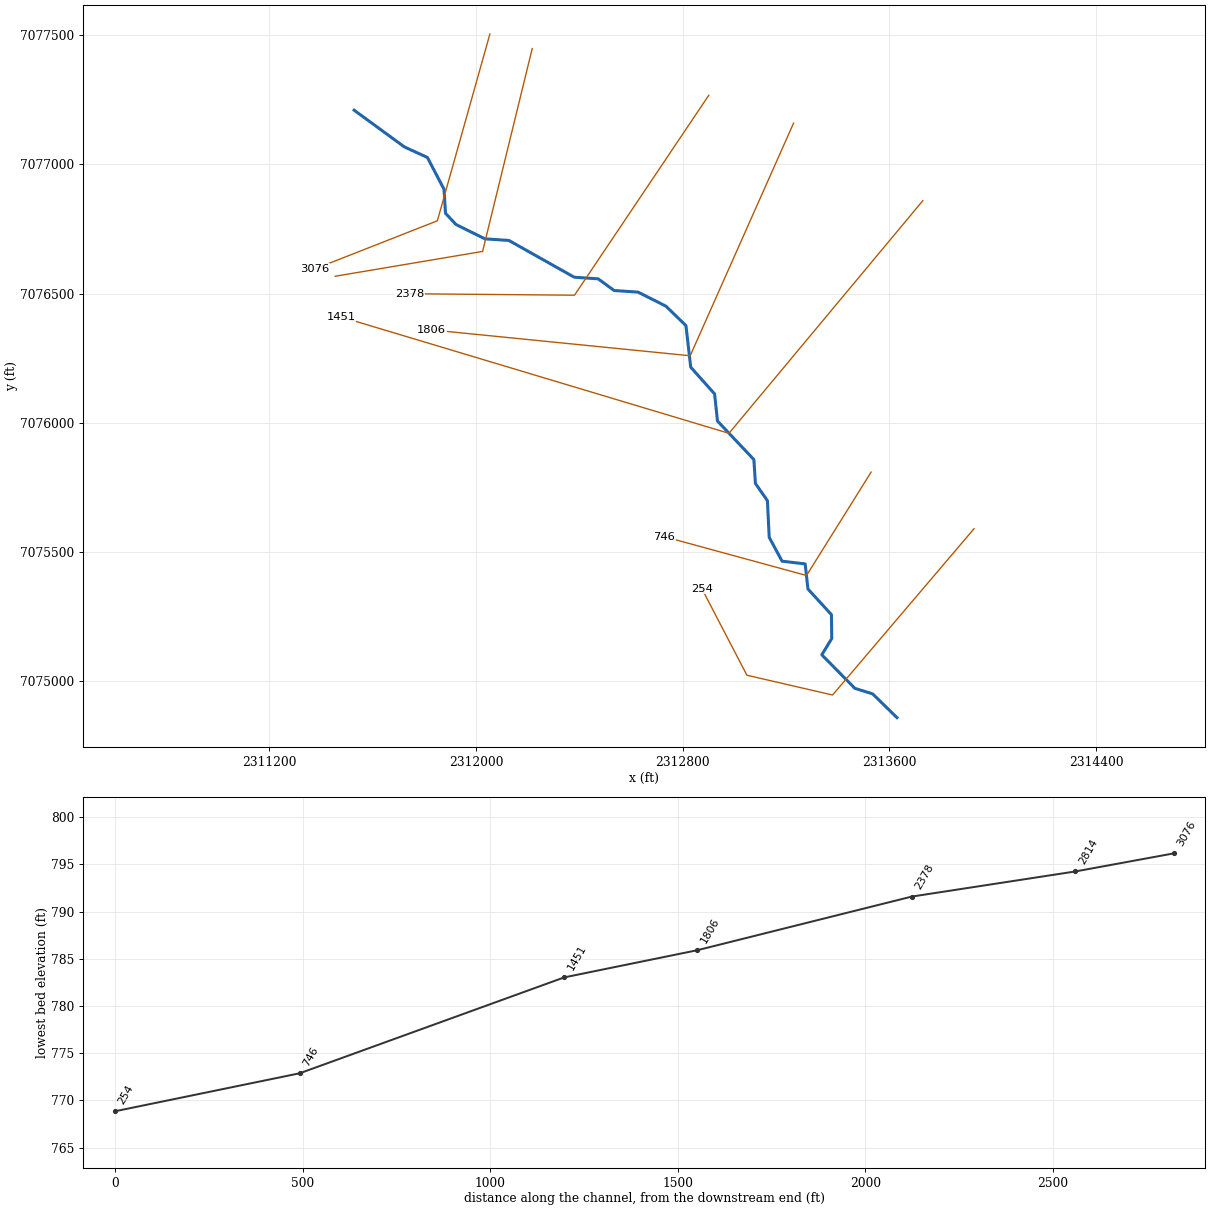
--- Harriet Creek Tributary 8.prj (project) ---

Proj Title=Harriet Creek Tributary 8 Base Level Engineering
Current Plan=p01
Default Exp/Contr=0.3,0.1
English Units
Geom File=g01
Flow File=f01
Plan File=p01
Y Axis Title=Elevation
X Axis Title(PF)=Main Channel Distance
X Axis Title(XS)=Station
BEGIN DESCRIPTION:
Harriet Creek Tributary 8
END DESCRIPTION:
DSS Export Rating Curves= 0
DSS Export Rating Curve Sorted= 0
DSS Export Volume Flow Curves= 0
DXF OffsetX= 0
DXF OffsetY= 0
DXF ScaleX= 1
DXF ScaleY= 10

--- Harriet Creek Tributary 8.p01 (plan) ---

Plan Title=Multiple Run
Program Version=4.10
Short Identifier=Multiple
Geom File=g01
Flow File=f01
Subcritical Flow
K Sum by GR= 0
Std Step Tol= 0.01
Critical Tol= 0.01
Num of Std Step Trials= 20
Max Error Tol= 0.3
Flow Tol Ratio= 0.001
Split Flow NTrial= 30
Split Flow Tol= 0.02
Split Flow Ratio= 0.02
Log Output Level= 0
Friction Slope Method= 0
Unsteady Friction Slope Method= 2
Unsteady Bridges Friction Slope Method= 1
Parabolic Critical Depth
Global Vel Dist= 1 , 1 , 1
Global Log Level= 0
CheckData=True
Encroach Param=-1 ,0,0, 0
BEGIN DESCRIPTION:
Multiple Run
END DESCRIPTION:
Computation Interval=1HOUR
Output Interval=1HOUR
Run HTab= 0
Run UNet= 0
Run PostProcess= 0
Run WQNet= 0
UNET Theta= 1
UNET Theta Warmup= 1
UNET ZTol= 0.02
UNET ZSATol= 0.05
UNET MxIter= 20
UNET MaxInSteps= 0
UNET DtIC= 0
UNET DtMin= 0
UNET MaxCRTS= 20
UNET WFStab= 2
UNET SFStab= 1
UNET WFX= 1
UNET SFX= 1
UNET DSS MLevel= 4
UNET DZMax Abort= 100
UNET Convert EG Bridges= 0
UNET Use Existing IB Tables=-1
UNET Froude Reduction=False
UNET Froude Limit= 1
UNET Froude Power= 10
UNET Time Slicing=0,0, 5
UNET Junction Losses=0
Instantaneous Interval=1HOUR
Write IC File= 0
Write IC File at Sim End=0
Echo Input=False
Echo Parameters=False
Echo Output=False
Write Detailed= 0
WQ AD Non Conservative
WQ ULTIMATE=-1
WQ Max Comp Step=1HOUR
WQ Output Interval=15MIN
WQ Output Selected Increments= 0
WQ Output face flow=0
WQ Output face velocity=0
WQ Output face area=0
WQ Output face dispersion=0
WQ Output cell volume=0
WQ Output cell surface area=0
WQ Output cell continuity=0
WQ Output cumulative cell continuity=0
WQ Output face conc=0
WQ Output face dconc_dx=0
WQ Output face courant=0
WQ Output face peclet=0
WQ Output face adv mass=0
WQ Output face disp mass=0
WQ Output cell mass=0
WQ Output cell source sink temp=0
WQ Output cell source sink nsm=0
WQ Output MaxMinRange=-1
WQ Daily Max Min Mean=-1
WQ Daily Range=0
WQ Daily Time=0
WQ Create Restart=0
WQ Fixed Restart=0
WQ System Summary=0
WQ Use Fixed Temperature=0
Sorting and Armoring Iterations= 10
XS Update Threshold= 0.02
Hydraulics Update Threshold= 0.02
Energy Slope Method= 1
Volume Change Method= 0
XS Weighting Method= 0
Number of US Weighted Cross Sections= 1
Number of DS Weighted Cross Sections= 1
Upstream XS Weight=0.25
Main XS Weight=0.5
Downstream XS Weight=0.25
Number of DS XS's Weighted with US Boundary= 1
Upstream Boundary Weight= 1
Weight of XSs Associated with US Boundary= 0
Number of US XS's Weighted with DS Boundary= 1
Downstream Boundary Weight= 0.5
Weight of XSs Associated with DS Boundary= 0.5
Sediment Output Level= 4
Mass or Volume Output= 0
Output Increment Type= 1
Profile and TS Output Increment= 10
XS Output Flag= 0
XS Output Increment= 10
Disregard all LS=0
Disregard all Conn=0
Disregard all Breaches=0
Disregard all Pumps=0

--- Harriet Creek Tributary 8.f01 (steady flow) ---

Flow Title=Multiple
Number of Profiles=7
Profile Names=10-year,25-year,50-year,1pct_min,100-year,1pct_plu,500-year
River Rch & RM= Harriet Creek Tr,Reach-1,3076
     373     496     595     355     708    1410    1000
River Rch & RM= Harriet Creek Tr,Reach-1,1806
     462     624     756     455     907    1810    1310
Boundary for River Rch & Prof#=Harriet Creek Tr,Reach-1,1
Up Type=0
Dn Type=3
Dn Slope=0.005
Boundary for River Rch & Prof#=Harriet Creek Tr,Reach-1,2
Up Type=0
Dn Type=3
Dn Slope=0.005
Boundary for River Rch & Prof#=Harriet Creek Tr,Reach-1,3
Up Type=0
Dn Type=3
Dn Slope=0.005
Boundary for River Rch & Prof#=Harriet Creek Tr,Reach-1,4
Up Type=0
Dn Type=3
Dn Slope=0.005
Boundary for River Rch & Prof#=Harriet Creek Tr,Reach-1,5
Up Type=0
Dn Type=3
Dn Slope=0.005
Boundary for River Rch & Prof#=Harriet Creek Tr,Reach-1,6
Up Type=0
Dn Type=3
Dn Slope=0.005
Boundary for River Rch & Prof#=Harriet Creek Tr,Reach-1,7
Up Type=0
Dn Type=3
Dn Slope=0.005

--- Harriet Creek Tributary 8.g01 (geometry) ---

Geom Title=Existing Conditions

River Reach=Harriet Creek Tr,Reach-1
Reach XY= 30
      2311529.00      7077210.00      2311722.98      7077068.18
      2311812.51      7077027.05      2311876.67      7076904.03
      2311882.52      7076811.28      2311922.62      7076768.00
      2312034.96      7076712.33      2312127.42      7076706.17
      2312380.58      7076563.83      2312473.03      7076557.65
      2312534.97      7076512.35      2312627.42      7076506.18
      2312735.08      7076451.87      2312812.58      7076376.80
      2312831.08      7076215.86      2312923.46      7076112.42
      2312934.52      7076007.57      2313075.39      7075858.50
      2313081.36      7075765.98      2313127.77      7075699.49
      2313134.70      7075557.61      2313184.52      7075465.28
      2313273.82      7075454.86      2313284.57      7075357.64
      2313375.53      7075258.50      2313376.63      7075165.89
      2313338.13      7075103.26      2313465.79      7074973.63
      2313535.07      7074951.89      2313629.00      7074860.00

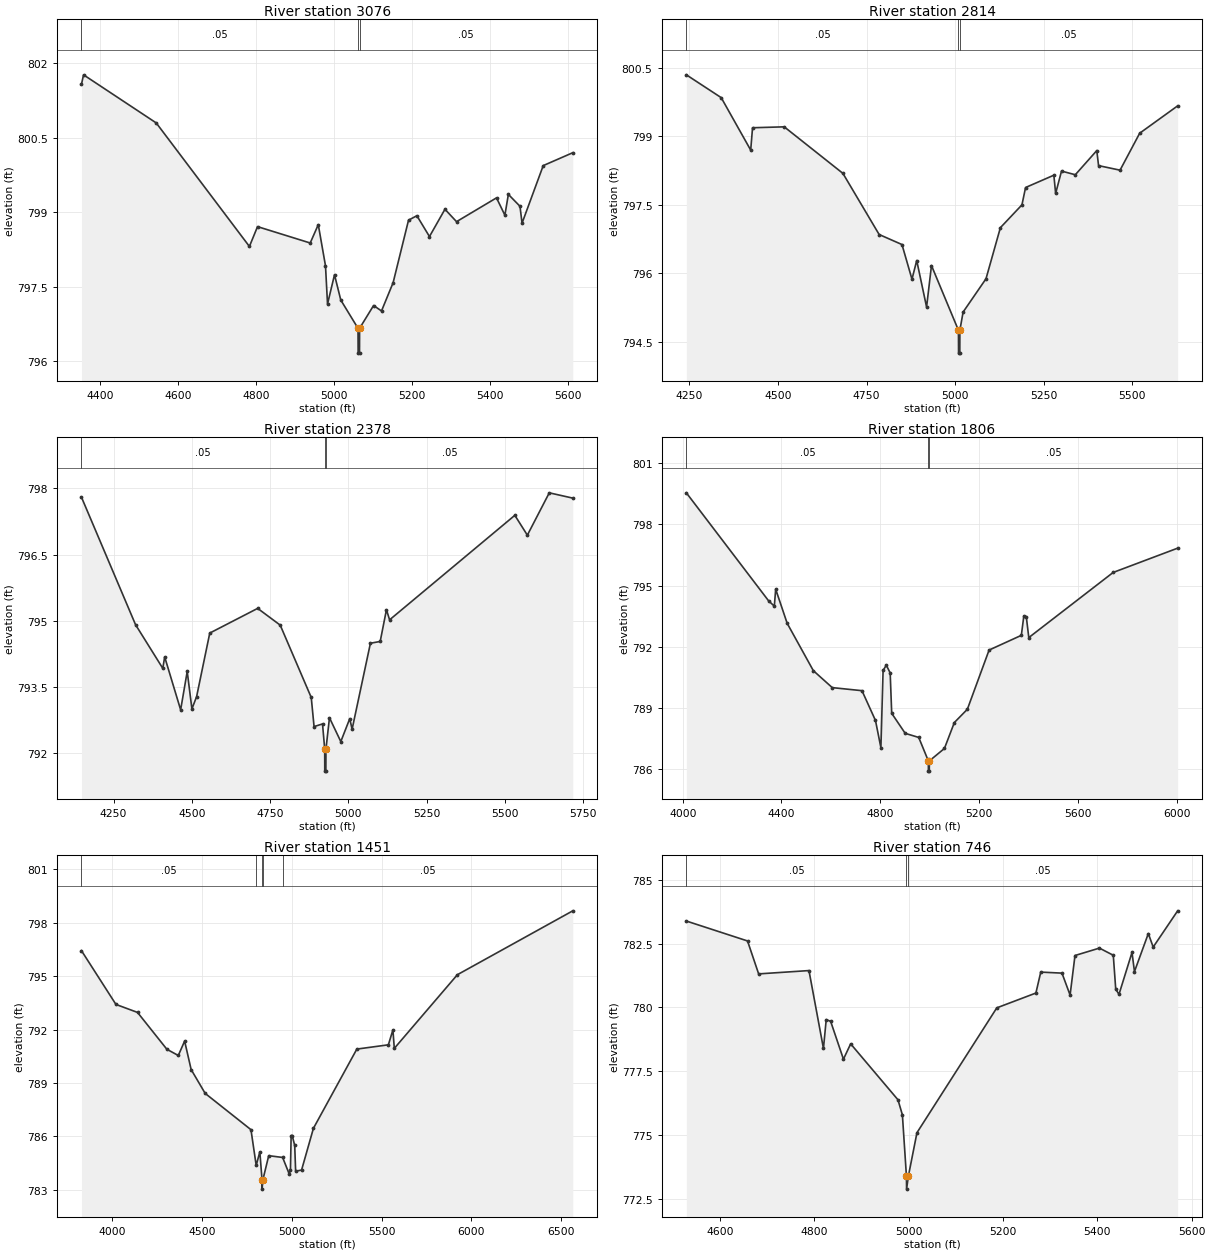
Type RM Length L Ch R = 1,3076,262,262,262
BEGIN DESCRIPTION:
Harriet Creek Tributary 5.0
END DESCRIPTION:
XS GIS Cut Line= 3
      2312054.19      7077504.55      2311851.01      7076782.13
      2311376.92      7076595.89
#Sta/Elev= 30
  4353.1  801.58  4358.4  801.77  4544.8  800.80  4783.7  798.31  4804.5  798.71
  4939.6  798.38  4960.3  798.75  4978.8  797.92  4984.0  797.15  5001.9  797.74
  5018.0  797.23  5062.2  796.66  5062.5  796.16  5066.0  796.16  5066.2  796.66
  5102.1  797.12  5122.4  797.01  5152.2  797.58  5191.7  798.84  5213.1  798.93
  5245.4  798.51  5285.1  799.06  5314.8  798.81  5417.3  799.29  5438.8  798.94
  5447.7  799.36  5477.5  799.12  5482.8  798.78  5537.1  799.94  5612.9  800.20
#Mann=3,-1,0
  4353.1    0.05       0  5062.2   0.035       0  5066.2    0.05       0
Bank Sta=5062.2,5066.2
Exp/Cntr=0.3,0.1

Type RM Length L Ch R = 1,2814,436,436,436
BEGIN DESCRIPTION:
Harriet Creek Tributary 4.0
END DESCRIPTION:
XS GIS Cut Line= 3
      2312217.89      7077448.20      2312025.98      7076663.60
      2311455.92      7076567.65
#Sta/Elev= 30
  4241.8  800.35  4340.1  799.85  4423.3  798.70  4428.5  799.19  4517.9  799.21
  4683.4  798.19  4785.6  796.85  4850.0  796.63  4878.2  795.87  4891.6  796.28
  4919.4  795.26  4933.2  796.17  5009.3  794.75  5009.6  794.25  5013.1  794.25
  5013.3  794.75  5022.4  795.15  5087.0  795.88  5127.6  797.00  5188.4  797.50
  5198.6  797.88  5278.4  798.15  5283.4  797.75  5300.0  798.24  5338.9  798.16
  5399.5  798.69  5404.5  798.36  5465.1  798.26  5520.5  799.07  5627.6  799.67
#Mann=3,-1,0
  4241.8    0.05       0  5009.3   0.033       0  5013.3    0.05       0
Bank Sta=5009.3,5013.3
Exp/Cntr=0.3,0.1

Type RM Length L Ch R = 1,2378,572,572,572
BEGIN DESCRIPTION:
Harriet Creek Tributary 3.5
END DESCRIPTION:
XS GIS Cut Line= 3
      2312900.83      7077267.53      2312381.56      7076494.28
      2311743.91      7076499.92
#Sta/Elev= 30
  4147.7  797.80  4320.4  794.91  4407.4  793.92  4413.4  794.18  4464.4  792.98
  4485.4  793.85  4500.4  793.00  4515.4  793.28  4557.4  794.72  4710.4  795.28
  4782.4  794.90  4881.5  793.26  4890.5  792.60  4917.5  792.66  4924.5  792.09
  4924.7  791.59  4928.2  791.59  4928.5  792.09  4939.7  792.80  4975.9  792.26
  5004.5  792.78  5012.0  792.54  5070.5  794.49  5101.7  794.53  5121.7  795.25
  5131.7  795.02  5531.7  797.39  5571.7  796.94  5641.7  797.90  5716.8  797.78
#Mann=3,-1,0
  4147.7    0.05       0  4924.5   0.033       0  4928.5    0.05       0
Bank Sta=4924.5,4928.5
Exp/Cntr=0.3,0.1

Type RM Length L Ch R = 1,1806,355,355,355
BEGIN DESCRIPTION:
Harriet Creek Tributary 8 3.0
END DESCRIPTION:
XS GIS Cut Line= 3
      2313228.99      7077159.97      2312829.00      7076260.00
      2311829.04      7076360.00
#Sta/Elev= 30
  4014.8  799.54  4347.9  794.25  4371.1  793.99  4376.6  794.82  4423.1  793.15
  4529.1  790.83  4605.7  790.00  4726.1  789.85  4780.8  788.39  4802.7  787.06
  4811.6  790.84  4824.6  791.10  4840.3  790.72  4846.5  788.74  4901.2  787.76
  4955.9  787.56  4994.9  786.41  4995.2  785.91  4998.7  785.91  4998.9  786.41
  5060.0  787.02  5100.2  788.29  5152.9  788.94  5240.9  791.84  5371.5  792.56
  5381.6  793.51  5391.6  793.47  5401.7  792.45  5743.3  795.64  6004.6  796.83
#Mann=3,-1,0
  4014.8    0.05       0  4994.9   0.033       0  4998.9    0.05       0
Bank Sta=4994.9,4998.9
Exp/Cntr=0.3,0.1

Type RM Length L Ch R = 1,1451,705,705,705
BEGIN DESCRIPTION:
Harriet Creek Tributary 8 2.0
END DESCRIPTION:
XS GIS Cut Line= 3
      2313728.99      7076859.99      2312979.00      7075960.00
      2311478.97      7076410.01
#Sta/Elev= 30
  3827.9  796.43  4019.9  793.41  4140.3  792.96  4303.7  790.89  4367.4  790.54
  4402.6  791.35  4439.0  789.75  4517.1  788.41  4772.3  786.37  4801.5  784.36
  4821.7  785.13  4834.1  783.53  4834.3  783.03  4838.1  783.53  4871.2  784.91
  4948.7  784.81  4985.8  783.87  4992.3  784.13  4996.2  786.04  5002.0  786.04
  5016.0  785.49  5021.2  784.04  5054.2  784.10  5120.4  786.45  5362.2  790.90
  5538.0  791.14  5563.2  791.98  5571.0  790.94  5922.5  795.08  6565.5  798.67
#Mann=5,-1,0
  3827.9    0.05       0  4801.5    0.12       0  4834.1   0.033       0
  4838.1    0.12       0  4948.7    0.05       0
Bank Sta=4834.1,4838.1
Exp/Cntr=0.3,0.1

Type RM Length L Ch R = 1,746,492,492,492
BEGIN DESCRIPTION:
Harriet Creek Tributary 8 1.0
END DESCRIPTION:
XS GIS Cut Line= 3
      2313528.99      7075809.98      2313279.00      7075410.00
      2312728.97      7075560.01
#Sta/Elev= 30
  4528.6  783.38  4658.3  782.60  4681.9  781.31  4788.6  781.44  4819.3  778.39
  4825.2  779.52  4834.6  779.45  4861.7  777.97  4877.0  778.57  4977.3  776.38
  4986.7  775.79  4995.3  773.38  4995.6  772.88  4999.3  773.38  5017.6  775.09
  5186.9  779.98  5269.8  780.56  5280.1  781.38  5325.1  781.34  5342.3  780.48
  5352.7  782.03  5404.5  782.32  5433.9  782.04  5439.1  780.71  5446.0  780.51
  5473.6  782.15  5478.8  781.40  5508.2  782.89  5518.5  782.36  5570.4  783.78
#Mann=3,-1,0
  4528.6    0.05       0  4995.3   0.033       0  4999.3    0.05       0
Bank Sta=4995.3,4999.3
Exp/Cntr=0.3,0.1

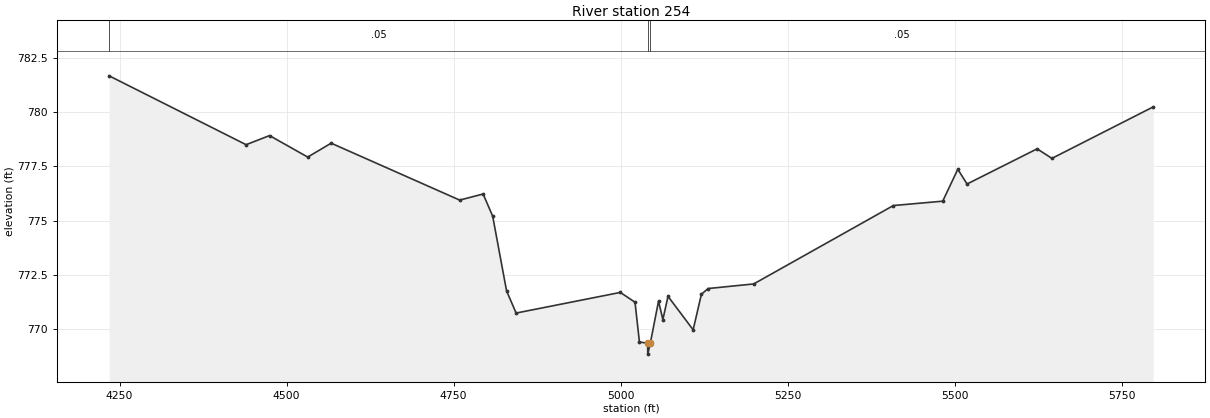
Type RM Length L Ch R = 1,254,0,0,0
BEGIN DESCRIPTION:
Harriet Creek Tributary 8 0.5
END DESCRIPTION:
XS GIS Cut Line= 4
      2313926.99      7075590.89      2313379.87      7074947.67
      2313048.46      7075024.15      2312873.96      7075359.41
#Sta/Elev= 30
  4234.4  781.67  4439.4  778.50  4474.5  778.92  4531.6  777.93  4566.7  778.57
  4759.0  775.95  4794.1  776.23  4808.4  775.21  4829.2  771.77  4843.5  770.75
  4999.4  771.70  5021.4  771.25  5028.0  769.42  5040.3  769.36  5040.5  768.86
  5044.3  769.36  5056.6  771.30  5063.1  770.45  5070.8  771.52  5108.4  769.98
  5120.8  771.62  5131.0  771.88  5199.0  772.09  5408.1  775.70  5481.9  775.90
  5504.5  777.37  5518.3  776.69  5623.2  778.31  5645.3  777.87  5796.9  780.24
#Mann=3,-1,0
  4234.4    0.05       0  5040.3   0.033       0  5044.3    0.05       0
Bank Sta=5040.3,5044.3
Exp/Cntr=0.3,0.1

Chan Stop Cuts=-1