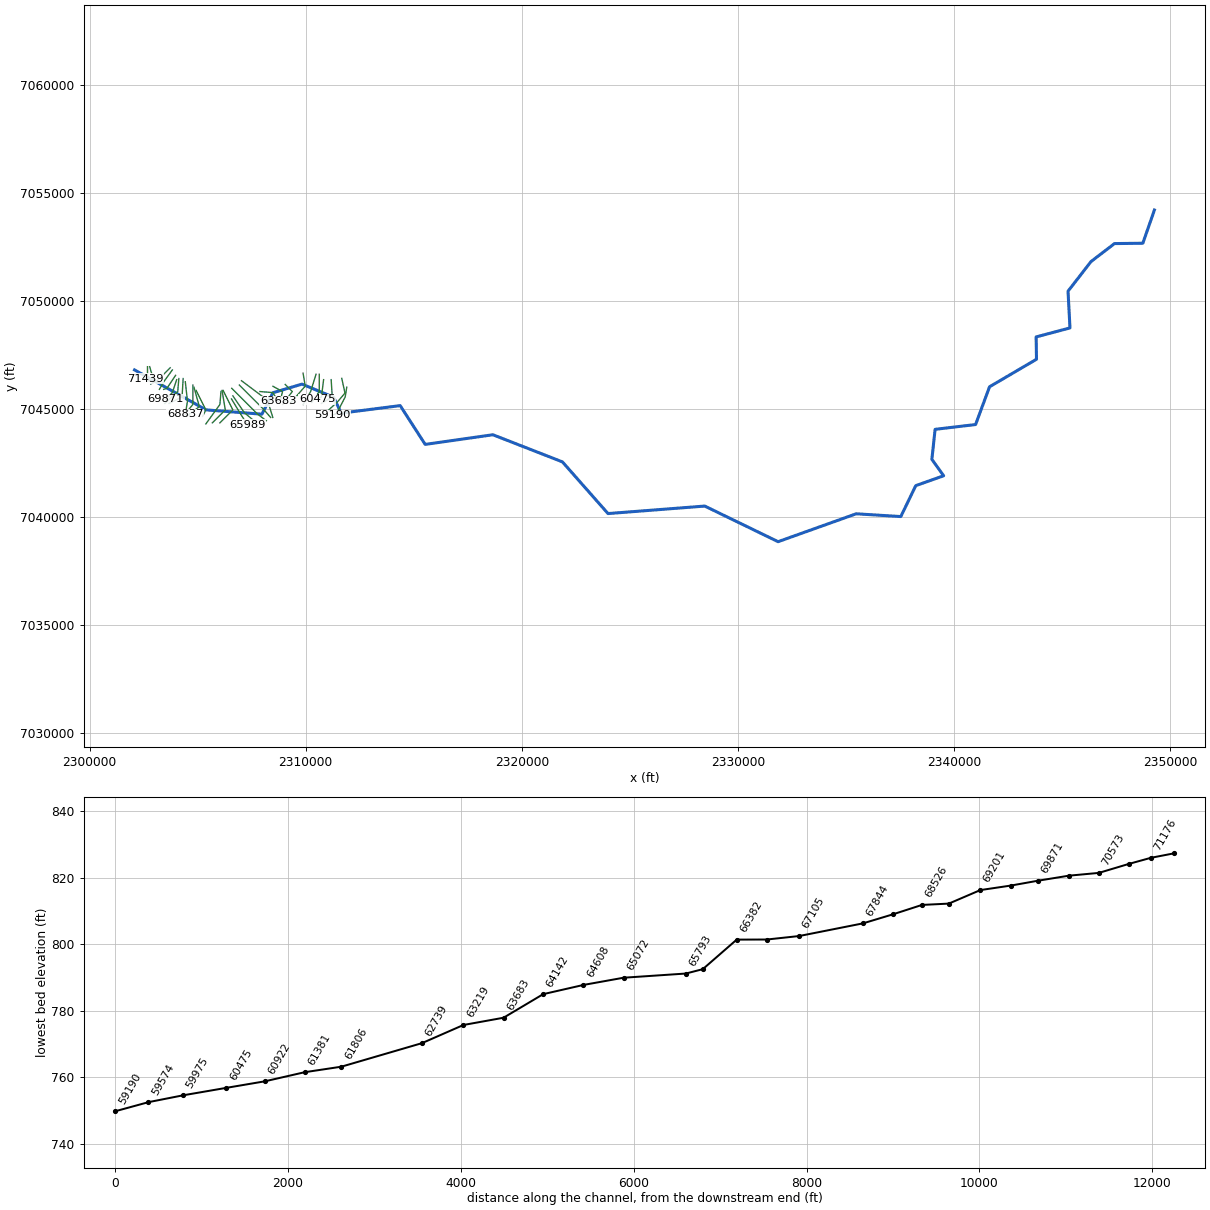
--- Henrietta Creek.prj (project) ---

Proj Title=Henrietta Creek Base Level Engineering
Current Plan=p01
Default Exp/Contr=0.3,0.1
English Units
Geom File=g01
Flow File=f01
Plan File=p01
BEGIN DESCRIPTION:
Henrietta Creek
END DESCRIPTION:

--- Henrietta Creek.p01 (plan) ---

Plan Title=Multiple Run
Short Identifier=Multiple
Geom File=g01
Flow File=f01
Subcritical Flow
K Sum by GR= 0
Std Step Tol= 0.01
Critical Tol= 0.01
Num of Std Step Trials= 20
Max Error Tol= 0.3
Flow Tol Ratio= 0.001
Split Flow NTrial= 30
Split Flow Tol= 0.02
Split Flow Ratio= 0.02
Log Output Level= 0
Friction Slope Method= 0
Unsteady Friction Slope Method= 2
Unsteady Bridges Friction Slope Method= 1
Parabolic Critical Depth
Global Vel Dist=  1 , 1 , 1
Global Log Level= 0
CheckData=True
Encroach Param= -1, 0, 0, 0
BEGIN DESCRIPTION:
Multiple Run
END DESCRIPTION:

--- Henrietta Creek.f01 (steady flow) ---

Flow Title=Multiple
Number of Profiles=7
Profile Names=10-year,25-year,50-year,1pct_min,100-year,1pct_plu,500-year
River Rch & RM= Henrietta Creek,Reach-1,71439
     432     577     692     413     823    1640    1160
River Rch & RM= Henrietta Creek,Reach-1,70225
     688     945    1160     700    1400    2790    2040
River Rch & RM= Henrietta Creek,Reach-1,65072
     757    1040    1280     778    1550    3100    2280
River Rch & RM= Henrietta Creek,Reach-1,61806
    1200    1700    2130    1310    2620    5220    3970
River Rch & RM= Henrietta Creek,Reach-1,58134
    1900    2750    3490    2180    4350    8690    6800
River Rch & RM= Henrietta Creek,Reach-1,57223
    2240    3260    4140    2600    5180   10300    8130
River Rch & RM= Henrietta Creek,Reach-1,52777
    2370    3450    4390    2760    5500   11000    8630
River Rch & RM= Henrietta Creek,Reach-1,49489
    3000    4400    5640    3560    7100   14200   11300
River Rch & RM= Henrietta Creek,Reach-1,47204
    3070    4520    5790    3660    7300   14600   11600
River Rch & RM= Henrietta Creek,Reach-1,45365
    3200    4720    6050    3820    7630   15200   12100
River Rch & RM= Henrietta Creek,Reach-1,42742
    3220    4740    6070    3840    7660   15300   12200
River Rch & RM= Henrietta Creek,Reach-1,41625
    5030    7490    9670    6150   12300   24500   19800
River Rch & RM= Henrietta Creek,Reach-1,37230
    5220    7770   10000    6390   12800   25400   20600
River Rch & RM= Henrietta Creek,Reach-1,35090
    5420    8080   10500    6660   13300   26500   21500
River Rch & RM= Henrietta Creek,Reach-1,32875
    5450    8130   10500    6690   13300   26600   21600
River Rch & RM= Henrietta Creek,Reach-1,31527
    6250    9360   12100    7740   15400   30800   25100
River Rch & RM= Henrietta Creek,Reach-1,28445
    6210    9290   12000    7680   15300   30600   24800
River Rch & RM= Henrietta Creek,Reach-1,27338
    6370    9540   12400    7900   15800   31500   25600
River Rch & RM= Henrietta Creek,Reach-1,26255
    6450    9660   12500    8000   16000   31800   25900
River Rch & RM= Henrietta Creek,Reach-1,26067
    6420    9600   12400    7940   15800   31600   25700
River Rch & RM= Henrietta Creek,Reach-1,22384
    6830   10200   13300    8480   16900   33800   27500
River Rch & RM= Henrietta Creek,Reach-1,19607
    7060   10600   13700    8770   17500   34900   28400
River Rch & RM= Henrietta Creek,Reach-1,14069
    7780   11700   15100    9650   19300   38400   31200
River Rch & RM= Henrietta Creek,Reach-1,9587
    7810   11700   15200    9690   19300   38600   31400
River Rch & RM= Henrietta Creek,Reach-1,7409
    6200    9220   11900    7580   15100   30200   24500
River Rch & RM= Henrietta Creek,Reach-1,5244
    6250    9290   12000    7640   15200   30400   24700
River Rch & RM= Henrietta Creek,Reach-1,1861
    6300    9370   12100    7710   15400   30700   24900
River Rch & RM= Henrietta Creek,Reach-1,1203
    6310    9380   12100    7710   15400   30700   24900
Boundary for River Rch & Prof#=Henrietta Creek,Reach-1,1
Up Type=0
Dn Type=3
Dn Slope=0.005
Boundary for River Rch & Prof#=Henrietta Creek,Reach-1,2
Up Type=0
Dn Type=3
Dn Slope=0.005
Boundary for River Rch & Prof#=Henrietta Creek,Reach-1,3
Up Type=0
Dn Type=3
Dn Slope=0.005
Boundary for River Rch & Prof#=Henrietta Creek,Reach-1,4
Up Type=0
Dn Type=3
Dn Slope=0.005
Boundary for River Rch & Prof#=Henrietta Creek,Reach-1,5
Up Type=0
Dn Type=3
Dn Slope=0.005
Boundary for River Rch & Prof#=Henrietta Creek,Reach-1,6
Up Type=0
Dn Type=3
Dn Slope=0.005
Boundary for River Rch & Prof#=Henrietta Creek,Reach-1,7
Up Type=0
Dn Type=3
Dn Slope=0.005

--- Henrietta Creek.g01 (geometry) ---

Geom Title=Existing Conditions

River Reach=Henrietta Creek,Reach-1
Reach XY= 30
      2302079.00      7046810.00      2305394.22      7044960.52
      2307973.35      7044761.97      2308484.62      7045754.38
      2309828.91      7046152.71      2311288.83      7045549.53
      2311645.04      7044810.17      2314373.35      7045158.03
      2315530.45      7043363.50      2318663.99      7043809.69
      2321881.30      7042554.17      2323990.95      7040161.92
      2328468.56      7040508.96      2331863.04      7038860.96
      2335475.68      7040151.96      2337542.32      7040023.37
      2338234.25      7041454.56      2339525.25      7041911.55
      2338979.55      7042670.64      2339129.00      7044060.00
      2341003.03      7044282.65      2341648.78      7046030.09
      2343820.94      7047303.68      2343805.26      7048336.89
      2345371.00      7048753.61      2345280.58      7050453.95
      2346342.37      7051823.32      2347430.63      7052656.87
      2348742.74      7052673.20      2349279.00      7054210.00

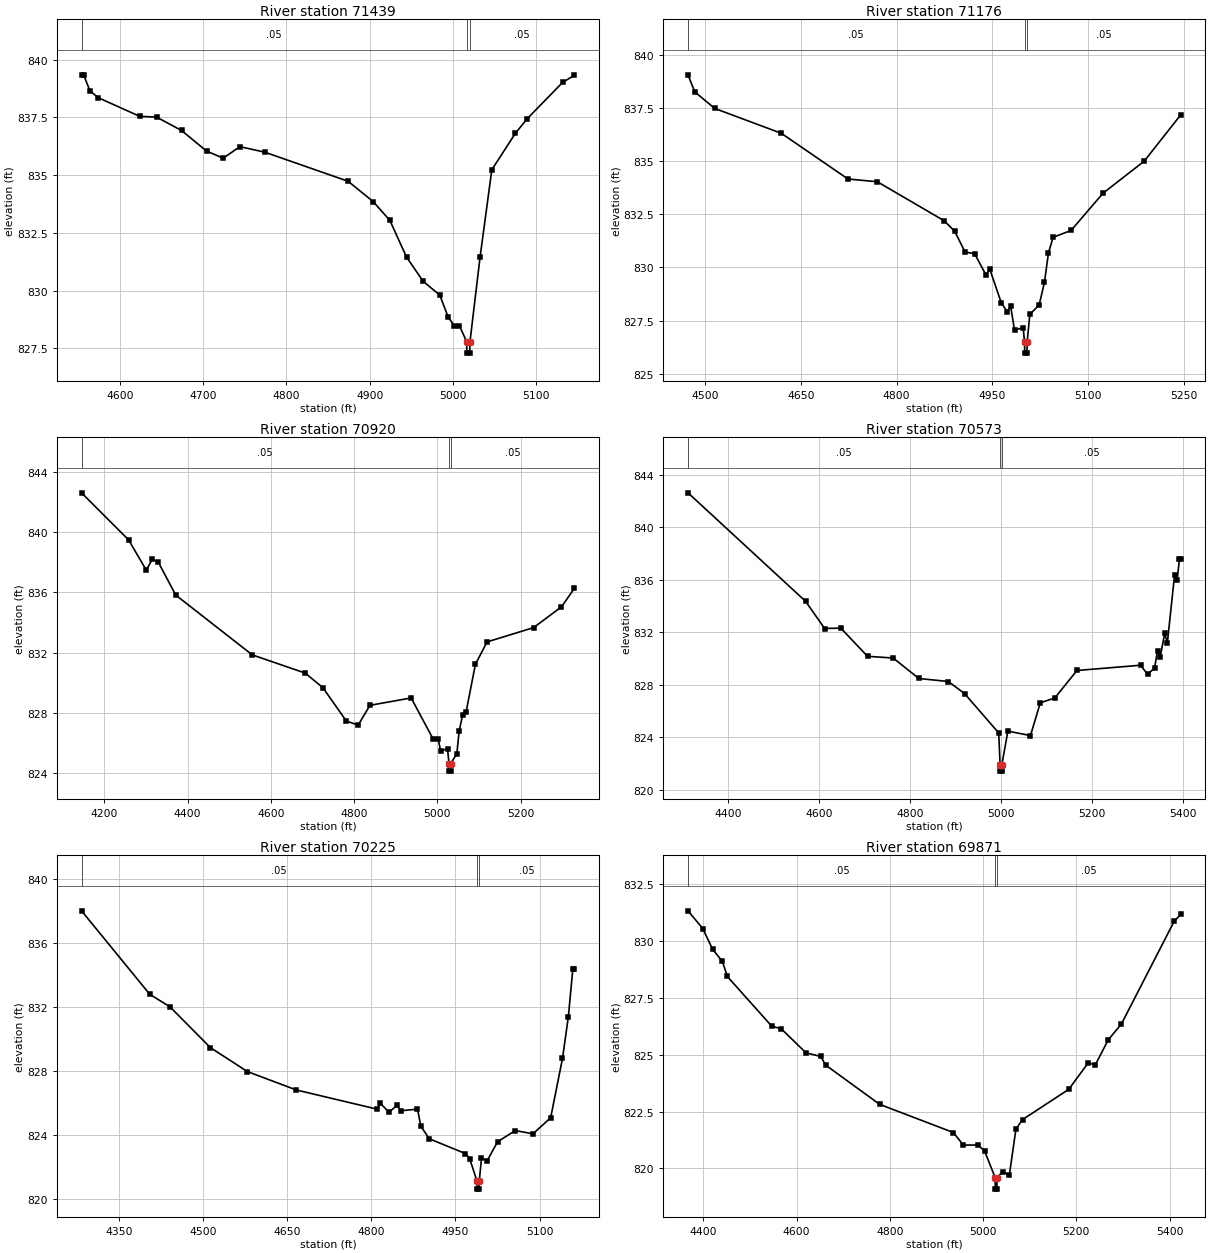
Type RM Length L Ch R = 1,71439,263,263,263
BEGIN DESCRIPTION:
Henrietta Creek 123.0
END DESCRIPTION:
XS GIS Cut Line= 3
      2302679.00      7046960.01      2302679.00      7046510.00
      2302579.02      7046410.02
#Sta/Elev= 30
  4554.1  839.34  4556.6  839.34  4564.1  838.65  4574.1  838.35  4624.1  837.54
  4644.1  837.51  4674.1  836.93  4704.1  836.04  4724.1  835.73  4744.1  836.23
  4774.1  835.99  4874.1  834.73  4904.1  833.85  4924.1  833.04  4944.1  831.45
  4964.1  830.40  4984.1  829.80  4994.1  828.85  5001.6  828.47  5007.6  828.47
  5016.3  827.79  5016.5  827.29  5020.0  827.29  5020.3  827.79  5032.4  831.45
  5046.5  835.23  5074.8  836.81  5089.0  837.44  5131.4  839.01  5145.5  839.32
#Mann=3,-1,0
  4554.1    0.05       0  5016.3   0.033       0  5020.3    0.05       0
Bank Sta=5016.3,5020.3
Exp/Cntr=0.3,0.1

Type RM Length L Ch R = 1,71176,256,256,256
BEGIN DESCRIPTION:
Henrietta Creek 122.0
END DESCRIPTION:
XS GIS Cut Line= 3
      2302778.99      7046960.04      2302929.00      7046460.00
      2302728.96      7046309.97
#Sta/Elev= 30
  4473.2  839.06  4483.7  838.26  4515.0  837.48  4619.4  836.31  4723.8  834.16
  4769.9  834.03  4874.3  832.20  4890.9  831.71  4907.4  830.72  4922.2  830.65
  4940.4  829.63  4945.7  829.95  4963.9  828.35  4973.5  827.91  4978.7  828.18
  4984.8  827.05  4998.4  827.17  5000.5  826.47  5000.8  825.97  5004.3  825.97
  5004.5  826.47  5008.8  827.79  5023.4  828.24  5031.7  829.30  5038.0  830.69
  5045.3  831.42  5073.4  831.74  5123.4  833.49  5188.0  835.00  5245.3  837.18
#Mann=3,-1,0
  4473.2    0.05       0  5000.5   0.033       0  5004.5    0.05       0
Bank Sta=5000.5,5004.5
Exp/Cntr=0.3,0.1

Type RM Length L Ch R = 1,70920,347,347,347
BEGIN DESCRIPTION:
Henrietta Creek 121.0
END DESCRIPTION:
XS GIS Cut Line= 3
      2303729.03      7046910.03      2303129.00      7046310.00
      2302828.99      7046159.99
#Sta/Elev= 30
  4145.0  842.61  4258.2  839.48  4300.6  837.47  4314.8  838.19  4328.9  838.03
  4371.3  835.82  4555.2  831.85  4682.4  830.64  4724.9  829.67  4781.4  827.45
  4809.7  827.19  4838.0  828.50  4937.0  828.99  4990.0  826.25  5002.0  826.28
  5007.6  825.47  5024.3  825.62  5027.9  824.63  5028.2  824.13  5031.7  824.13
  5031.9  824.63  5046.7  825.28  5052.3  826.80  5060.7  827.86  5069.0  828.06
  5091.4  831.23  5119.4  832.71  5231.2  833.66  5298.2  835.04  5329.0  836.26
#Mann=3,-1,0
  4145.0    0.05       0  5027.9   0.033       0  5031.9    0.05       0
Bank Sta=5027.9,5031.9
Exp/Cntr=0.3,0.1

Type RM Length L Ch R = 1,70573,348,348,348
BEGIN DESCRIPTION:
Henrietta Creek 120.0
END DESCRIPTION:
XS GIS Cut Line= 3
      2303829.02      7046810.03      2303429.00      7046260.00
      2303229.01      7045910.02
#Sta/Elev= 30
  4311.3  842.64  4569.8  834.37  4611.6  832.30  4647.1  832.33  4705.9  830.18
  4762.3  830.05  4818.7  828.49  4883.6  828.26  4919.2  827.34  4994.3  824.34
  4997.3  821.93  4997.6  821.43  5001.1  821.43  5001.3  821.93  5014.4  824.48
  5064.1  824.14  5085.7  826.64  5117.4  827.00  5166.3  829.10  5306.0  829.50
  5321.8  828.80  5336.9  829.30  5343.4  830.60  5349.2  830.13  5359.3  831.94
  5365.0  831.20  5380.8  836.37  5386.6  836.01  5391.6  837.61  5394.5  837.61
#Mann=3,-1,0
  4311.3    0.05       0  4997.3   0.033       0  5001.3    0.05       0
Bank Sta=4997.3,5001.3
Exp/Cntr=0.3,0.1

Type RM Length L Ch R = 1,70225,354,354,354
BEGIN DESCRIPTION:
Henrietta Creek 119.0
END DESCRIPTION:
XS GIS Cut Line= 3
      2303978.98      7046559.97      2303579.00      7045960.00
      2303428.99      7045910.00
#Sta/Elev= 30
  4282.8  837.99  4404.5  832.77  4440.5  831.99  4512.6  829.44  4578.7  827.94
  4665.9  826.79  4810.1  825.59  4816.1  825.95  4831.1  825.40  4846.1  825.83
  4852.1  825.49  4882.2  825.59  4888.2  824.52  4903.2  823.74  4967.8  822.81
  4975.3  822.49  4988.4  821.09  4988.6  820.59  4992.1  820.59  4992.4  821.09
  4996.4  822.52  5006.5  822.36  5025.0  823.55  5056.6  824.25  5088.2  824.05
  5119.8  825.05  5140.9  828.76  5151.4  831.37  5159.4  834.37  5162.0  834.37
#Mann=3,-1,0
  4282.8    0.05       0  4988.4   0.033       0  4992.4    0.05       0
Bank Sta=4988.4,4992.4
Exp/Cntr=0.3,0.1

Type RM Length L Ch R = 1,69871,314,314,314
BEGIN DESCRIPTION:
Henrietta Creek 118.0
END DESCRIPTION:
XS GIS Cut Line= 3
      2304029.00      7046359.99      2303829.00      7045760.00
      2303529.00      7045460.00
#Sta/Elev= 30
  4367.3  831.34  4398.9  830.56  4420.0  829.65  4441.1  829.11  4451.6  828.45
  4546.5  826.27  4567.6  826.14  4620.3  825.09  4651.9  824.93  4662.4  824.55
  4778.4  822.82  4936.5  821.58  4957.6  821.03  4989.2  821.03  5003.3  820.77
  5026.0  819.59  5026.3  819.09  5029.8  819.09  5030.0  819.59  5042.2  819.86
  5056.3  819.70  5070.5  821.73  5084.6  822.15  5183.6  823.48  5226.0  824.66
  5240.2  824.54  5268.4  825.66  5296.7  826.36  5409.9  830.88  5424.0  831.19
#Mann=3,-1,0
  4367.3    0.05       0  5026.0   0.033       0  5030.0    0.05       0
Bank Sta=5026,5030
Exp/Cntr=0.3,0.1

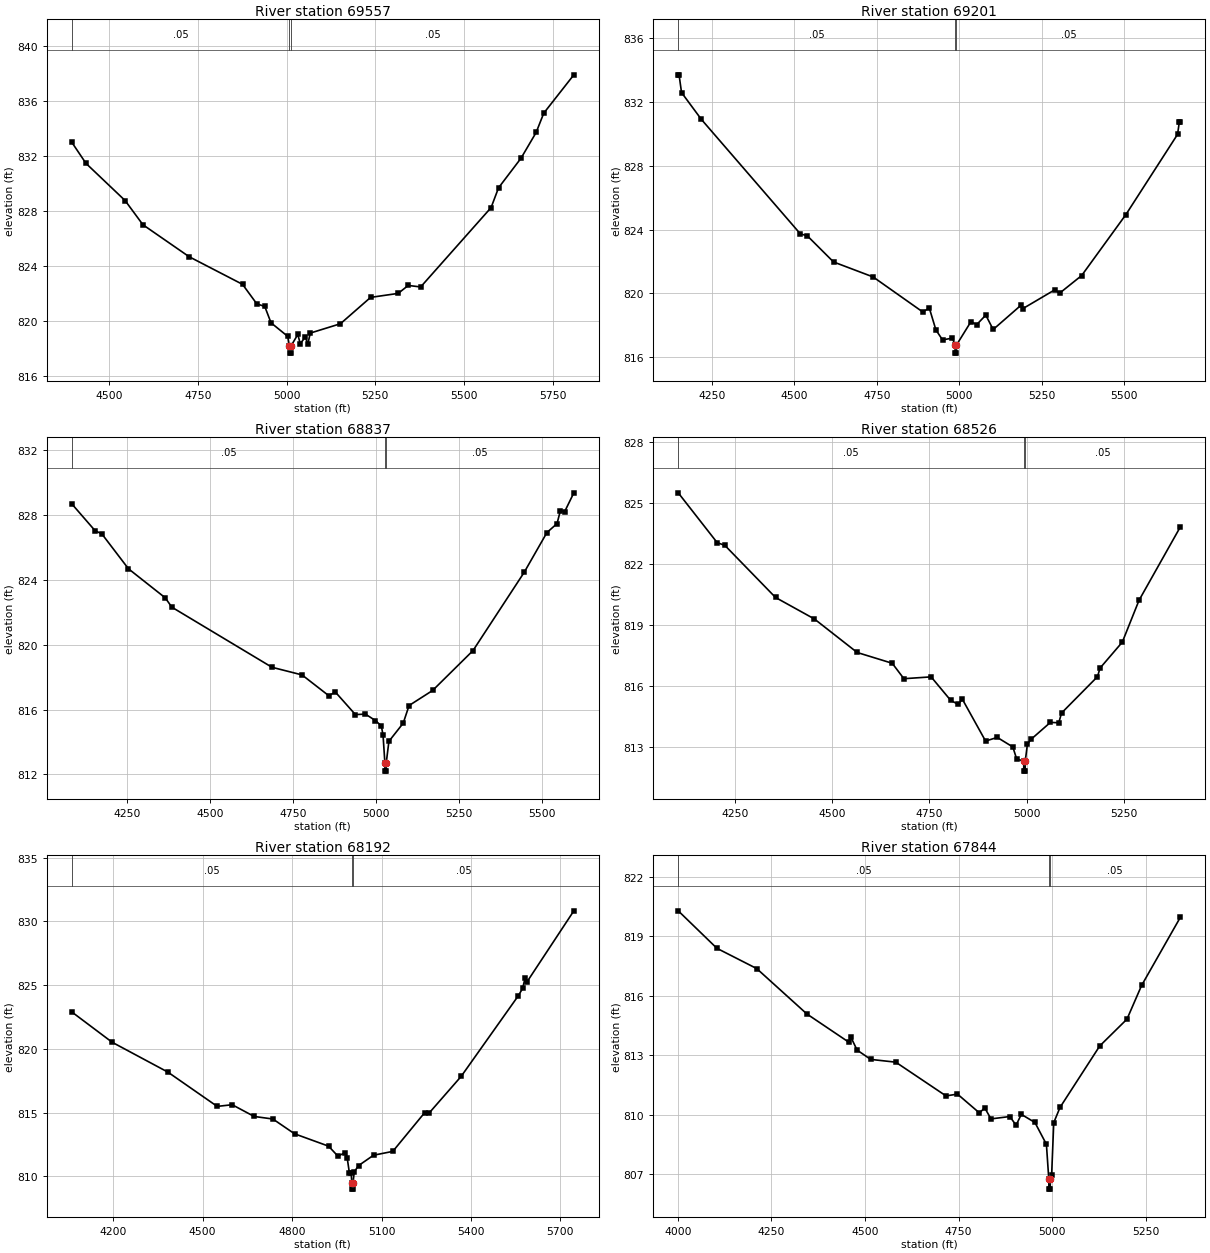
Type RM Length L Ch R = 1,69557,356,356,356
BEGIN DESCRIPTION:
Henrietta Creek 117.0
END DESCRIPTION:
XS GIS Cut Line= 3
      2304129.00      7046409.96      2304079.00      7045810.00
      2303478.99      7045259.99
#Sta/Elev= 30
  4394.0  832.99  4434.1  831.45  4544.5  828.74  4594.7  826.98  4725.1  824.65
  4875.6  822.64  4915.8  821.22  4938.3  821.03  4955.9  819.84  5003.1  818.85
  5007.9  818.13  5008.2  817.63  5011.7  817.63  5011.9  818.13  5031.5  818.99
  5038.3  818.32  5052.5  818.79  5059.9  818.31  5066.6  819.09  5151.7  819.77
  5236.8  821.69  5314.5  821.98  5342.9  822.56  5378.0  822.45  5576.6  828.23
  5597.6  829.67  5661.1  831.83  5703.6  833.70  5725.2  835.11  5810.0  837.90
#Mann=3,-1,0
  4394.0    0.05       0  5007.9   0.033       0  5011.9    0.05       0
Bank Sta=5007.9,5011.9
Exp/Cntr=0.3,0.1

Type RM Length L Ch R = 1,69201,364,364,364
BEGIN DESCRIPTION:
Henrietta Creek 116.0
END DESCRIPTION:
XS GIS Cut Line= 3
      2304329.00      7046409.99      2304279.00      7045560.00
      2303678.98      7045259.99
#Sta/Elev= 30
  4147.7  833.69  4150.2  833.69  4157.7  832.58  4217.8  830.90  4518.3  823.72
  4538.4  823.62  4618.5  821.97  4738.7  821.03  4889.0  818.84  4909.0  819.08
  4929.0  817.71  4949.1  817.09  4979.1  817.20  4987.1  816.76  4987.4  816.26
  4990.9  816.26  4991.1  816.76  5035.5  818.24  5052.3  818.04  5080.2  818.64
  5102.6  817.74  5186.4  819.25  5192.0  819.04  5289.8  820.23  5303.8  820.01
  5370.9  821.12  5505.1  824.94  5661.6  829.96  5667.2  830.76  5670.0  830.76
#Mann=3,-1,0
  4147.7    0.05       0  4987.1   0.033       0  4991.1    0.05       0
Bank Sta=4987.1,4991.1
Exp/Cntr=0.3,0.1

Type RM Length L Ch R = 1,68837,311,311,311
BEGIN DESCRIPTION:
Henrietta Creek 115.0
END DESCRIPTION:
XS GIS Cut Line= 3
      2304429.00      7046259.98      2304529.00      7045360.00
      2304429.00      7044760.00
#Sta/Elev= 30
  4083.2  828.70  4153.6  827.04  4173.7  826.85  4254.2  824.69  4364.9  822.90
  4385.0  822.32  4686.9  818.61  4777.4  818.14  4857.9  816.86  4878.0  817.08
  4938.4  815.69  4968.6  815.72  4998.9  815.32  5016.6  814.99  5021.7  814.42
  5027.3  812.70  5027.5  812.20  5031.0  812.20  5031.3  812.70  5039.4  814.04
  5082.5  815.16  5100.2  816.25  5171.2  817.18  5292.9  819.64  5447.5  824.48
  5515.9  826.93  5546.3  827.48  5556.4  828.28  5569.1  828.21  5597.0  829.38
#Mann=3,-1,0
  4083.2    0.05       0  5027.3   0.033       0  5031.3    0.05       0
Bank Sta=5027.3,5031.3
Exp/Cntr=0.3,0.1

Type RM Length L Ch R = 1,68526,334,334,334
BEGIN DESCRIPTION:
Henrietta Creek 114.0
END DESCRIPTION:
XS GIS Cut Line= 3
      2304779.00      7046109.95      2304779.00      7045210.00
      2304528.98      7044909.97
#Sta/Elev= 30
  4104.7  825.50  4204.7  823.05  4224.7  822.91  4354.7  820.35  4454.7  819.29
  4564.7  817.64  4654.7  817.11  4684.7  816.35  4754.7  816.44  4804.7  815.29
  4824.7  815.08  4834.7  815.35  4894.7  813.28  4924.7  813.46  4964.7  812.99
  4974.7  812.39  4992.7  812.30  4992.9  811.80  4996.4  811.80  4996.7  812.30
  5002.2  813.13  5011.8  813.37  5061.3  814.20  5082.8  814.18  5089.9  814.66
  5182.3  816.45  5188.8  816.87  5246.1  818.15  5289.1  820.21  5395.2  823.82
#Mann=3,-1,0
  4104.7    0.05       0  4992.7   0.033       0  4996.7    0.05       0
Bank Sta=4992.7,4996.7
Exp/Cntr=0.3,0.1

Type RM Length L Ch R = 1,68192,348,348,348
BEGIN DESCRIPTION:
Henrietta Creek 113.0
END DESCRIPTION:
XS GIS Cut Line= 3
      2304829.00      7046010.02      2305079.00      7045110.00
      2304479.00      7044660.00
#Sta/Elev= 30
  4060.9  822.89  4196.4  820.51  4383.2  818.17  4548.7  815.48  4599.0  815.61
  4672.7  814.69  4735.5  814.49  4808.2  813.33  4922.3  812.36  4953.5  811.58
  4977.9  811.85  4984.6  811.46  4992.4  810.22  4998.1  810.22  5000.3  809.49
  5000.5  808.99  5004.0  808.99  5004.3  809.49  5008.5  810.35  5023.1  810.84
  5073.1  811.65  5137.7  811.95  5245.0  815.00  5258.5  814.93  5366.9  817.83
  5558.5  824.15  5573.1  824.73  5581.5  825.55  5587.7  825.24  5745.0  830.82
#Mann=3,-1,0
  4060.9    0.05       0  5000.3   0.033       0  5004.3    0.05       0
Bank Sta=5000.3,5004.3
Exp/Cntr=0.3,0.1

Type RM Length L Ch R = 1,67844,739,739,739
BEGIN DESCRIPTION:
Henrietta Creek 112.0
END DESCRIPTION:
XS GIS Cut Line= 3
      2304929.02      7045859.96      2305379.00      7044960.00
      2305229.00      7044660.00
#Sta/Elev= 30
  4000.8  820.29  4104.2  818.40  4210.4  817.38  4344.6  815.09  4456.4  813.67
  4461.9  813.93  4478.7  813.27  4515.1  812.80  4582.1  812.66  4716.3  810.96
  4747.0  811.05  4805.7  810.10  4819.7  810.36  4836.5  809.80  4886.8  809.92
  4903.6  809.48  4917.5  810.03  4953.9  809.62  4984.6  808.52  4991.0  806.76
  4991.3  806.26  4994.8  806.26  4995.0  806.76  4998.6  806.99  5004.2  809.61
  5021.0  810.38  5127.2  813.48  5199.9  814.83  5239.0  816.53  5342.4  819.96
#Mann=3,-1,0
  4000.8    0.05       0  4991.0   0.033       0  4995.0    0.05       0
Bank Sta=4991,4995
Exp/Cntr=0.3,0.1

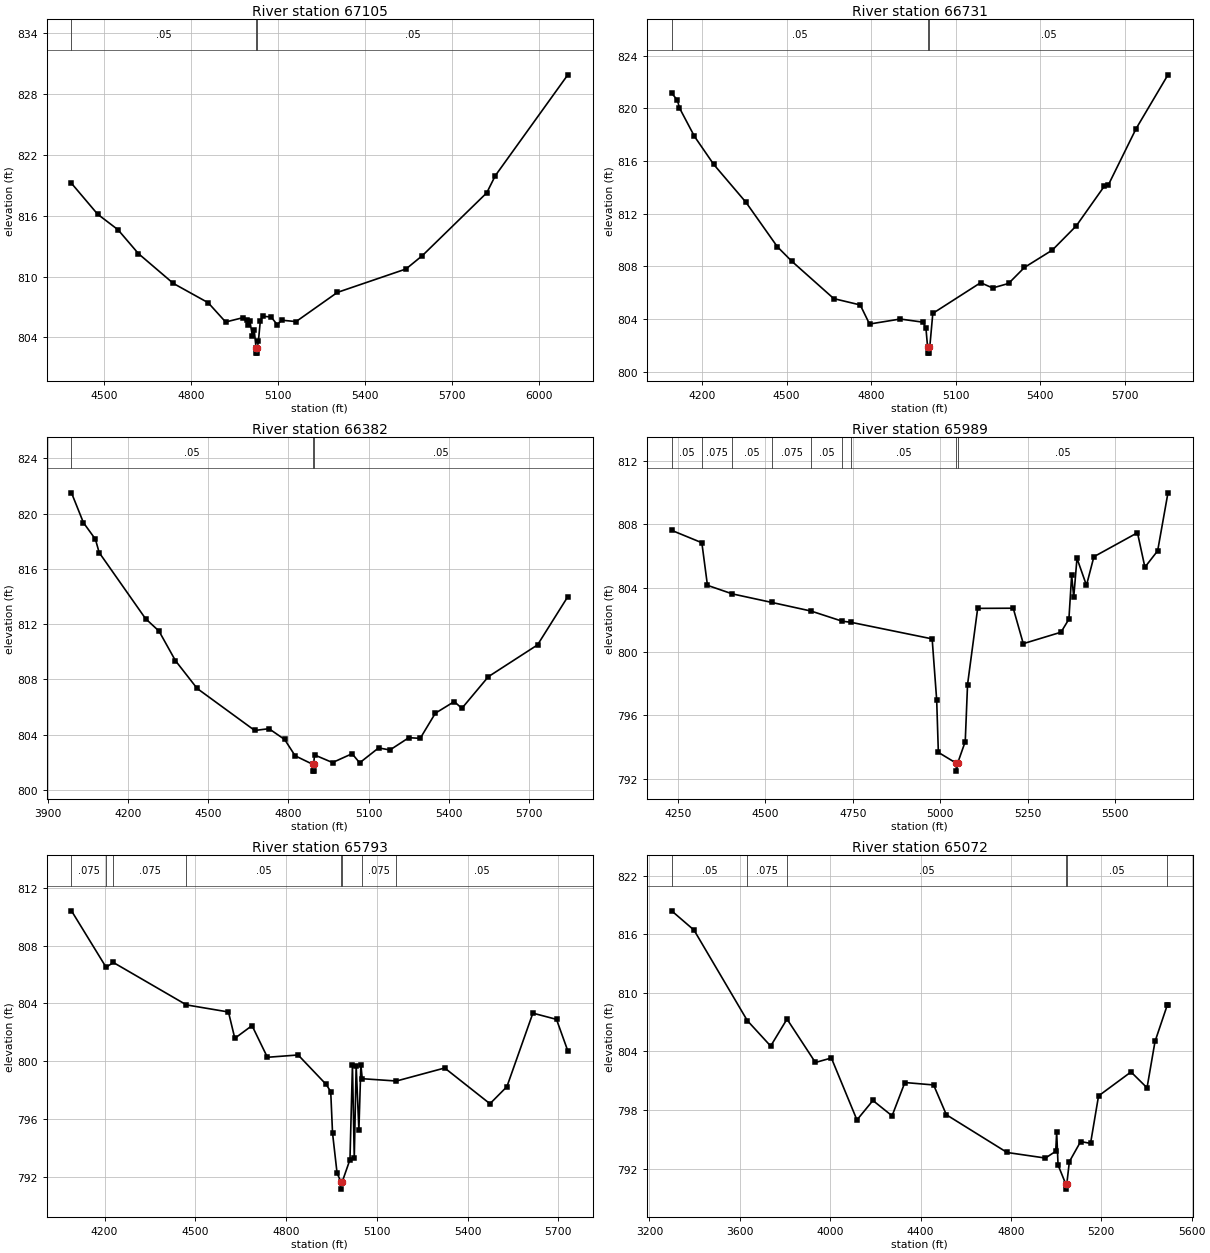
Type RM Length L Ch R = 1,67105,374,374,374
BEGIN DESCRIPTION:
Henrietta Creek 111.0
END DESCRIPTION:
XS GIS Cut Line= 3
      2306079.00      7045809.96      2306029.00      7045210.00
      2305379.01      7044310.01
#Sta/Elev= 30
  4386.2  819.20  4476.5  816.15  4546.7  814.62  4617.0  812.27  4737.4  809.33
  4857.8  807.42  4918.0  805.52  4978.2  805.95  4991.3  805.76  4995.6  805.26
  5001.8  805.57  5010.3  804.15  5016.5  804.72  5023.0  802.95  5023.3  802.45
  5026.8  802.45  5027.0  802.95  5031.2  803.67  5037.6  805.62  5045.9  806.08
  5074.6  806.02  5096.2  805.25  5110.9  805.70  5160.9  805.56  5303.5  808.44
  5540.2  810.75  5596.7  812.07  5818.7  818.26  5848.2  819.95  6098.4  829.90
#Mann=3,-1,0
  4386.2    0.05       0  5023.0   0.033       0  5027.0    0.05       0
Bank Sta=5023,5027
Exp/Cntr=0.3,0.1

Type RM Length L Ch R = 1,66731,349,349,349
BEGIN DESCRIPTION:
Henrietta Creek 110.0
END DESCRIPTION:
XS GIS Cut Line= 3
      2306129.00      7045860.00      2306279.00      7044960.00
      2305679.03      7044360.03
#Sta/Elev= 30
  4092.3  821.15  4112.6  820.62  4120.2  820.02  4173.4  817.86  4241.8  815.73
  4355.9  812.86  4467.4  809.48  4518.1  808.39  4667.6  805.54  4761.4  805.06
  4794.4  803.61  4903.3  803.99  4984.4  803.75  4994.6  803.28  5000.2  801.90
  5000.4  801.40  5003.9  801.40  5004.2  801.90  5008.3  801.90  5018.9  804.42
  5188.6  806.75  5231.0  806.35  5287.6  806.69  5344.1  807.91  5443.1  809.23
  5528.0  811.07  5627.0  814.07  5641.1  814.15  5740.1  818.45  5853.2  822.54
#Mann=3,-1,0
  4092.3    0.05       0  5000.2   0.033       0  5004.2    0.05       0
Bank Sta=5000.2,5004.2
Exp/Cntr=0.3,0.1

Type RM Length L Ch R = 1,66382,393,393,393
BEGIN DESCRIPTION:
Henrietta Creek 109.0
END DESCRIPTION:
XS GIS Cut Line= 3
      2306179.00      7045860.01      2306629.00      7044960.00
      2306028.98      7044359.98
#Sta/Elev= 30
  3989.5  821.50  4034.2  819.34  4079.0  818.14  4092.9  817.18  4266.2  812.40
  4316.5  811.50  4378.0  809.36  4459.1  807.35  4674.3  804.31  4727.4  804.44
  4786.1  803.66  4825.2  802.48  4890.3  801.87  4890.6  801.37  4894.1  801.37
  4894.3  801.87  4897.9  802.54  4965.0  801.99  5038.2  802.63  5066.4  801.97
  5137.2  803.05  5179.6  802.90  5250.3  803.79  5292.7  803.74  5349.3  805.56
  5420.0  806.40  5448.3  805.91  5547.3  808.20  5731.1  810.50  5844.3  813.99
#Mann=3,-1,0
  3989.5    0.05       0  4890.3   0.033       0  4894.3    0.05       0
Bank Sta=4890.3,4894.3
Exp/Cntr=0.3,0.1

Type RM Length L Ch R = 1,65989,196,196,196
BEGIN DESCRIPTION:
Henrietta Creek 108.0
END DESCRIPTION:
XS GIS Cut Line= 3
      2306566.07      7045467.67      2306959.01      7044814.62
      2307310.48      7044261.13
#Sta/Elev= 30
  4232.3  807.63  4318.6  806.85  4334.6  804.17  4405.9  803.63  4519.2  803.09
  4630.8  802.55  4719.9  801.91  4743.3  801.85  4976.5  800.80  4989.4  796.96
  4994.2  793.66  5045.3  792.98  5045.6  792.48  5049.3  792.98  5071.0  794.34
  5077.6  797.93  5106.5  802.72  5208.1  802.73  5236.8  800.50  5344.5  801.22
  5367.1  802.04  5375.0  804.81  5380.9  803.42  5390.2  805.87  5417.3  804.17
  5438.5  805.97  5563.0  807.48  5584.2  805.31  5620.6  806.34  5650.1  809.99
#Mann=9,-1,0
  4232.3    0.05       0  4318.6   0.075       0  4405.9    0.05       0
  4519.2   0.075       0  4630.8    0.05       0  4719.9   0.075       0
  4743.3    0.05       0  5045.3    0.05       0  5049.3    0.05       0
Bank Sta=5045.3,5049.3
Exp/Cntr=0.3,0.1

Type RM Length L Ch R = 1,65793,721,721,721
BEGIN DESCRIPTION:
Henrietta Creek 107.0
END DESCRIPTION:
XS GIS Cut Line= 3
      2306629.01      7045609.99      2307161.02      7044831.22
      2307695.08      7044382.95
#Sta/Elev= 30
  4090.8  810.40  4205.2  806.50  4229.2  806.83  4470.8  803.90  4609.6  803.41
  4630.6  801.59  4687.5  802.47  4738.3  800.28  4839.9  800.44  4932.7  798.40
  4947.6  797.91  4953.6  795.04  4968.6  792.27  4981.5  791.67  4981.7  791.17
  4985.5  791.67  5011.2  793.21  5019.4  799.76  5025.4  793.31  5031.7  799.70
  5040.7  795.25  5047.3  799.76  5051.8  798.80  5164.7  798.64  5324.3  799.54
  5473.9  797.07  5529.9  798.25  5615.7  803.33  5693.8  802.90  5731.2  800.72
#Mann=8,-1,0
  4090.8   0.075       0  4205.2    0.05       0  4229.2   0.075       0
  4470.8    0.05       0  4981.5    0.05       0  4985.5    0.05       0
  5051.8   0.075       0  5164.7    0.05       0
Bank Sta=4981.5,4985.5
Exp/Cntr=0.3,0.1

Type RM Length L Ch R = 1,65072,464,464,464
BEGIN DESCRIPTION:
Henrietta Creek 106.0
END DESCRIPTION:
XS GIS Cut Line= 3
      2306578.99      7045960.01      2307779.00      7044760.00
      2308179.02      7044459.98
#Sta/Elev= 30
  3298.0  818.39  3397.0  816.42  3633.2  807.15  3736.4  804.55  3808.7  807.31
  3934.4  802.87  4005.1  803.33  4118.3  796.99  4189.0  798.98  4273.8  797.41
  4330.4  800.82  4457.7  800.57  4514.2  797.52  4782.9  793.66  4952.6  793.09
  4998.2  793.78  5002.4  795.75  5008.6  792.38  5043.0  790.41  5043.3  789.91
  5047.1  790.41  5058.6  792.72  5108.6  794.78  5152.4  794.59  5187.8  799.45
  5331.5  801.90  5402.4  800.28  5437.8  805.02  5492.9  808.80  5495.1  808.80
#Mann=6,-1,0
  3298.0    0.05       0  3633.2   0.075       0  3808.7    0.05       0
  5043.0    0.05       0  5047.1    0.05       0  5492.9   0.075       0
Bank Sta=5043,5047.1
Exp/Cntr=0.3,0.1

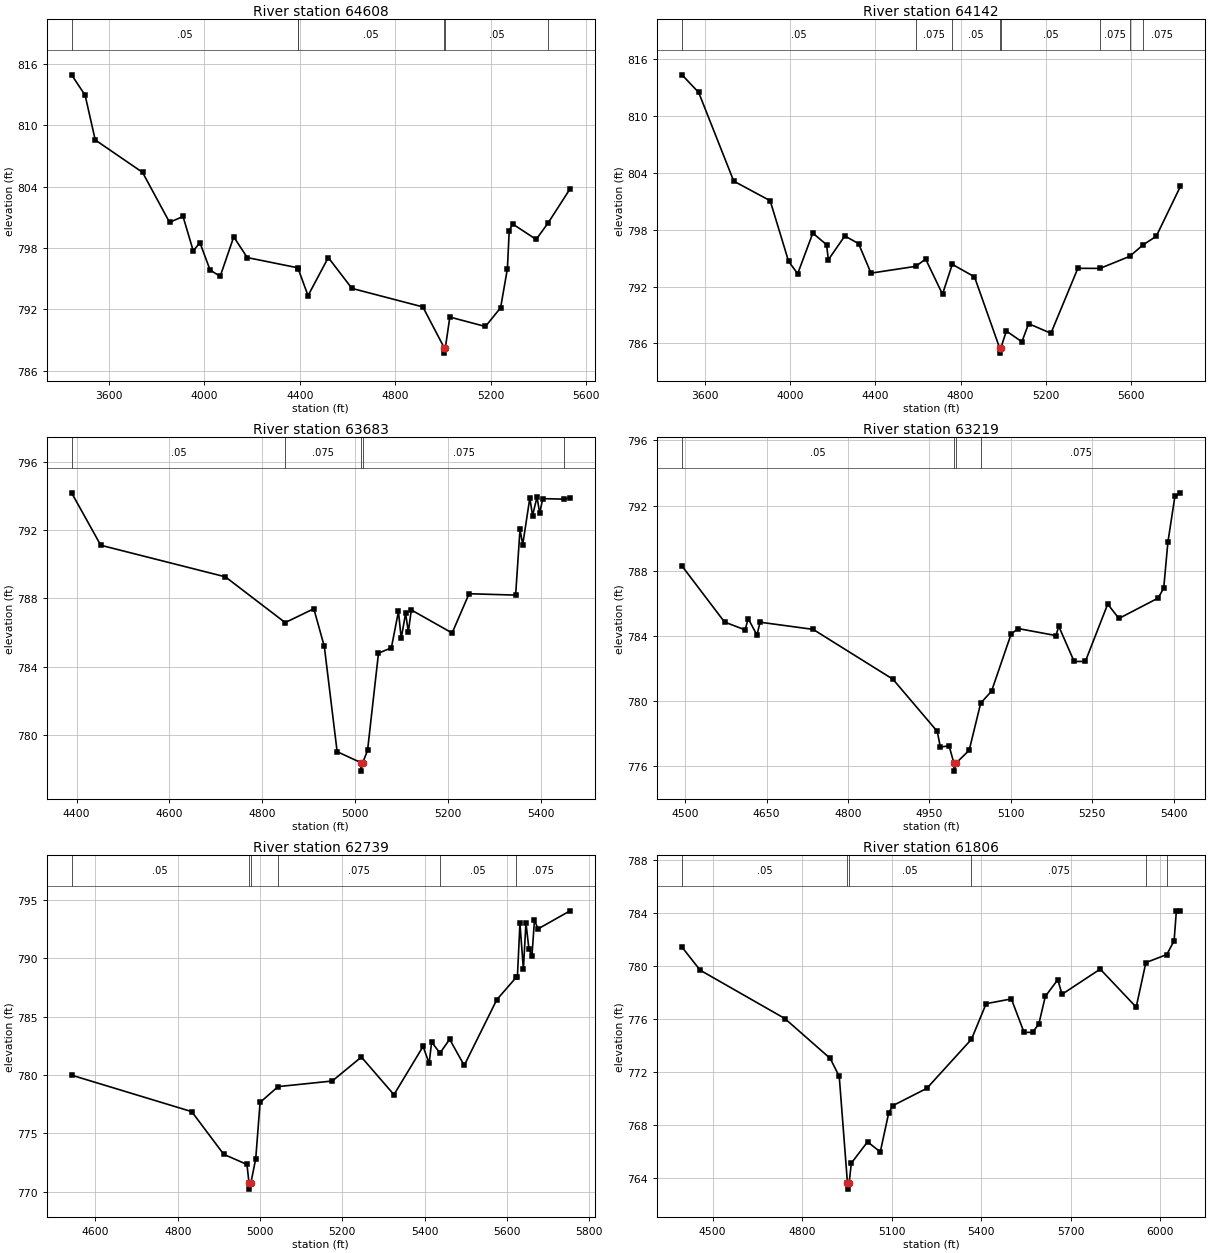
Type RM Length L Ch R = 1,64608,466,466,466
BEGIN DESCRIPTION:
Henrietta Creek 105.0
END DESCRIPTION:
XS GIS Cut Line= 3
      2306928.97      7046110.03      2308029.00      7045010.00
      2308379.01      7044609.99
#Sta/Elev= 30
  3444.9  814.91  3501.5  812.92  3543.9  808.55  3741.9  805.39  3855.1  800.51
  3911.6  801.08  3954.1  797.73  3982.3  798.52  4024.8  795.85  4067.2  795.24
  4123.8  799.09  4180.3  797.07  4392.2  796.07  4394.0  795.96  4434.9  793.35
  4519.7  797.07  4618.7  794.06  4915.7  792.25  5005.6  788.24  5005.9  787.74
  5009.7  788.24  5028.6  791.26  5177.6  790.34  5241.2  792.17  5269.7  795.99
  5277.2  799.68  5291.5  800.35  5390.2  798.84  5440.7  800.47  5532.1  803.78
#Mann=6,-1,0
  3444.9    0.05       0  4392.2   0.075       0  4394.0    0.05       0
  5005.6    0.05       0  5009.7    0.05       0  5440.7   0.075       0
Bank Sta=5005.6,5009.7
Exp/Cntr=0.3,0.1

Type RM Length L Ch R = 1,64142,459,459,459
BEGIN DESCRIPTION:
Henrietta Creek 104.0
END DESCRIPTION:
XS GIS Cut Line= 3
      2307028.98      7046310.02      2308229.00      7045410.00
      2308479.01      7044609.98
#Sta/Elev= 30
  3492.8  814.37  3571.0  812.51  3735.5  803.14  3906.4  801.07  3992.8  794.66
  4035.5  793.36  4106.4  797.65  4171.0  796.42  4179.3  794.83  4256.4  797.35
  4321.0  796.54  4379.3  793.42  4589.5  794.14  4635.5  794.91  4714.7  791.20
  4760.6  794.35  4864.7  793.03  4983.4  785.47  4983.8  784.97  4987.6  785.47
  5014.3  787.30  5087.1  786.17  5118.6  788.08  5223.3  787.07  5349.6  793.93
  5453.4  793.92  5592.3  795.19  5656.8  796.43  5717.3  797.31  5831.0  802.60
#Mann=8,-1,0
  3492.8    0.05       0  4589.5   0.075       0  4760.6    0.05       0
  4983.4   0.033       0  4987.6    0.05       0  5453.4   0.075       0
  5592.3    0.05       0  5656.8   0.075       0
Bank Sta=4983.4,4987.6
Exp/Cntr=0.3,0.1

Type RM Length L Ch R = 1,63683,464,464,464
BEGIN DESCRIPTION:
Henrietta Creek 103.0
END DESCRIPTION:
XS GIS Cut Line= 3
      2307878.96      7045810.00      2308479.00      7045760.00
      2308728.99      7045360.02
#Sta/Elev= 30
  4389.4  794.18  4452.2  791.11  4720.6  789.26  4849.5  786.58  4911.2  787.39
  4933.8  785.18  4961.4  779.02  5012.4  778.38  5012.7  777.88  5016.6  778.38
  5026.9  779.09  5050.5  784.79  5078.2  785.10  5093.5  787.23  5099.4  785.66
  5108.9  787.12  5114.8  786.04  5121.2  787.32  5209.1  785.97  5245.6  788.27
  5345.9  788.19  5355.3  792.04  5361.2  791.15  5376.5  793.88  5382.4  792.85
  5391.9  793.93  5397.8  792.99  5404.3  793.84  5450.6  793.81  5463.2  793.89
#Mann=5,-1,0
  4389.4    0.05       0  4849.5   0.075       0  5012.4    0.07       0
  5016.6   0.075       0  5450.6     0.1       0
Bank Sta=5012.4,5016.6
Exp/Cntr=0.3,0.1

Type RM Length L Ch R = 1,63219,480,480,480
BEGIN DESCRIPTION:
Henrietta Creek 102.0
END DESCRIPTION:
XS GIS Cut Line= 3
      2308485.43      7046052.62      2308929.00      7045810.00
      2308829.00      7045410.00
#Sta/Elev= 30
  4494.4  788.29  4572.7  784.85  4610.6  784.37  4616.3  785.06  4632.4  784.05
  4638.1  784.84  4735.8  784.40  4882.8  781.34  4964.4  778.14  4970.1  777.18
  4986.2  777.25  4995.0  776.20  4995.3  775.70  4999.3  776.20  5023.2  776.98
  5044.4  779.87  5064.4  780.61  5100.5  784.12  5113.4  784.45  5183.0  784.02
  5188.1  784.59  5216.5  782.43  5237.1  782.43  5278.3  785.95  5298.9  785.07
  5371.1  786.32  5381.4  786.93  5389.1  789.75  5402.0  792.56  5412.3  792.78
#Mann=4,-1,0
  4494.4    0.05       0  4995.0   0.033       0  4999.3    0.05       0
  5044.4   0.075       0
Bank Sta=4995,4999.3
Exp/Cntr=0.3,0.1

Type RM Length L Ch R = 1,62739,933,933,933
BEGIN DESCRIPTION:
Henrietta Creek 101.0
END DESCRIPTION:
XS GIS Cut Line= 3
      2309052.60      7046136.54      2309379.00      7045810.00
      2308929.00      7045210.00
#Sta/Elev= 30
  4542.0  779.99  4834.0  776.87  4911.8  773.22  4968.3  772.35  4973.3  770.74
  4973.6  770.24  4977.6  770.74  4989.6  772.84  5000.2  777.66  5043.9  779.01
  5175.6  779.49  5246.4  781.54  5325.6  778.32  5396.4  782.45  5411.0  781.00
  5417.2  782.82  5437.5  781.88  5461.0  783.06  5496.4  780.82  5575.6  786.45
  5623.3  788.38  5625.6  788.36  5631.8  792.97  5640.2  789.07  5646.4  793.02
  5653.7  790.77  5661.0  790.22  5667.2  793.28  5675.6  792.50  5753.7  794.05
#Mann=6,-1,0
  4542.0    0.05       0  4973.3   0.033       0  4977.6    0.05       0
  5043.9   0.075       0  5437.5    0.05       0  5623.3   0.075       0
Bank Sta=4973.3,4977.6
Exp/Cntr=0.3,0.1

Type RM Length L Ch R = 1,61806,425,425,425
BEGIN DESCRIPTION:
Henrietta Creek 100.0
END DESCRIPTION:
XS GIS Cut Line= 3
      2309879.00      7046660.01      2309979.00      7046060.00
      2309279.00      7045260.00
#Sta/Elev= 30
  4397.3  781.43  4458.1  779.69  4742.0  776.04  4894.1  773.03  4924.5  771.67
  4951.9  763.66  4952.9  763.16  4957.8  763.66  4965.0  765.12  5019.4  766.73
  5062.1  765.97  5090.5  768.93  5104.8  769.47  5218.2  770.77  5367.7  774.47
  5417.0  777.16  5501.5  777.52  5544.2  774.99  5572.7  775.00  5593.6  775.62
  5615.4  777.71  5657.2  778.97  5671.4  777.87  5799.5  779.77  5920.1  776.90
  5952.5  780.26  6022.7  780.87  6047.2  781.91  6054.8  784.17  6068.6  784.12
#Mann=6,-1,0
  4397.3    0.05       0  4951.9   0.033       0  4957.8    0.05       0
  5367.7   0.075       0  5952.5    0.05       0  6022.7   0.075       0
Bank Sta=4951.9,4957.8
Exp/Cntr=0.3,0.1

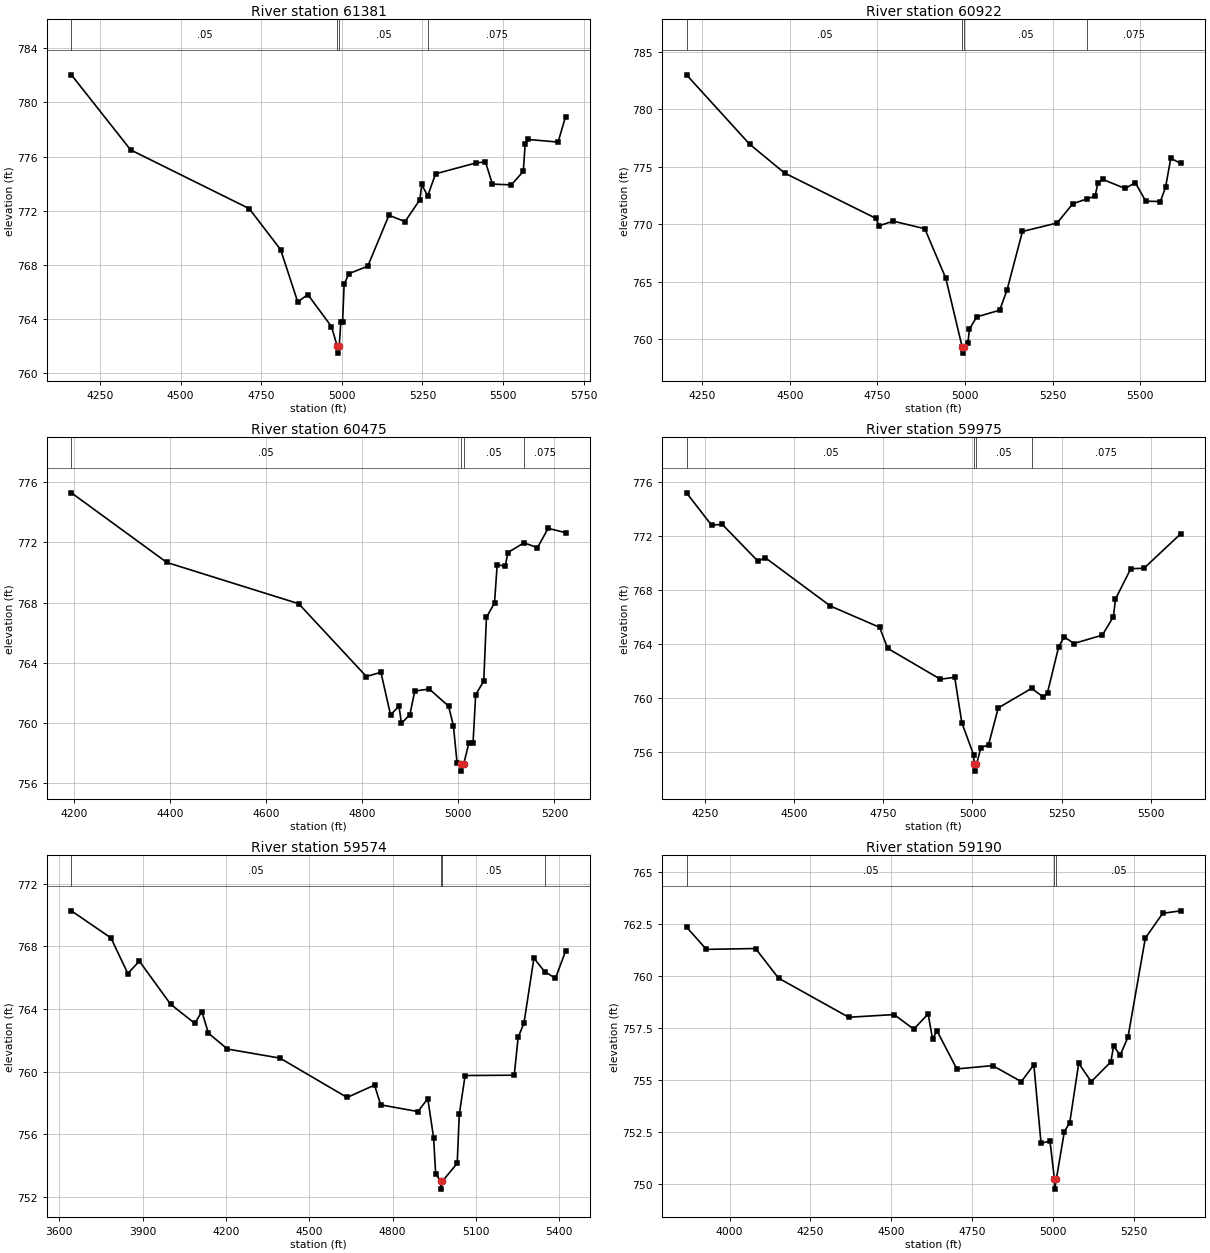
Type RM Length L Ch R = 1,61381,459,459,459
BEGIN DESCRIPTION:
Henrietta Creek 99.0
END DESCRIPTION:
XS GIS Cut Line= 3
      2310479.01      7046610.02      2310229.00      7045810.00
      2309879.00      7045210.00
#Sta/Elev= 30
  4161.3  782.03  4345.2  776.49  4712.9  772.16  4810.4  769.13  4863.3  765.28
  4894.7  765.82  4968.0  763.46  4986.0  762.00  4987.0  761.50  4992.0  762.00
  4996.9  763.77  5002.4  763.77  5007.3  766.59  5022.6  767.37  5080.5  767.91
  5146.3  771.67  5196.3  771.20  5242.2  772.82  5248.0  773.94  5266.4  773.10
  5291.0  774.73  5416.3  775.53  5445.6  775.61  5467.1  773.97  5525.8  773.91
  5563.0  774.91  5568.8  776.93  5578.3  777.26  5670.9  777.07  5694.1  778.95
#Mann=4,-1,0
  4161.3    0.05       0  4986.0   0.033       0  4992.0    0.05       0
  5266.4   0.075       0
Bank Sta=4986,4992
Exp/Cntr=0.3,0.1

Type RM Length L Ch R = 1,60922,447,447,447
BEGIN DESCRIPTION:
Henrietta Creek 98.0
END DESCRIPTION:
XS GIS Cut Line= 3
      2310629.00      7046609.96      2310629.00      7045810.00
      2310279.00      7045309.99
#Sta/Elev= 30
  4205.1  783.02  4385.1  776.98  4485.1  774.46  4745.1  770.52  4755.1  769.87
  4795.1  770.27  4885.1  769.61  4945.1  765.29  4992.0  759.27  4993.0  758.77
  4998.2  759.27  5008.1  759.63  5012.5  760.86  5033.4  761.93  5098.8  762.51
  5119.7  764.26  5163.8  769.37  5262.7  770.11  5307.2  771.78  5348.4  772.22
  5371.3  772.45  5378.7  773.57  5393.5  773.90  5456.7  773.12  5485.9  773.62
  5515.6  772.01  5557.4  771.98  5572.2  773.23  5587.1  775.75  5615.4  775.30
#Mann=4,-1,0
  4205.1    0.05       0  4992.0   0.033       0  4998.2    0.05       0
  5348.4   0.075       0
Bank Sta=4992,4998.2
Exp/Cntr=0.3,0.1

Type RM Length L Ch R = 1,60475,500,500,500
BEGIN DESCRIPTION:
Henrietta Creek 97.0
END DESCRIPTION:
XS GIS Cut Line= 3
      2310829.00      7046359.98      2310729.00      7045560.00
      2310529.01      7045460.00
#Sta/Elev= 30
  4193.5  775.30  4392.5  770.67  4667.1  767.93  4808.2  763.09  4838.5  763.37
  4858.6  760.54  4876.2  761.12  4881.3  759.97  4898.9  760.56  4909.0  762.12
  4939.2  762.26  4979.5  761.12  4989.6  759.81  4997.2  757.34  5005.0  757.30
  5006.0  756.80  5011.2  757.30  5022.1  758.70  5030.4  758.64  5036.0  761.88
  5052.8  762.79  5058.4  767.03  5075.2  767.97  5080.8  770.53  5097.5  770.41
  5103.1  771.33  5136.8  771.98  5164.6  771.65  5187.0  772.94  5223.3  772.65
#Mann=4,-1,0
  4193.5    0.05       0  5005.0    0.05       0  5011.2    0.05       0
  5136.8   0.075       0
Bank Sta=5005,5011.2
Exp/Cntr=0.3,0.1

Type RM Length L Ch R = 1,59975,401,401,401
BEGIN DESCRIPTION:
Henrietta Creek 96.0
END DESCRIPTION:
XS GIS Cut Line= 3
      2311179.00      7046359.96      2311229.00      7045560.00
      2310729.01      7045260.01
#Sta/Elev= 30
  4198.9  775.21  4269.0  772.81  4299.1  772.87  4399.3  770.13  4419.3  770.40
  4602.1  766.81  4739.9  765.23  4762.5  763.67  4910.2  761.38  4950.3  761.52
  4970.4  758.14  5003.3  755.77  5005.0  755.06  5006.0  754.56  5011.3  755.06
  5023.7  756.30  5045.1  756.51  5072.3  759.25  5165.7  760.70  5198.7  760.06
  5210.3  760.39  5241.4  763.76  5257.0  764.53  5284.2  764.03  5363.9  764.65
  5395.0  766.02  5400.8  767.33  5443.6  769.58  5480.5  769.61  5583.5  772.17
#Mann=4,-1,0
  4198.9    0.05       0  5005.0   0.033       0  5011.3    0.05       0
  5165.7   0.075       0
Bank Sta=5005,5011.3
Exp/Cntr=0.3,0.1

Type RM Length L Ch R = 1,59574,384,384,384
BEGIN DESCRIPTION:
Henrietta Creek 95.8
END DESCRIPTION:
XS GIS Cut Line= 4
      2311670.04      7046419.23      2311817.50      7045737.66
      2311479.68      7045339.67      2311068.22      7044959.47
#Sta/Elev= 30
  3643.5  770.26  3786.0  768.53  3846.8  766.26  3888.3  767.05  4000.8  764.30
  4087.8  763.08  4113.4  763.83  4137.0  762.45  4205.4  761.44  4394.7  760.86
  4636.4  758.35  4735.2  759.14  4757.2  757.88  4891.2  757.45  4926.9  758.27
  4947.9  755.78  4955.2  753.49  4973.0  753.00  4974.1  752.50  4979.4  753.00
  5032.9  754.15  5040.3  757.27  5061.3  759.75  5238.2  759.77  5252.4  762.19
  5273.3  763.10  5309.1  767.24  5348.1  766.37  5386.7  765.96  5423.1  767.69
#Mann=4,-1,0
  3643.5    0.05       0  4973.0   0.033       0  4979.4    0.05       0
  5348.1   0.075       0
Bank Sta=4973,4979.4
Exp/Cntr=0.3,0.1

Type RM Length L Ch R = 1,59190,631,631,631
BEGIN DESCRIPTION:
Henrietta Creek 95.5
END DESCRIPTION:
XS GIS Cut Line= 4
      2311900.49      7046010.71      2311828.42      7045559.61
      2311432.80      7044792.80      2311240.48      7044714.83
#Sta/Elev= 30
  3867.1  762.35  3928.6  761.28  4080.5  761.32  4151.4  759.90  4368.5  758.02
  4508.6  758.15  4569.4  757.45  4613.8  758.18  4627.3  756.99  4641.5  757.36
  4702.4  755.54  4813.2  755.70  4901.8  754.93  4940.5  755.74  4962.7  751.97
  4990.4  752.08  5003.8  750.27  5004.8  749.77  5010.2  750.27  5034.7  752.53
  5051.3  752.95  5079.1  755.81  5117.8  754.93  5178.6  755.88  5186.8  756.64
  5207.3  756.20  5231.4  757.07  5285.0  761.82  5338.6  763.01  5394.3  763.13
#Mann=3,-1,0
  3867.1    0.05       0  5003.8   0.033       0  5010.2    0.05       0
Bank Sta=5003.8,5010.2
Exp/Cntr=0.3,0.1