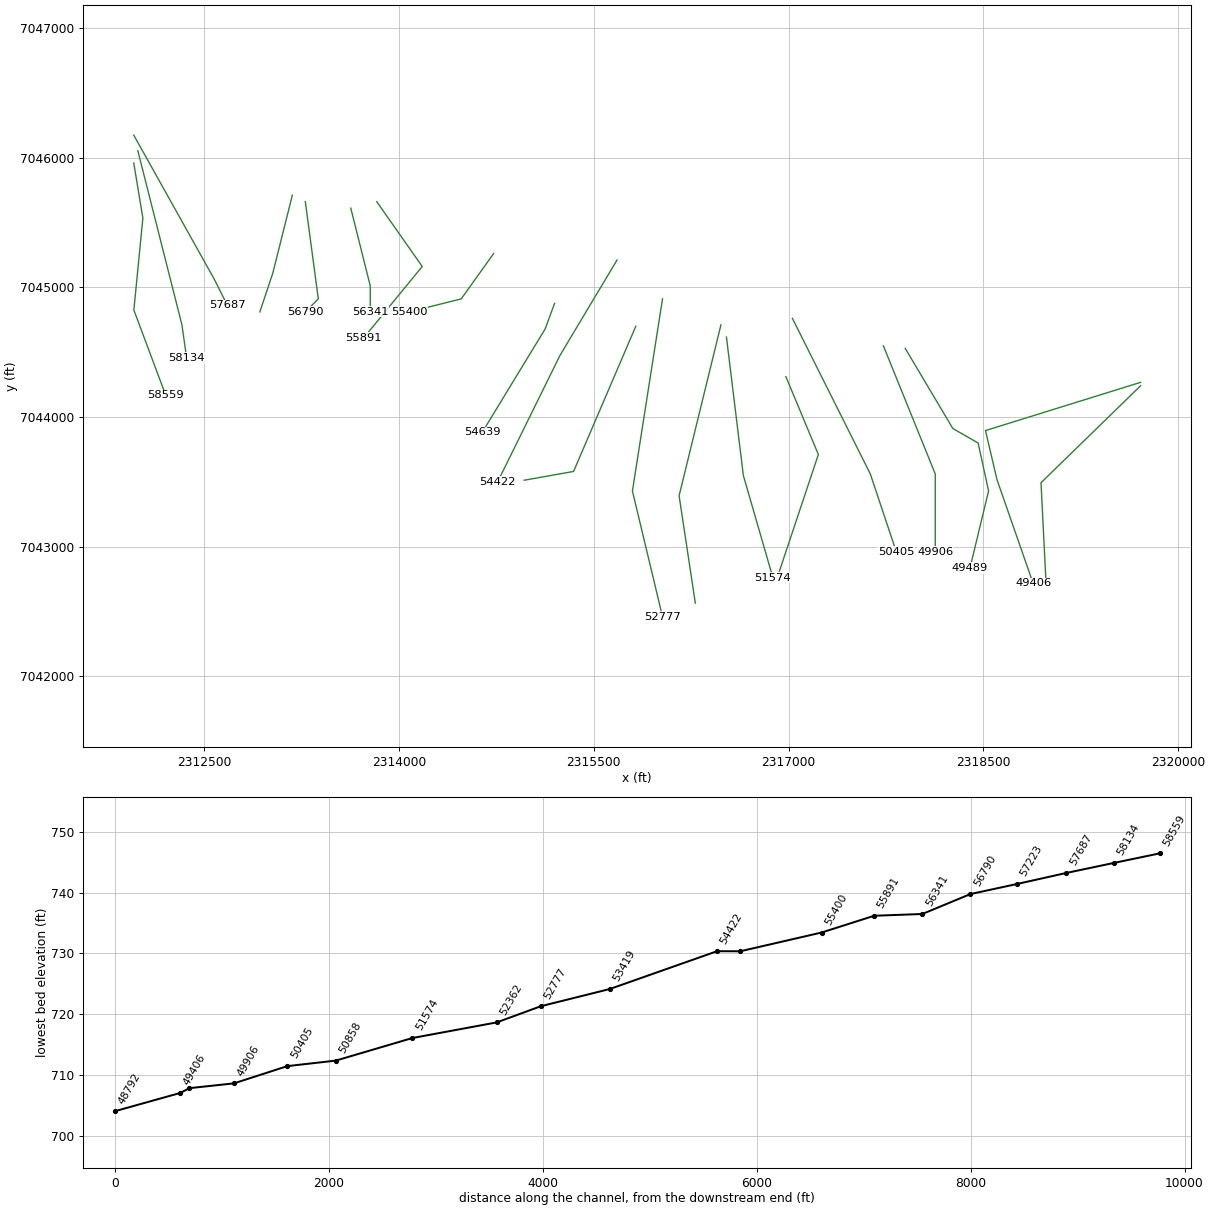
HEC-RAS study Henrietta Creek.prj: Henrietta Creek Base Level Engineering

--- Henrietta Creek.g01 (geometry) --- (continued)

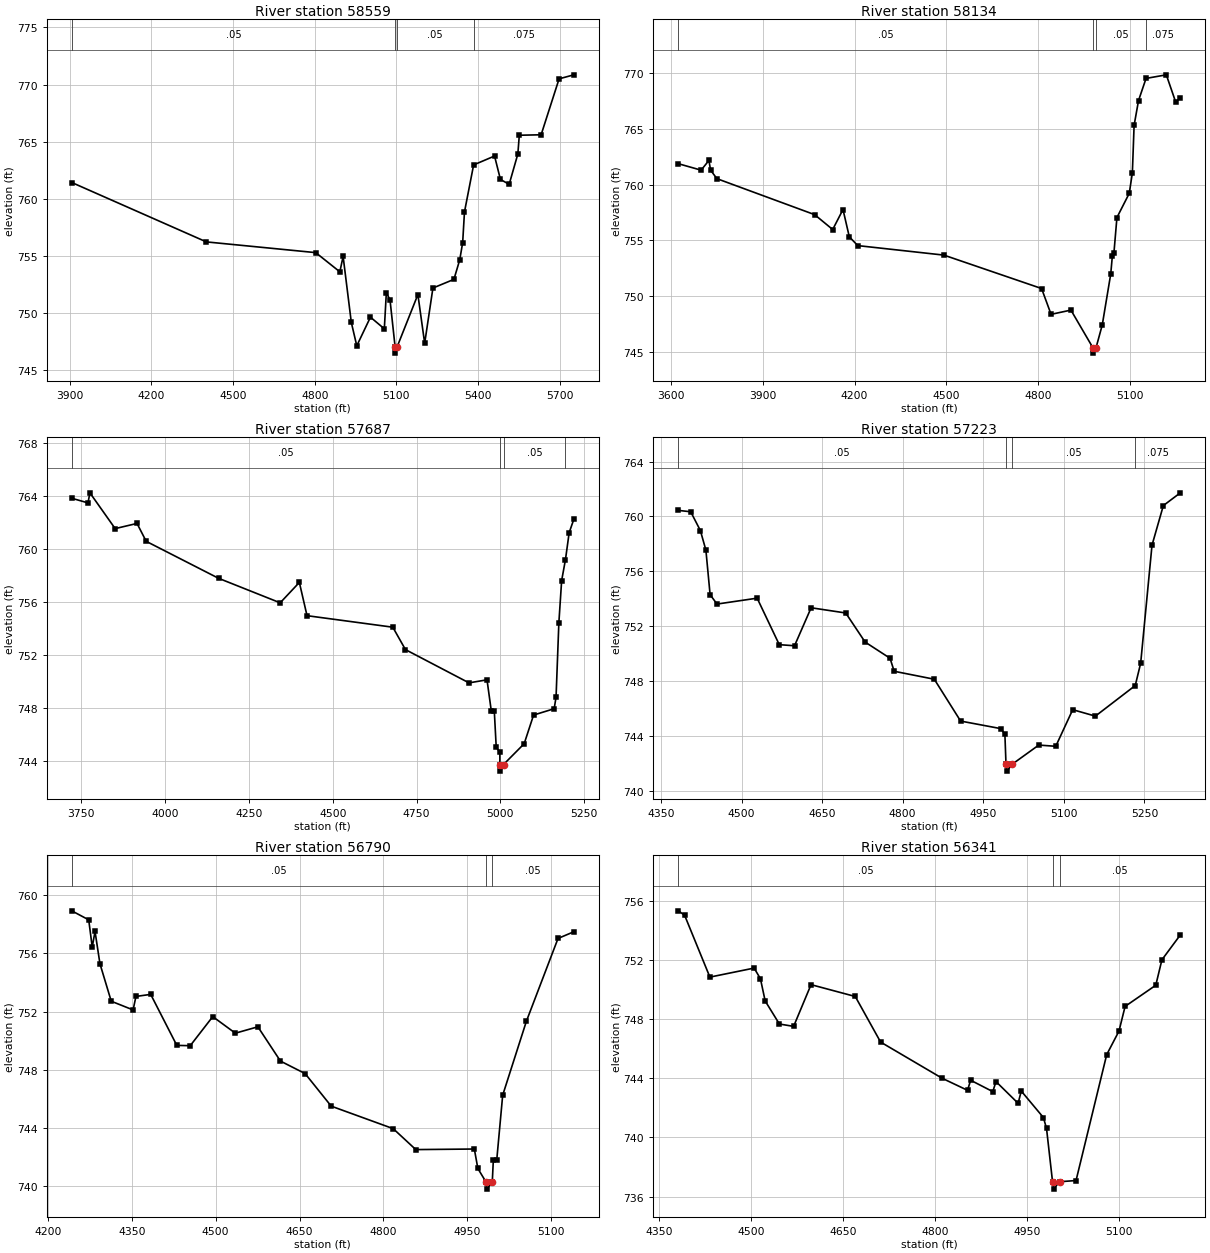
Type RM Length L Ch R = 1,58559,425,425,425
BEGIN DESCRIPTION:
Henrietta Creek 95.2
END DESCRIPTION:
XS GIS Cut Line= 4
      2311958.11      7045958.32      2312028.29      7045533.36
      2311958.85      7044824.05      2312204.14      7044167.39
#Sta/Elev= 30
  3907.6  761.42  4402.0  756.22  4803.9  755.28  4892.4  753.60  4904.4  754.95
  4934.5  749.17  4954.6  747.12  5004.8  749.63  5055.8  748.61  5063.2  751.77
  5076.7  751.14  5095.6  746.98  5096.7  746.48  5102.0  746.98  5179.1  751.61
  5204.0  747.34  5234.3  752.18  5311.5  752.94  5332.9  754.66  5343.6  756.16
  5350.2  758.84  5383.8  762.96  5460.7  763.74  5482.3  761.69  5514.4  761.26
  5546.3  763.92  5551.6  765.56  5631.8  765.60  5697.8  770.50  5752.0  770.85
#Mann=4,-1,0
  3907.6    0.05       0  5095.6   0.033       0  5102.0    0.05       0
  5383.8   0.075       0
Bank Sta=5095.6,5102
Exp/Cntr=0.3,0.1

Type RM Length L Ch R = 1,58134,447,447,447
BEGIN DESCRIPTION:
Henrietta Creek 95.0
END DESCRIPTION:
XS GIS Cut Line= 3
      2311989.53      7046052.65      2312329.00      7044710.00
      2312365.04      7044454.63
#Sta/Elev= 30
  3623.0  761.87  3697.9  761.29  3723.3  762.16  3728.9  761.29  3749.5  760.53
  4069.3  757.31  4128.4  755.98  4162.1  757.77  4182.7  755.33  4210.4  754.54
  4492.2  753.69  4811.9  750.70  4842.9  748.39  4907.9  748.77  4979.4  745.42
  4980.9  744.92  4990.2  745.42  5010.4  747.44  5038.2  752.01  5043.5  753.64
  5048.5  753.86  5058.4  757.05  5098.8  759.22  5108.9  761.05  5114.6  765.30
  5129.1  767.52  5153.7  769.50  5220.0  769.82  5250.3  767.41  5265.8  767.75
#Mann=4,-1,0
  3623.0    0.05       0  4979.4   0.033       0  4990.2    0.05       0
  5153.7   0.075       0
Bank Sta=4979.4,4990.2
Exp/Cntr=0.3,0.1

Type RM Length L Ch R = 1,57687,464,464,464
BEGIN DESCRIPTION:
Henrietta Creek 94.0
END DESCRIPTION:
XS GIS Cut Line= 3
      2311958.10      7046173.11      2312579.00      7045060.00
      2312679.01      7044859.98
#Sta/Elev= 30
  3721.3  763.85  3769.7  763.50  3775.4  764.26  3850.8  761.56  3916.0  761.95
  3943.4  760.60  4159.4  757.81  4343.2  755.96  4400.4  757.50  4423.3  754.99
  4679.3  754.12  4717.0  752.43  4906.7  749.92  4960.4  750.15  4973.0  747.83
  4982.1  747.81  4987.9  745.05  4998.7  744.71  4998.8  743.76  5000.3  743.26
  5009.7  743.76  5071.3  745.33  5099.3  747.49  5160.8  747.97  5166.4  748.84
  5174.8  754.46  5183.1  757.64  5194.5  759.22  5205.5  761.25  5219.5  762.27
#Mann=4,-1,0
  3721.3    0.05       0  4998.8   0.033       0  5009.7    0.05       0
  5194.5   0.075       0
Bank Sta=4998.8,5009.7
Exp/Cntr=0.3,0.1

Type RM Length L Ch R = 1,57223,433,433,433
BEGIN DESCRIPTION:
Henrietta Creek 93.0
END DESCRIPTION:
XS GIS Cut Line= 3
      2313179.00      7045709.99      2313029.00      7045110.00
      2312928.99      7044809.98
#Sta/Elev= 30
  4382.2  760.44  4405.4  760.34  4423.4  758.97  4433.7  757.54  4441.5  754.30
  4454.3  753.61  4529.1  754.04  4570.3  750.65  4598.7  750.57  4629.6  753.34
  4694.0  752.96  4730.1  750.84  4776.5  749.66  4784.2  748.71  4858.9  748.13
  4907.9  745.08  4982.6  744.53  4990.3  744.13  4992.4  741.93  4994.0  741.43
  5003.8  741.93  5053.4  743.33  5085.0  743.24  5116.6  745.91  5158.8  745.44
  5233.0  747.67  5243.1  749.30  5264.2  757.90  5285.3  760.79  5316.9  761.72
#Mann=4,-1,0
  4382.2    0.05       0  4992.4   0.033       0  5003.8    0.05       0
  5233.0   0.075       0
Bank Sta=4992.4,5003.8
Exp/Cntr=0.3,0.1

Type RM Length L Ch R = 1,56790,449,449,449
BEGIN DESCRIPTION:
Henrietta Creek 92.0
END DESCRIPTION:
XS GIS Cut Line= 3
      2313279.00      7045660.00      2313379.00      7044910.00
      2313278.97      7044809.97
#Sta/Elev= 30
  4242.6  758.93  4272.9  758.31  4279.2  756.44  4284.2  757.51  4293.0  755.29
  4313.2  752.71  4352.3  752.11  4357.4  753.04  4383.8  753.18  4430.5  749.67
  4454.5  749.65  4494.8  751.65  4535.2  750.51  4575.5  750.95  4615.9  748.59
  4660.0  747.73  4706.7  745.49  4817.6  743.94  4858.0  742.50  4962.7  742.54
  4969.0  741.20  4983.4  740.28  4985.0  739.78  4994.8  740.28  4996.7  741.79
  5002.8  741.79  5013.4  746.24  5055.8  751.33  5112.4  757.03  5140.7  757.49
#Mann=3,-1,0
  4242.6    0.05       0  4983.4   0.033       0  4994.8    0.05       0
Bank Sta=4983.4,4994.8
Exp/Cntr=0.3,0.1

Type RM Length L Ch R = 1,56341,450,450,450
BEGIN DESCRIPTION:
Henrietta Creek 91.0
END DESCRIPTION:
XS GIS Cut Line= 3
      2313629.00      7045610.01      2313779.00      7045010.00
      2313779.00      7044809.98
#Sta/Elev= 30
  4381.6  755.31  4391.9  755.02  4433.2  750.83  4505.3  751.44  4515.6  750.72
  4523.3  749.22  4546.5  747.66  4569.7  747.50  4598.1  750.32  4670.2  749.52
  4711.5  746.44  4812.0  743.99  4853.2  743.18  4858.3  743.86  4894.4  743.09
  4899.6  743.77  4935.7  742.30  4940.8  743.13  4976.9  741.34  4982.0  740.60
  4991.8  737.00  4993.4  736.50  5003.2  737.00  5030.1  737.08  5080.1  745.59
  5100.1  747.18  5110.1  748.85  5160.1  750.28  5170.1  752.00  5200.1  753.68
#Mann=3,-1,0
  4381.6    0.05       0  4991.8   0.033       0  5003.2    0.05       0
Bank Sta=4991.8,5003.2
Exp/Cntr=0.3,0.1

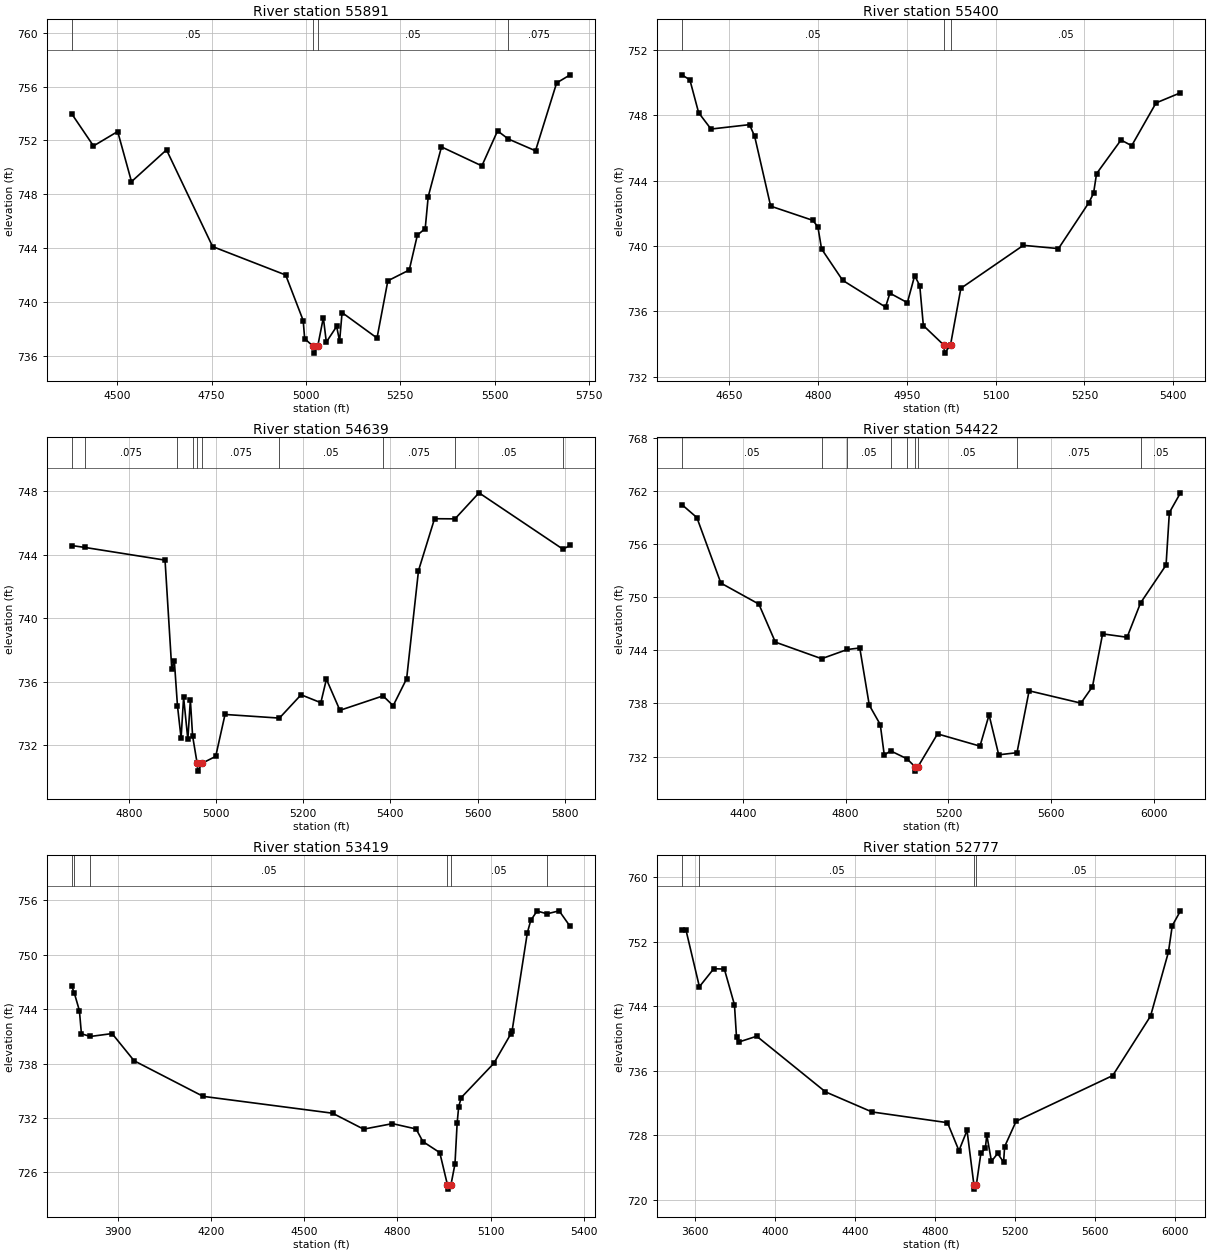
Type RM Length L Ch R = 1,55891,491,491,491
BEGIN DESCRIPTION:
Henrietta Creek 90.0
END DESCRIPTION:
XS GIS Cut Line= 3
      2313829.00      7045660.00      2314179.00      7045160.00
      2313728.98      7044609.97
#Sta/Elev= 30
  4379.1  753.99  4437.1  751.59  4501.2  752.66  4537.8  748.94  4630.6  751.30
  4752.7  744.12  4946.3  742.01  4992.7  738.63  4996.6  737.28  5019.6  736.71
  5021.2  736.21  5031.1  736.71  5046.1  738.84  5054.0  737.03  5081.3  738.19
  5089.2  737.10  5095.7  739.22  5188.3  737.33  5217.0  741.58  5273.7  742.38
  5295.2  744.97  5316.0  745.46  5323.9  747.82  5359.1  751.52  5466.1  750.11
  5507.7  752.71  5535.9  752.11  5608.2  751.23  5664.2  756.27  5700.1  756.87
#Mann=4,-1,0
  4379.1    0.05       0  5019.6   0.033       0  5031.1    0.05       0
  5535.9   0.075       0
Bank Sta=5019.6,5031.1
Exp/Cntr=0.3,0.1

Type RM Length L Ch R = 1,55400,761,761,761
BEGIN DESCRIPTION:
Henrietta Creek 89.0
END DESCRIPTION:
XS GIS Cut Line= 3
      2314729.02      7045260.02      2314479.00      7044910.00
      2314078.96      7044809.99
#Sta/Elev= 30
  4569.8  750.49  4583.3  750.18  4598.1  748.17  4619.0  747.17  4684.1  747.44
  4692.7  746.73  4719.8  742.45  4791.0  741.58  4799.6  741.18  4805.8  739.83
  4841.4  737.91  4913.9  736.27  4921.3  737.12  4950.8  736.54  4963.1  738.19
  4971.7  737.59  4977.8  735.14  5012.2  733.95  5013.8  733.45  5023.7  733.95
  5041.2  737.42  5146.8  740.05  5206.1  739.85  5257.6  742.67  5265.4  743.24
  5270.5  744.44  5311.8  746.50  5329.8  746.15  5371.0  748.77  5412.3  749.39
#Mann=3,-1,0
  4569.8    0.05       0  5012.2   0.033       0  5023.7    0.05       0
Bank Sta=5012.2,5023.7
Exp/Cntr=0.3,0.1

Type RM Length L Ch R = 1,54639,217,217,217
BEGIN DESCRIPTION:
Henrietta Creek 88.0
END DESCRIPTION:
XS GIS Cut Line= 3
      2315198.43      7044876.15      2315125.51      7044678.22
      2314641.12      7043881.32
#Sta/Elev= 30
  4668.8  744.57  4699.3  744.45  4883.1  743.65  4898.6  736.77  4904.4  737.32
  4911.6  734.48  4919.9  732.44  4925.7  735.01  4935.4  732.36  4941.2  734.85
  4946.3  732.58  4956.7  730.86  4958.3  730.36  4968.3  730.86  4999.3  731.29
  5020.7  733.93  5145.4  733.70  5195.1  735.17  5240.4  734.67  5253.2  736.15
  5284.2  734.19  5383.1  735.10  5406.3  734.48  5437.2  736.18  5464.4  742.99
  5501.2  746.26  5548.1  746.25  5603.2  747.89  5795.7  744.34  5812.3  744.58
#Mann=10,-1,0
  4668.8    0.05       0  4699.3   0.075       0  4911.6    0.05       0
  4946.3   0.075       0  4956.7    0.07       0  4968.3   0.075       0
  5145.4    0.05       0  5383.1   0.075       0  5548.1    0.05       0
  5795.7   0.075       0
Bank Sta=4956.7,4968.3
Exp/Cntr=0.3,0.1

Type RM Length L Ch R = 1,54422,1003,1003,1003
BEGIN DESCRIPTION:
Henrietta Creek 87.0
END DESCRIPTION:
XS GIS Cut Line= 3
      2315679.02      7045210.04      2315240.10      7044475.09
      2314760.92      7043501.12
#Sta/Elev= 30
  4162.2  760.43  4220.5  758.97  4314.0  751.58  4461.9  749.21  4526.1  744.92
  4706.3  743.05  4806.5  744.09  4854.9  744.26  4891.9  737.81  4934.7  735.62
  4950.3  732.17  4974.6  732.66  5038.1  731.77  5069.9  730.87  5071.5  730.37
  5081.5  730.87  5157.6  734.57  5322.9  733.19  5358.3  736.71  5395.9  732.21
  5467.0  732.45  5514.3  739.43  5716.0  738.04  5761.0  739.90  5800.4  745.85
  5895.8  745.47  5948.2  749.34  6047.5  753.61  6060.4  759.53  6103.7  761.76
#Mann=9,-1,0
  4162.2    0.05       0  4706.3   0.075       0  4806.5    0.05       0
  4974.6   0.075       0  5038.1    0.05       0  5069.9    0.07       0
  5081.5    0.05       0  5467.0   0.075       0  5948.2    0.05       0
Bank Sta=5069.9,5081.5
Exp/Cntr=0.3,0.1

Type RM Length L Ch R = 1,53419,642,642,642
BEGIN DESCRIPTION:
Henrietta Creek 86.0
END DESCRIPTION:
XS GIS Cut Line= 3
      2315823.44      7044699.07      2315344.26      7043579.26
      2314964.07      7043511.55
#Sta/Elev= 30
  3751.7  746.56  3760.1  745.82  3776.8  743.85  3783.3  741.29  3811.9  740.99
  3882.0  741.31  3952.8  738.31  4174.9  734.38  4591.4  732.52  4691.2  730.76
  4784.0  731.37  4860.1  730.78  4881.9  729.39  4936.3  728.17  4960.8  724.64
  4962.4  724.14  4972.4  724.64  4985.2  726.92  4992.2  731.44  4997.2  733.25
  5005.5  734.25  5110.1  738.02  5164.0  741.22  5169.1  741.63  5218.0  752.43
  5229.0  753.80  5249.3  754.84  5281.5  754.53  5320.4  754.86  5355.9  753.13
#Mann=6,-1,0
  3751.7    0.05       0  3760.1   0.075       0  3811.9    0.05       0
  4960.8   0.033       0  4972.4    0.05       0  5281.5   0.075       0
Bank Sta=4960.8,4972.4
Exp/Cntr=0.3,0.1

Type RM Length L Ch R = 1,52777,415,415,415
BEGIN DESCRIPTION:
Henrietta Creek 85.0
END DESCRIPTION:
XS GIS Cut Line= 3
      2316029.00      7044909.98      2315797.39      7043428.22
      2316029.00      7042459.99
#Sta/Elev= 30
  3532.9  753.45  3553.1  753.47  3620.5  746.42  3692.3  748.65  3745.4  748.61
  3796.0  744.18  3806.2  740.17  3816.3  739.55  3907.4  740.28  4251.5  733.38
  4484.3  730.89  4862.1  729.56  4919.5  726.09  4960.0  728.60  4994.5  721.82
  4996.2  721.32  5006.4  721.82  5029.2  725.76  5051.4  726.37  5058.8  728.03
  5082.2  724.77  5113.1  725.74  5142.9  724.67  5148.1  726.59  5205.6  729.74
  5688.9  735.40  5878.4  742.78  5967.7  750.70  5987.1  753.99  6028.2  755.83
#Mann=4,-1,0
  3532.9   0.075       0  3620.5    0.05       0  4994.5   0.033       0
  5006.4    0.05       0
Bank Sta=4994.5,5006.4
Exp/Cntr=0.3,0.1

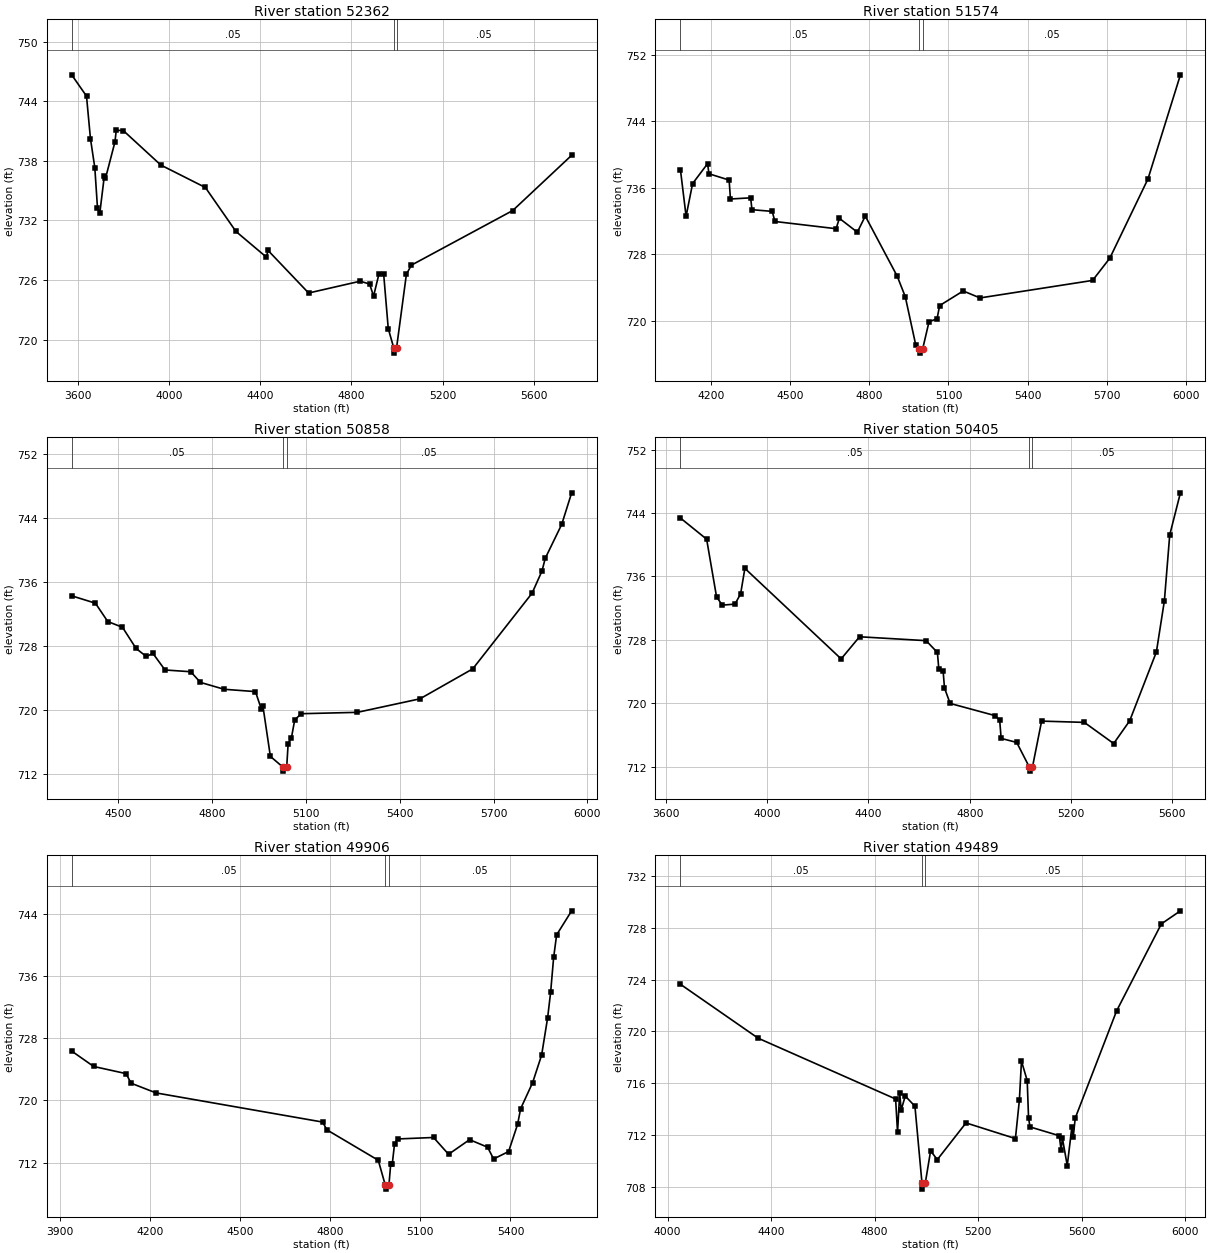
Type RM Length L Ch R = 1,52362,788,788,788
BEGIN DESCRIPTION:
Henrietta Creek 84.0
END DESCRIPTION:
XS GIS Cut Line= 3
      2316479.01      7044710.05      2316156.76      7043391.76
      2316281.66      7042564.33
#Sta/Elev= 30
  3572.5  746.65  3637.6  744.51  3654.9  740.24  3674.1  737.30  3685.8  733.25
  3696.1  732.76  3715.7  736.44  3720.9  736.23  3762.5  739.90  3768.1  741.07
  3799.0  741.04  3963.7  737.57  4159.3  735.31  4293.2  730.89  4427.0  728.30
  4434.0  728.98  4612.3  724.69  4838.8  725.88  4879.9  725.59  4897.3  724.38
  4921.1  726.63  4941.5  726.62  4961.7  721.11  4986.1  719.14  4987.8  718.64
  4998.0  719.14  5041.3  726.57  5062.9  727.49  5507.8  732.99  5766.4  738.55
#Mann=3,-1,0
  3572.5    0.05       0  4986.1   0.033       0  4998.0    0.05       0
Bank Sta=4986.1,4998
Exp/Cntr=0.3,0.1

Type RM Length L Ch R = 1,51574,716,716,716
BEGIN DESCRIPTION:
Henrietta Creek 83.0
END DESCRIPTION:
XS GIS Cut Line= 3
      2316521.35      7044615.72      2316651.55      7043548.01
      2316879.00      7042760.00
#Sta/Elev= 30
  4083.7  738.16  4105.1  732.56  4129.8  736.50  4186.7  738.90  4191.7  737.68
  4268.3  736.92  4273.3  734.64  4349.9  734.78  4354.9  733.35  4431.5  733.15
  4442.1  731.93  4673.8  731.06  4686.4  732.31  4754.4  730.64  4784.6  732.58
  4905.5  725.35  4936.2  722.87  4976.0  717.04  4990.1  716.57  4991.8  716.07
  5002.1  716.57  5026.4  719.87  5056.6  720.20  5066.6  721.80  5155.8  723.56
  5219.7  722.72  5646.4  724.83  5711.6  727.50  5856.5  737.06  5979.5  749.60
#Mann=3,-1,0
  4083.7    0.05       0  4990.1   0.033       0  5002.1    0.05       0
Bank Sta=4990.1,5002.1
Exp/Cntr=0.3,0.1

Type RM Length L Ch R = 1,50858,453,453,453
BEGIN DESCRIPTION:
Henrietta Creek 82.0
END DESCRIPTION:
XS GIS Cut Line= 3
      2316978.99      7044310.02      2317229.00      7043710.00
      2316929.00      7042810.01
#Sta/Elev= 30
  4350.6  734.24  4426.5  733.32  4466.0  731.03  4513.1  730.31  4556.5  727.67
  4589.0  726.67  4610.6  727.04  4649.1  724.98  4731.4  724.76  4762.3  723.43
  4838.1  722.57  4938.3  722.28  4956.8  720.12  4962.2  720.46  4986.0  714.19
  5026.2  712.85  5027.9  712.35  5038.2  712.85  5042.8  715.79  5053.3  716.51
  5063.9  718.76  5085.0  719.52  5264.1  719.69  5464.4  721.38  5633.1  725.12
  5822.8  734.57  5854.4  737.33  5865.0  738.93  5917.7  743.17  5949.3  747.10
#Mann=3,-1,0
  4350.6    0.05       0  5026.2   0.033       0  5038.2    0.05       0
Bank Sta=5026.2,5038.2
Exp/Cntr=0.3,0.1

Type RM Length L Ch R = 1,50405,499,499,499
BEGIN DESCRIPTION:
Henrietta Creek 81.0
END DESCRIPTION:
XS GIS Cut Line= 3
      2317029.00      7044760.00      2317629.00      7043560.00
      2317829.00      7042960.00
#Sta/Elev= 30
  3657.9  743.37  3761.3  740.70  3800.4  733.44  3822.8  732.38  3873.1  732.51
  3895.5  733.80  3912.3  737.02  4292.4  725.60  4365.1  728.39  4627.8  727.90
  4672.5  726.41  4678.1  724.30  4694.9  724.13  4700.5  721.92  4722.8  719.98
  4901.7  718.43  4918.5  717.83  4924.1  715.57  4985.6  715.06  5035.7  711.94
  5037.4  711.44  5047.7  711.94  5083.9  717.75  5252.5  717.59  5368.5  714.92
  5431.7  717.79  5537.1  726.47  5568.7  732.93  5589.8  741.24  5632.0  746.55
#Mann=3,-1,0
  3657.9    0.05       0  5035.7   0.033       0  5047.7    0.05       0
Bank Sta=5035.7,5047.7
Exp/Cntr=0.3,0.1

Type RM Length L Ch R = 1,49906,417,417,417
BEGIN DESCRIPTION:
Henrietta Creek 80.0
END DESCRIPTION:
XS GIS Cut Line= 3
      2317729.68      7044548.00      2318129.00      7043560.00
      2318129.00      7042960.04
#Sta/Elev= 30
  3938.2  726.35  4011.5  724.37  4119.4  723.45  4136.1  722.22  4219.2  720.97
  4774.5  717.22  4788.1  716.23  4959.6  712.31  4983.1  709.10  4984.7  708.60
  4995.1  709.10  5001.1  711.85  5006.3  711.85  5013.8  714.41  5023.8  715.05
  5143.8  715.24  5193.8  713.08  5263.8  714.96  5323.8  713.99  5343.8  712.48
  5393.8  713.43  5423.8  716.94  5433.8  718.93  5473.8  722.29  5503.8  725.83
  5523.8  730.63  5533.8  733.90  5543.8  738.38  5553.8  741.29  5603.8  744.38
#Mann=3,-1,0
  3938.2    0.05       0  4983.1   0.033       0  4995.1    0.05       0
Bank Sta=4983.1,4995.1
Exp/Cntr=0.3,0.1

Type RM Length L Ch R = 1,49489,83,83,83
BEGIN DESCRIPTION:
Henrietta Creek 79.0
END DESCRIPTION:
XS GIS Cut Line= 5
      2317897.78      7044528.45      2318264.44      7043910.35
      2318458.90      7043798.74      2318539.61      7043429.19
      2318396.41      7042834.74
#Sta/Elev= 30
  4049.6  723.65  4350.0  719.48  4881.3  714.78  4888.8  712.20  4897.1  715.24
  4902.8  713.93  4918.6  715.01  4956.0  714.22  4983.1  708.31  4985.0  707.81
  4996.3  708.31  5016.6  710.77  5042.4  710.09  5153.4  712.93  5344.4  711.72
  5359.7  714.68  5367.8  717.71  5390.0  716.20  5395.2  713.31  5400.8  712.62
  5513.9  711.94  5520.9  710.84  5526.1  711.74  5544.8  709.63  5562.8  712.64
  5568.0  711.85  5575.6  713.30  5735.7  721.60  5908.5  728.32  5982.2  729.33
#Mann=3,-1,0
  4049.6    0.05       0  4983.1   0.033       0  4996.3    0.05       0
Bank Sta=4983.1,4996.3
Exp/Cntr=0.3,0.1

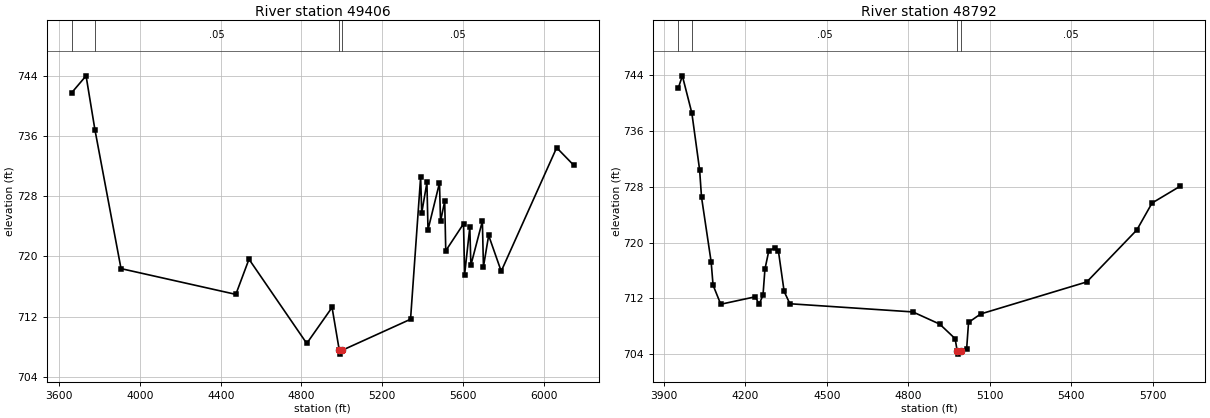
Type RM Length L Ch R = 1,49406,614,614,614
BEGIN DESCRIPTION:
Henrietta Creek 78.0
END DESCRIPTION:
XS GIS Cut Line= 4
      2319710.04      7044266.51      2318515.86      7043894.64
      2318604.22      7043516.13      2318882.49      7042716.17
#Sta/Elev= 30
  3662.4  741.74  3733.2  743.97  3776.9  736.84  3906.3  718.38  4474.9  714.96
  4540.0  719.63  4826.1  708.45  4951.4  713.23  4987.3  707.53  4989.2  707.03
  5000.5  707.53  5340.1  711.66  5390.1  730.55  5395.4  725.76  5421.2  729.82
  5426.5  723.53  5483.4  729.76  5488.7  724.66  5509.2  727.33  5514.5  720.75
  5602.5  724.33  5607.8  717.58  5633.6  723.87  5638.9  718.84  5695.8  724.68
  5701.1  718.62  5726.9  722.79  5789.1  718.03  6063.7  734.43  6148.8  732.09
#Mann=4,-1,0
  3662.4   0.075       0  3776.9    0.05       0  4987.3   0.033       0
  5000.5    0.05       0
Bank Sta=4987.3,5000.5
Exp/Cntr=0.3,0.1

Type RM Length L Ch R = 1,48792,691,691,691
BEGIN DESCRIPTION:
Henrietta Creek 77.0
END DESCRIPTION:
XS GIS Cut Line= 3
      2319710.05      7044240.30      2318943.26      7043492.44
      2318982.03      7042716.11
#Sta/Elev= 30
  3953.1  742.12  3968.3  743.90  4003.2  738.57  4031.8  730.43  4038.8  726.52
  4074.3  717.22  4081.3  713.90  4109.6  711.16  4236.9  712.23  4251.0  711.14
  4265.2  712.49  4272.3  716.19  4286.5  718.81  4307.6  719.22  4321.7  718.84
  4343.0  712.99  4364.2  711.23  4816.8  710.06  4915.8  708.31  4972.4  706.23
  4979.9  704.51  4981.8  704.01  4993.3  704.51  5014.9  704.78  5021.9  708.56
  5066.7  709.77  5457.2  714.36  5641.5  721.81  5697.5  725.67  5801.5  728.09
#Mann=4,-1,0
  3953.1   0.075       0  4003.2    0.05       0  4979.9   0.033       0
  4993.3    0.05       0
Bank Sta=4979.9,4993.3
Exp/Cntr=0.3,0.1