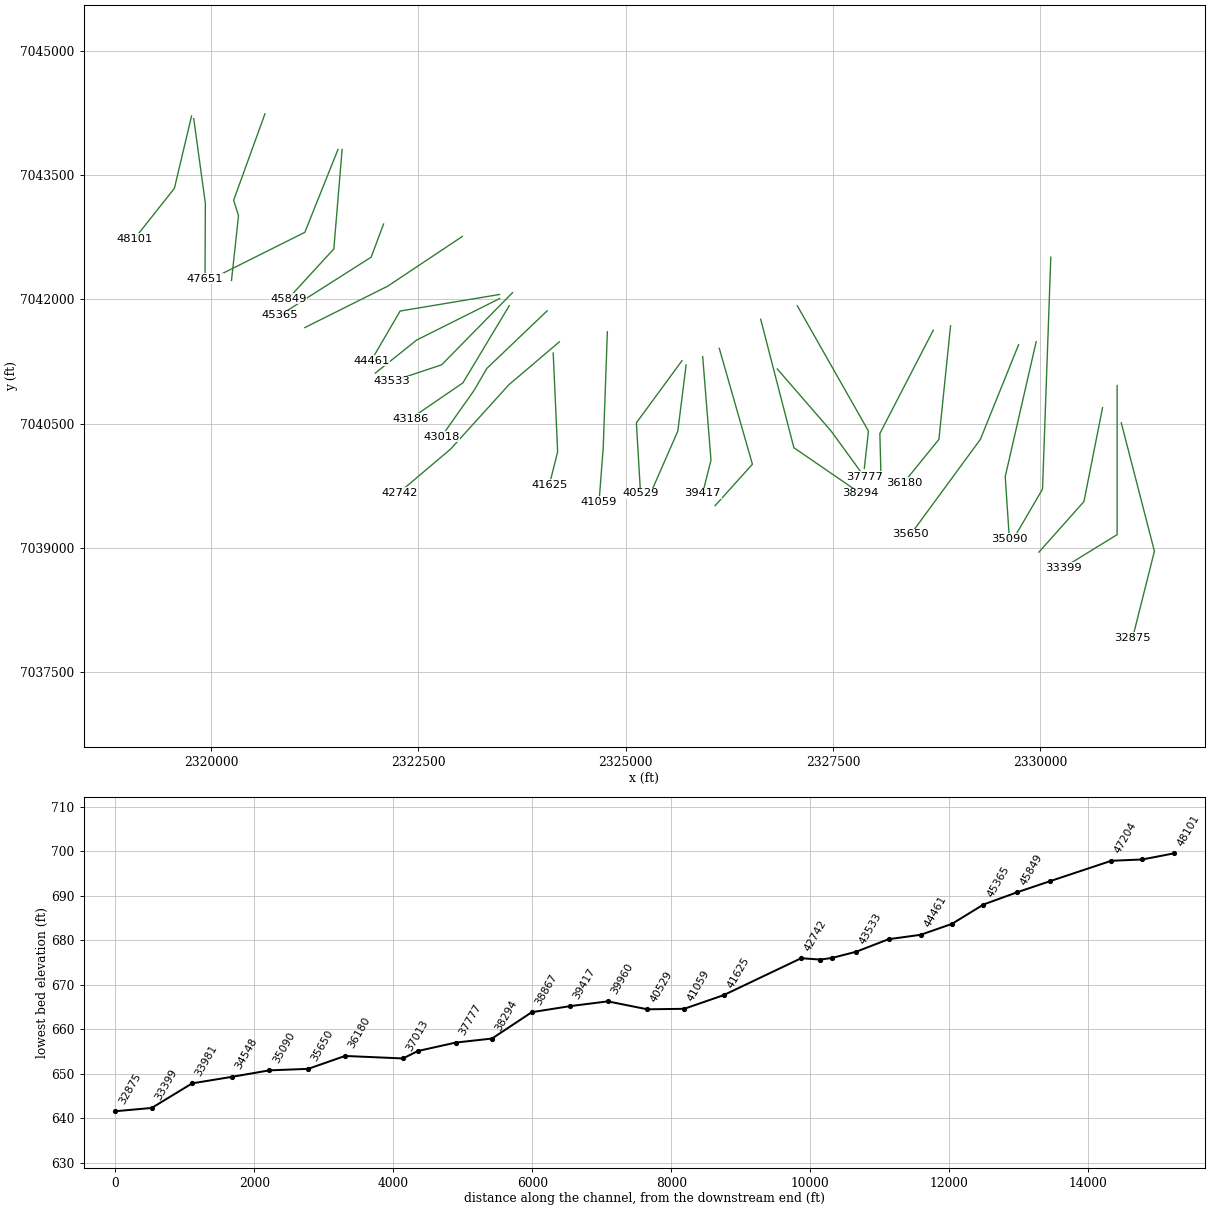
HEC-RAS study Henrietta Creek.prj: Henrietta Creek Base Level Engineering

--- Henrietta Creek.g01 (geometry) --- (continued)

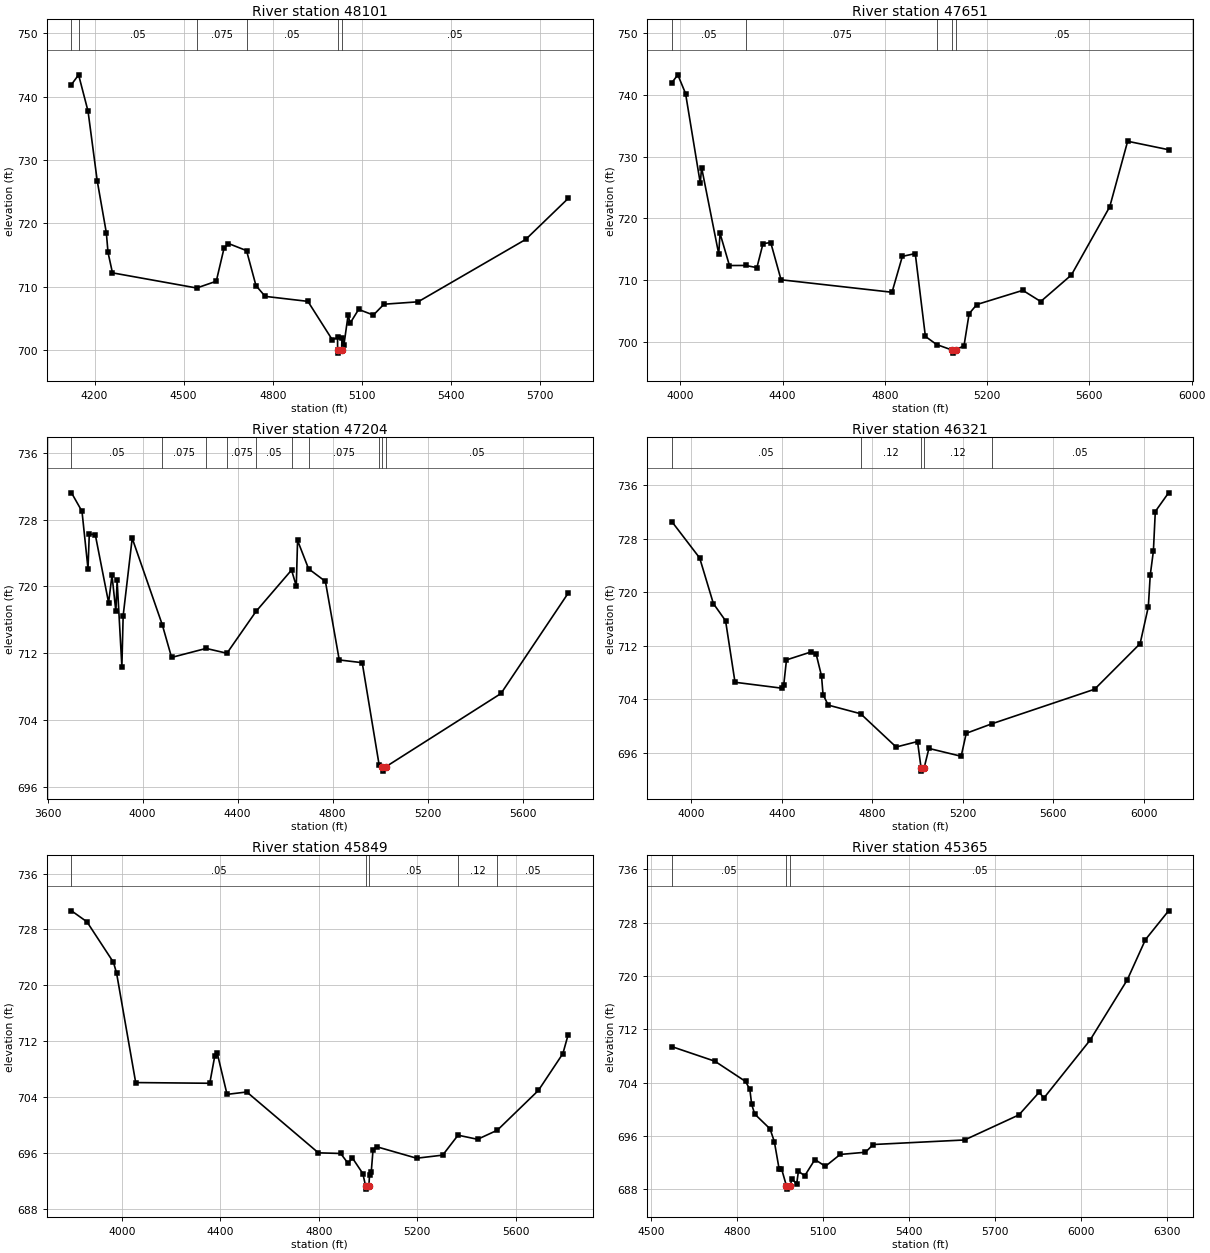
Type RM Length L Ch R = 1,48101,450,450,450
BEGIN DESCRIPTION:
Henrietta Creek 76.0
END DESCRIPTION:
XS GIS Cut Line= 3
      2319762.47      7044214.18      2319555.23      7043340.53
      2319074.55      7042734.26
#Sta/Elev= 30
  4122.4  741.92  4146.3  743.45  4178.1  737.70  4208.9  726.75  4239.7  718.51
  4245.3  715.42  4260.3  712.19  4543.9  709.80  4609.7  710.87  4635.6  716.04
  4650.8  716.82  4711.6  715.70  4743.3  710.18  4774.2  708.48  4918.1  707.69
  5000.3  701.62  5018.0  701.99  5018.1  700.02  5020.0  699.52  5031.5  700.02
  5032.9  701.96  5039.2  700.75  5053.7  705.61  5060.0  704.23  5088.9  706.42
  5138.6  705.53  5174.1  707.24  5289.0  707.62  5651.3  717.47  5794.0  723.93
#Mann=6,-1,0
  4122.4   0.075       0  4146.3    0.05       0  4543.9   0.075       0
  4711.6    0.05       0  5018.1   0.033       0  5031.5    0.05       0
Bank Sta=5018.1,5031.5
Exp/Cntr=0.3,0.1

Type RM Length L Ch R = 1,47651,447,447,447
BEGIN DESCRIPTION:
Henrietta Creek 75.0
END DESCRIPTION:
XS GIS Cut Line= 3
      2319788.65      7044182.75      2319929.00      7043160.00
      2319924.83      7042249.95
#Sta/Elev= 30
  3967.3  741.99  3990.3  743.24  4020.5  740.21  4078.1  725.68  4083.2  728.22
  4150.3  714.21  4155.3  717.56  4192.1  712.35  4255.2  712.36  4299.5  712.01
  4323.4  715.90  4353.6  716.07  4394.0  710.04  4828.0  708.02  4868.4  713.83
  4918.9  714.29  4958.5  700.87  5002.5  699.55  5062.9  698.66  5064.8  698.16
  5076.4  698.66  5109.6  699.36  5129.6  704.55  5159.6  706.03  5339.6  708.33
  5409.6  706.52  5529.6  710.82  5679.6  721.87  5749.6  732.48  5909.7  731.11
#Mann=5,-1,0
  3967.3    0.05       0  4255.2   0.075       0  5002.5    0.05       0
  5062.9    0.07       0  5076.4    0.05       0
Bank Sta=5062.9,5076.4
Exp/Cntr=0.3,0.1

Type RM Length L Ch R = 1,47204,883,883,883
BEGIN DESCRIPTION:
Henrietta Creek 74.0
END DESCRIPTION:
XS GIS Cut Line= 4
      2320647.67      7044240.37      2320270.53      7043198.01
      2320329.00      7043010.00      2320244.35      7042229.06
#Sta/Elev= 30
  3700.8  731.20  3745.0  728.98  3770.3  722.11  3775.7  726.26  3801.0  726.18
  3857.0  718.04  3871.3  721.31  3887.6  716.99  3892.9  720.70  3912.9  710.39
  3918.3  716.47  3956.4  725.76  4083.1  715.39  4122.2  711.48  4267.6  712.56
  4355.2  711.98  4477.6  716.99  4627.3  721.95  4647.2  720.03  4652.6  725.50
  4698.9  722.10  4769.8  720.59  4828.1  711.18  4924.8  710.85  4996.4  698.54
  5009.4  698.36  5011.4  697.86  5023.0  698.36  5509.1  707.16  5791.7  719.17
#Mann=10,-1,0
  3700.8    0.05       0  4083.1   0.075       0  4267.6    0.05       0
  4355.2   0.075       0  4477.6    0.05       0  4627.3     0.1       0
  4698.9   0.075       0  4996.4    0.05       0  5009.4   0.033       0
  5023.0    0.05       0
Bank Sta=5009.4,5023
Exp/Cntr=0.3,0.1

Type RM Length L Ch R = 1,46321,472,472,472
BEGIN DESCRIPTION:
Henrietta Creek 73.0
END DESCRIPTION:
XS GIS Cut Line= 3
      2321529.01      7043810.02      2321129.00      7042810.00
      2320128.99      7042310.00
#Sta/Elev= 30
  3914.5  730.51  4037.0  725.10  4097.6  718.29  4151.5  715.72  4193.2  706.54
  4399.2  705.66  4408.6  706.16  4420.7  709.88  4528.4  711.06  4551.3  710.82
  4575.6  707.48  4582.3  704.70  4605.2  703.13  4748.4  701.84  4905.4  696.87
  4999.9  697.69  5015.5  693.77  5017.4  693.27  5029.2  693.77  5050.3  696.66
  5192.8  695.49  5215.2  698.92  5327.6  700.33  5782.6  705.50  5983.8  712.31
  6020.1  717.82  6028.5  722.53  6042.5  726.13  6050.9  732.04  6109.6  734.83
#Mann=5,-1,0
  3914.5    0.05       0  4748.4    0.12       0  5015.5    0.07       0
  5029.2    0.12       0  5327.6    0.05       0
Bank Sta=5015.5,5029.2
Exp/Cntr=0.3,0.1

Type RM Length L Ch R = 1,45849,484,484,484
BEGIN DESCRIPTION:
Henrietta Creek 72.0
END DESCRIPTION:
XS GIS Cut Line= 3
      2321579.00      7043809.96      2321479.00      7042610.00
      2320928.97      7042009.97
#Sta/Elev= 30
  3795.1  730.66  3857.8  729.09  3965.6  723.28  3978.2  721.75  4056.0  706.05
  4357.0  705.95  4377.1  709.82  4387.1  710.30  4427.2  704.36  4507.5  704.70
  4798.5  695.98  4888.8  695.89  4918.9  694.48  4936.5  695.25  4979.1  693.00
  4989.9  691.28  4991.8  690.78  5003.6  691.28  5006.3  692.83  5013.1  693.21
  5020.5  696.43  5034.7  696.86  5197.5  695.21  5303.5  695.65  5365.9  698.51
  5445.3  697.92  5525.8  699.23  5692.6  704.93  5791.9  710.20  5813.2  712.89
#Mann=5,-1,0
  3795.1    0.05       0  4989.9   0.033       0  5003.6    0.05       0
  5365.9    0.12       0  5525.8    0.05       0
Bank Sta=4989.9,5003.6
Exp/Cntr=0.3,0.1

Type RM Length L Ch R = 1,45365,453,453,453
BEGIN DESCRIPTION:
Henrietta Creek 71.0
END DESCRIPTION:
XS GIS Cut Line= 3
      2322079.01      7042910.03      2321929.00      7042510.00
      2320828.98      7041809.98
#Sta/Elev= 30
  4573.0  709.39  4722.6  707.21  4829.4  704.18  4844.5  702.99  4850.7  700.77
  4861.4  699.29  4914.8  697.07  4929.9  695.15  4946.8  690.99  4954.8  691.11
  4971.9  688.53  4973.9  688.03  4985.9  688.53  4990.4  689.55  5007.9  688.87
  5013.8  690.71  5035.8  690.03  5071.3  692.47  5107.8  691.45  5159.4  693.23
  5247.5  693.56  5274.5  694.72  5592.9  695.40  5782.5  699.16  5853.7  702.59
  5868.9  701.66  6029.8  710.33  6160.1  719.41  6223.6  725.45  6304.1  729.76
#Mann=3,-1,0
  4573.0    0.05       0  4971.9    0.04       0  4985.9    0.05       0
Bank Sta=4971.9,4985.9
Exp/Cntr=0.3,0.1

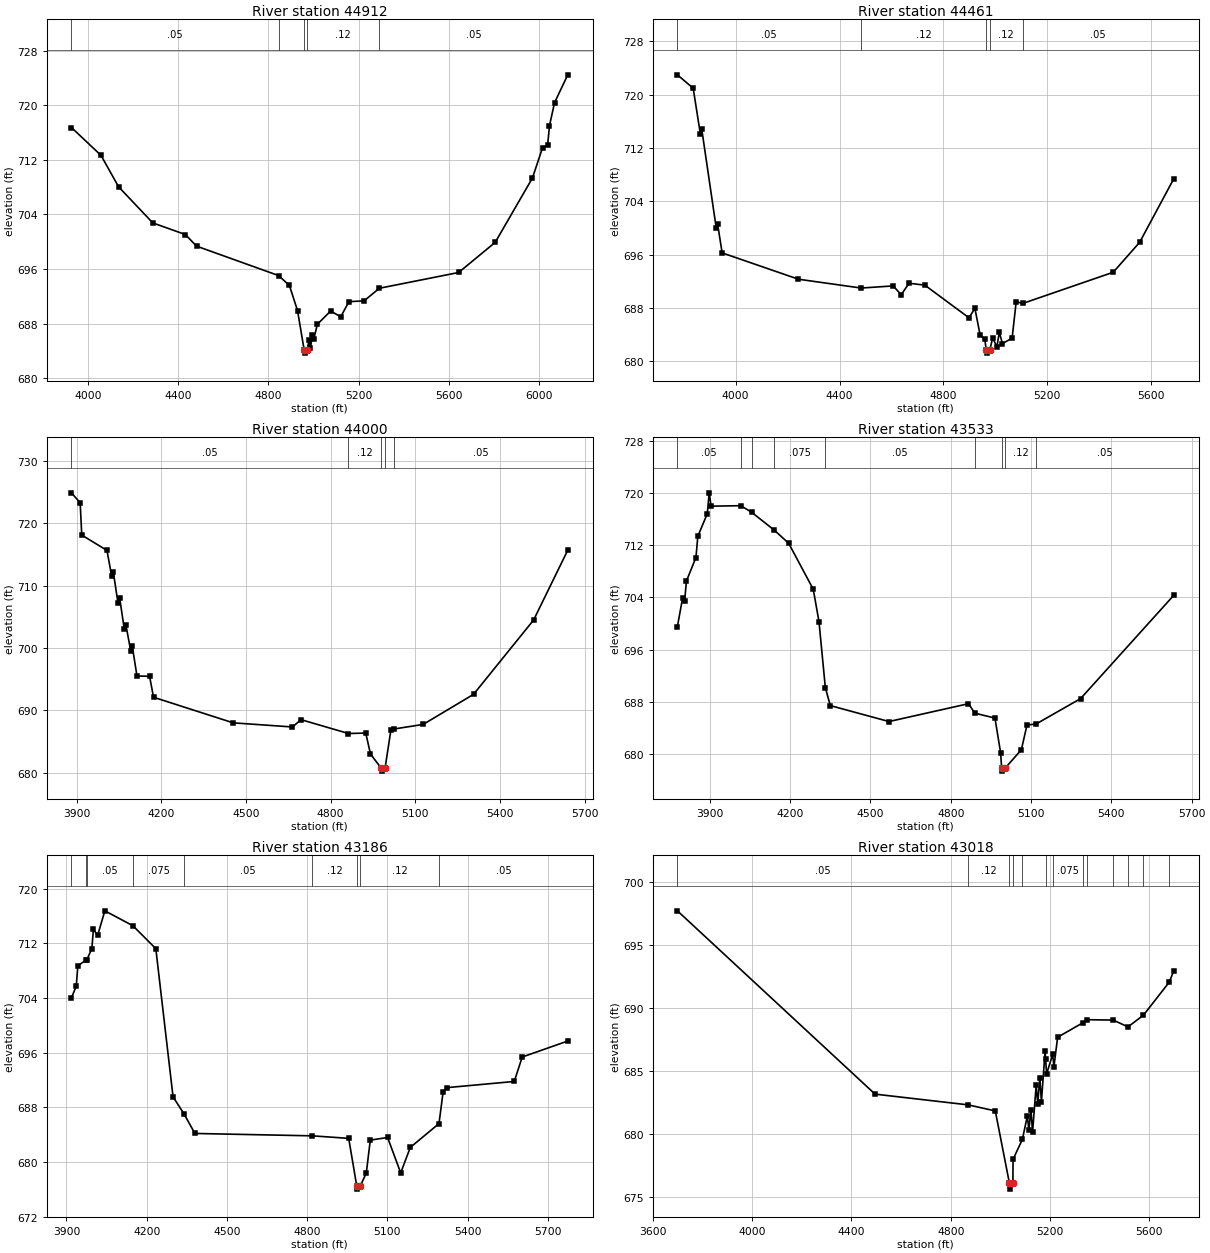
Type RM Length L Ch R = 1,44912,451,451,451
BEGIN DESCRIPTION:
Henrietta Creek 70.0
END DESCRIPTION:
XS GIS Cut Line= 3
      2323028.97      7042759.98      2322129.00      7042160.00
      2321128.97      7041659.98
#Sta/Elev= 30
  3927.8  716.72  4058.5  712.65  4136.6  708.04  4288.3  702.75  4432.5  701.05
  4482.1  699.35  4845.7  695.04  4893.7  693.59  4929.8  689.90  4958.9  684.18
  4960.9  683.68  4972.9  684.18  4980.9  685.66  4986.9  684.43  4995.9  686.40
  5001.9  685.76  5017.8  687.91  5076.5  689.85  5121.2  689.00  5157.6  691.22
  5224.6  691.33  5292.4  693.18  5643.9  695.49  5806.0  699.91  5970.9  709.33
  6015.7  713.77  6038.0  714.09  6046.4  716.99  6068.8  720.36  6127.5  724.44
#Mann=5,-1,0
  3927.8    0.05       0  4845.7    0.12       0  4958.9    0.07       0
  4972.9    0.12       0  5292.4    0.05       0
Bank Sta=4958.9,4972.9
Exp/Cntr=0.3,0.1

Type RM Length L Ch R = 1,44461,461,461,461
BEGIN DESCRIPTION:
Henrietta Creek 69.0
END DESCRIPTION:
XS GIS Cut Line= 3
      2323478.97      7042060.00      2322279.00      7041860.00
      2321929.02      7041260.04
#Sta/Elev= 30
  3775.7  722.95  3836.5  720.94  3864.4  714.02  3869.5  714.79  3925.2  700.00
  3930.3  700.64  3948.0  696.25  4242.0  692.30  4483.3  690.98  4607.0  691.30
  4637.4  689.97  4667.8  691.70  4728.6  691.41  4898.5  686.52  4921.3  687.94
  4941.5  683.91  4959.3  683.31  4965.0  681.72  4967.0  681.22  4979.0  681.72
  4989.7  683.51  5005.9  682.16  5015.4  684.32  5027.4  682.66  5064.6  683.46
  5080.3  688.93  5105.6  688.67  5454.1  693.35  5555.8  697.84  5686.8  707.34
#Mann=5,-1,0
  3775.7    0.05       0  4483.3    0.12       0  4965.0    0.07       0
  4979.0    0.12       0  5105.6    0.05       0
Bank Sta=4965,4979
Exp/Cntr=0.3,0.1

Type RM Length L Ch R = 1,44000,467,467,467
BEGIN DESCRIPTION:
Henrietta Creek 68.0
END DESCRIPTION:
XS GIS Cut Line= 3
      2323479.03      7042010.02      2322479.00      7041510.00
      2321978.99      7041109.99
#Sta/Elev= 30
  3881.9  724.91  3912.7  723.30  3918.3  718.13  4007.7  715.66  4024.5  711.48
  4030.1  712.19  4046.8  707.18  4052.4  708.08  4069.2  702.97  4074.8  703.68
  4091.6  699.59  4097.2  700.32  4113.9  695.50  4158.6  695.46  4172.6  692.09
  4454.9  687.98  4664.6  687.32  4695.3  688.49  4863.3  686.27  4924.5  686.34
  4941.3  682.98  4978.9  680.73  4980.9  680.23  4993.0  680.73  5013.6  686.82
  5024.0  686.99  5128.0  687.73  5306.5  692.56  5519.4  704.50  5640.3  715.71
#Mann=5,-1,0
  3881.9    0.05       0  4863.3    0.12       0  4978.9    0.07       0
  4993.0    0.12       0  5024.0    0.05       0
Bank Sta=4978.9,4993
Exp/Cntr=0.3,0.1

Type RM Length L Ch R = 1,43533,347,347,347
BEGIN DESCRIPTION:
Henrietta Creek 67.0
END DESCRIPTION:
XS GIS Cut Line= 3
      2323635.13      7042081.88      2322779.00      7041210.00
      2322178.99      7041010.00
#Sta/Elev= 30
  3778.5  699.54  3798.3  703.98  3805.4  703.46  3812.4  706.52  3847.8  710.11
  3854.8  713.35  3890.3  716.83  3897.3  720.01  3904.4  717.97  4015.5  718.04
  4055.7  717.04  4140.1  714.31  4194.3  712.29  4286.2  705.24  4307.5  700.31
  4331.3  690.19  4349.9  687.44  4569.1  685.00  4866.1  687.73  4890.0  686.28
  4965.1  685.53  4986.4  680.17  4989.9  677.91  4991.9  677.41  5004.0  677.91
  5063.7  680.68  5084.8  684.47  5119.0  684.63  5285.0  688.51  5632.9  704.31
#Mann=9,-1,0
  3778.5    0.05       0  4015.5   0.075       0  4055.7    0.05       0
  4140.1   0.075       0  4331.3    0.05       0  4890.0    0.12       0
  4989.9    0.07       0  5004.0    0.12       0  5119.0    0.05       0
Bank Sta=4989.9,5004
Exp/Cntr=0.3,0.1

Type RM Length L Ch R = 1,43186,168,168,168
BEGIN DESCRIPTION:
Henrietta Creek 66.0
END DESCRIPTION:
XS GIS Cut Line= 3
      2323596.05      7041925.62      2323036.14      7040992.44
      2322403.23      7040558.94
#Sta/Elev= 30
  3919.0  704.02  3936.9  705.75  3942.7  708.71  3974.9  709.59  3975.7  709.54
  3995.2  711.22  4001.0  714.08  4016.6  713.15  4043.8  716.76  4148.9  714.57
  4234.3  711.22  4298.7  689.53  4339.6  687.04  4380.4  684.17  4819.9  683.82
  4955.4  683.45  4985.3  676.52  4987.3  676.02  4999.4  676.52  5021.2  678.39
  5036.1  683.19  5100.8  683.58  5149.8  678.40  5185.7  682.13  5292.9  685.61
  5308.2  690.20  5323.1  690.88  5574.3  691.78  5604.1  695.36  5774.4  697.70
#Mann=9,-1,0
  3919.0    0.05       0  3974.9   0.075       0  3975.7    0.05       0
  4148.9   0.075       0  4339.6    0.05       0  4819.9    0.12       0
  4985.3    0.07       0  4999.4    0.12       0  5292.9    0.05       0
Bank Sta=4985.3,4999.4
Exp/Cntr=0.3,0.1

Type RM Length L Ch R = 1,43018,276,276,276
BEGIN DESCRIPTION:
Henrietta Creek 65.0
END DESCRIPTION:
XS GIS Cut Line= 4
      2324052.22      7041862.35      2323325.20      7041167.06
      2323170.69      7040901.29      2322775.71      7040341.39
#Sta/Elev= 30
  3699.3  697.71  4495.3  683.18  4869.8  682.33  4979.5  681.85  5036.1  676.15
  5038.1  675.65  5050.4  676.15  5051.0  678.01  5088.7  679.60  5108.6  681.45
  5114.7  680.34  5123.3  681.94  5129.5  680.15  5144.3  683.91  5150.4  682.41
  5159.0  684.49  5165.2  682.57  5180.0  686.57  5182.0  685.98  5186.1  684.78
  5210.5  686.33  5215.7  685.36  5230.5  687.69  5332.4  688.84  5347.9  689.08
  5454.3  689.05  5513.8  688.51  5576.2  689.44  5679.7  692.05  5697.9  692.93
#Mann=13,-1,0
  3699.3    0.05       0  4869.8    0.12       0  5036.1    0.07       0
  5050.4    0.12       0  5088.7    0.05       0  5182.0    0.12       0
  5210.5   0.075       0  5332.4    0.05       0  5347.9   0.075       0
  5454.3    0.05       0  5513.8   0.075       0  5576.2    0.05       0
  5679.7   0.075       0
Bank Sta=5036.1,5050.4
Exp/Cntr=0.3,0.1

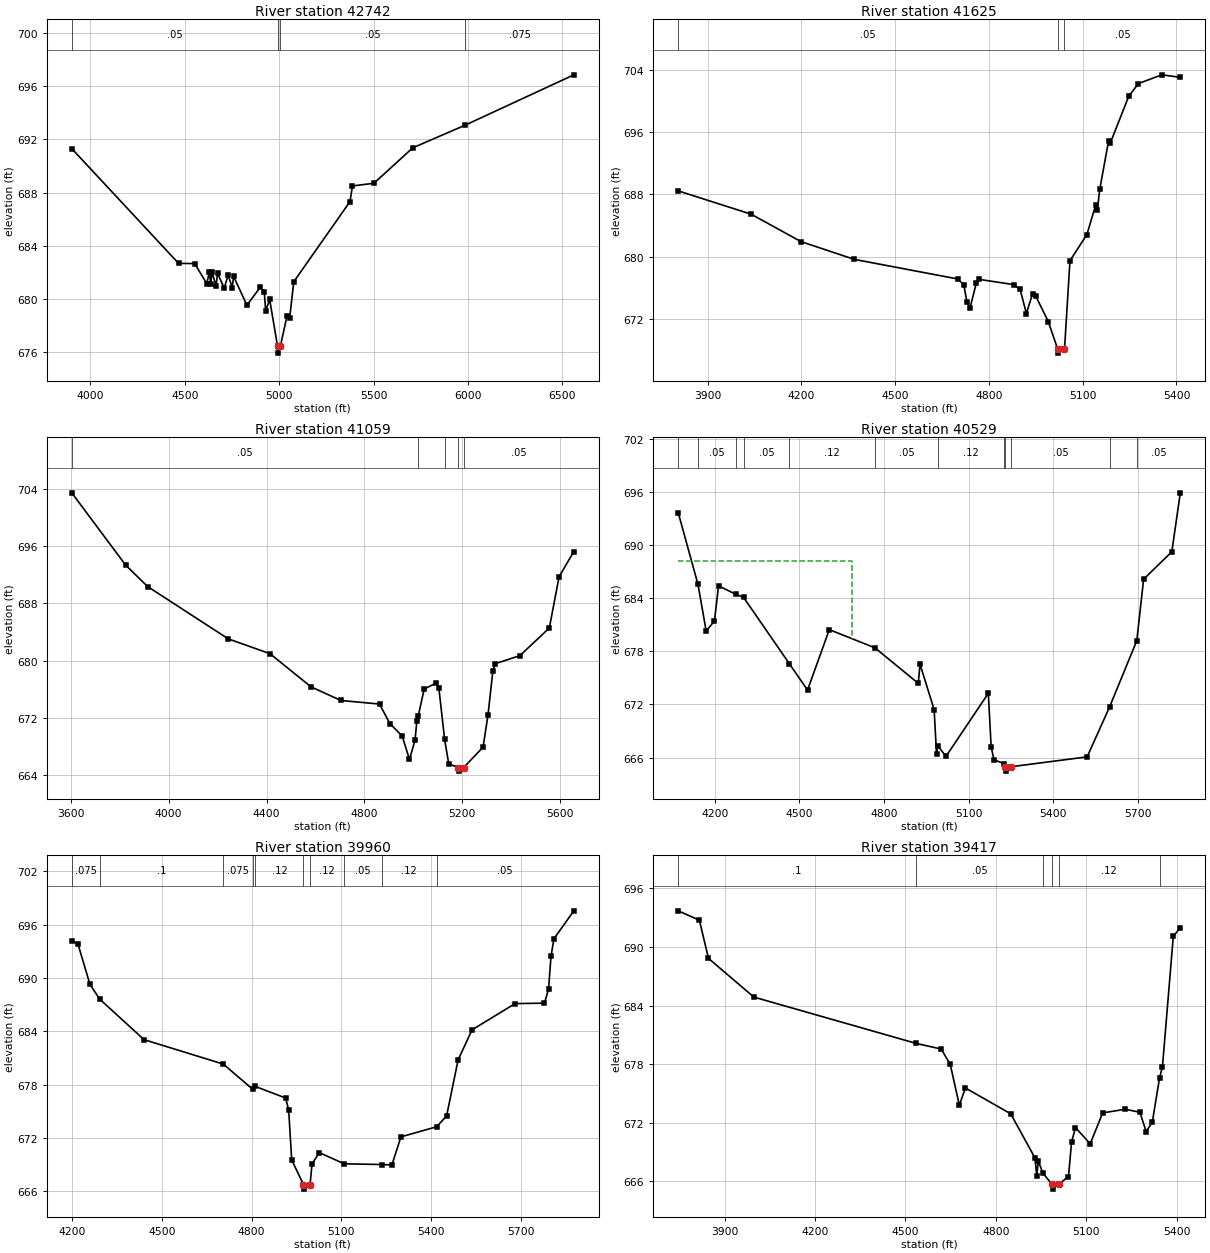
Type RM Length L Ch R = 1,42742,1117,1117,1117
BEGIN DESCRIPTION:
Henrietta Creek 64.5
END DESCRIPTION:
XS GIS Cut Line= 4
      2324199.36      7041487.26      2323591.69      7040970.74
      2322888.57      7040193.83      2322267.91      7039668.66
#Sta/Elev= 30
  3901.7  691.30  4467.1  682.69  4552.8  682.67  4616.5  681.17  4630.7  682.06
  4637.3  681.13  4645.0  682.02  4665.9  680.98  4673.6  681.95  4708.8  680.82
  4729.8  681.81  4751.4  680.86  4758.2  681.72  4829.1  679.55  4900.1  680.90
  4921.1  680.51  4928.5  679.11  4949.4  679.98  4991.6  676.45  4993.6  675.95
  5005.9  676.45  5041.4  678.74  5055.5  678.60  5077.2  681.31  5374.6  687.32
  5388.1  688.50  5501.6  688.70  5707.1  691.36  5986.0  693.07  6560.1  696.84
#Mann=4,-1,0
  3901.7    0.05       0  4991.6   0.033       0  5005.9    0.05       0
  5986.0   0.075       0
Bank Sta=4991.6,5005.9
Exp/Cntr=0.3,0.1

Type RM Length L Ch R = 1,41625,566,566,566
BEGIN DESCRIPTION:
Henrietta Creek 64.0
END DESCRIPTION:
XS GIS Cut Line= 3
      2324125.55      7041352.70      2324179.00      7040160.00
      2324079.00      7039760.01
#Sta/Elev= 30
  3806.1  688.44  4039.0  685.46  4199.2  681.93  4369.4  679.66  4699.7  677.15
  4719.7  676.43  4729.7  674.16  4739.7  673.46  4759.8  676.63  4769.8  677.09
  4879.9  676.42  4899.9  675.80  4919.9  672.72  4939.9  675.28  4949.9  674.94
  4990.0  671.69  5020.1  668.14  5022.3  667.64  5041.8  668.14  5059.3  679.49
  5113.4  682.84  5141.7  686.64  5146.9  686.02  5154.6  688.65  5183.0  694.88
  5188.1  694.55  5247.4  700.58  5278.3  702.20  5353.0  703.32  5412.3  703.00
#Mann=3,-1,0
  3806.1    0.05       0  5020.1   0.033       0  5041.8    0.05       0
Bank Sta=5020.1,5041.8
Exp/Cntr=0.3,0.1

Type RM Length L Ch R = 1,41059,530,530,530
BEGIN DESCRIPTION:
Henrietta Creek 63.0
END DESCRIPTION:
XS GIS Cut Line= 3
      2324779.00      7041609.95      2324729.00      7040210.00
      2324679.00      7039559.96
#Sta/Elev= 30
  3603.8  703.42  3823.9  693.34  3913.9  690.34  4244.2  683.03  4414.3  680.97
  4581.9  676.34  4704.5  674.44  4862.1  673.94  4904.6  671.21  4954.6  669.49
  4984.6  666.21  5007.2  668.90  5014.7  671.58  5020.3  672.26  5044.8  676.05
  5094.9  676.88  5104.9  676.12  5128.3  669.00  5145.1  665.59  5184.4  665.08
  5186.6  664.58  5206.1  665.08  5285.5  667.93  5305.5  672.39  5325.6  678.59
  5335.6  679.58  5435.9  680.70  5556.3  684.55  5596.4  691.72  5656.6  695.23
#Mann=5,-1,0
  3603.8    0.05       0  5020.3    0.12       0  5128.3    0.05       0
  5184.4   0.033       0  5206.1    0.05       0
Bank Sta=5184.4,5206.1
Exp/Cntr=0.3,0.1

Type RM Length L Ch R = 1,40529,569,569,569
BEGIN DESCRIPTION:
Henrietta Creek 62.0
END DESCRIPTION:
XS GIS Cut Line= 3
      2325678.97      7041259.96      2325129.00      7040510.00
      2325179.00      7039659.98
#Sta/Elev= 30
  4070.0  693.67  4140.1  685.57  4169.2  680.29  4198.5  681.45  4213.1  685.41
  4273.8  684.46  4302.0  684.10  4464.0  676.62  4528.8  673.63  4606.0  680.46
  4768.2  678.40  4921.7  674.39  4927.9  676.55  4978.0  671.42  4986.5  666.44
  4990.9  667.34  5020.0  666.13  5170.3  673.27  5180.3  667.21  5190.3  665.75
  5225.4  665.33  5229.5  664.97  5231.7  664.47  5251.3  664.97  5520.9  666.08
  5600.5  671.72  5697.1  679.21  5721.3  686.16  5821.4  689.26  5851.5  695.92
#Mann=12,-1,0
  4070.0   0.075       0  4140.1    0.05       0  4273.8   0.075       0
  4302.0    0.05       0  4464.0    0.12       0  4768.2    0.05       0
  4990.9    0.12       0  5225.4    0.05       0  5229.5    0.07       0
  5251.3    0.05       0  5600.5    0.12       0  5697.1    0.05       0
#XS Ineff=2,0
    0.00 4686.90  688.21               0
Permanent Ineff=
       F       F
Bank Sta=5229.5,5251.3
Exp/Cntr=0.3,0.1

Type RM Length L Ch R = 1,39960,543,543,543
BEGIN DESCRIPTION:
Henrietta Creek 61.0
END DESCRIPTION:
XS GIS Cut Line= 3
      2325729.00      7041210.02      2325629.00      7040410.00
      2325278.98      7039609.96
#Sta/Elev= 30
  4198.3  694.16  4218.5  693.89  4258.8  689.33  4291.4  687.64  4440.2  683.07
  4705.3  680.32  4804.2  677.47  4812.8  677.80  4913.8  676.50  4923.9  675.14
  4934.0  669.54  4973.4  666.75  4975.6  666.25  4995.4  666.75  5002.0  669.08
  5026.4  670.36  5109.7  669.10  5234.9  669.02  5269.2  668.97  5299.3  672.13
  5418.8  673.27  5452.1  674.48  5490.7  680.80  5537.4  684.18  5681.3  687.13
  5779.5  687.18  5793.2  688.76  5801.4  692.46  5811.1  694.42  5877.8  697.57
#Mann=10,-1,0
  4198.3   0.075       0  4291.4     0.1       0  4705.3   0.075       0
  4804.2    0.05       0  4812.8    0.12       0  4973.4    0.07       0
  4995.4    0.12       0  5109.7    0.05       0  5234.9    0.12       0
  5418.8    0.05       0
Bank Sta=4973.4,4995.4
Exp/Cntr=0.3,0.1

Type RM Length L Ch R = 1,39417,550,550,550
BEGIN DESCRIPTION:
Henrietta Creek 60.0
END DESCRIPTION:
XS GIS Cut Line= 3
      2325929.00      7041309.95      2326029.00      7040060.00
      2325928.99      7039659.96
#Sta/Elev= 30
  3745.8  693.71  3816.0  692.75  3846.1  688.84  3996.6  684.87  4535.2  680.12
  4618.5  679.54  4648.6  677.97  4678.7  673.78  4698.8  675.55  4849.3  672.90
  4929.5  668.39  4935.8  666.57  4940.8  668.08  4955.7  666.83  4986.2  665.68
  4988.4  665.18  5008.2  665.68  5041.0  666.47  5051.3  670.04  5064.2  671.48
  5113.1  669.83  5154.4  672.99  5229.1  673.37  5278.1  673.06  5298.7  671.07
  5319.3  672.07  5343.4  676.62  5352.8  677.72  5388.9  691.12  5412.1  691.96
#Mann=6,-1,0
  3745.8     0.1       0  4535.2    0.05       0  4955.7    0.12       0
  4986.2    0.07       0  5008.2    0.12       0  5343.4     0.1       0
Bank Sta=4986.2,5008.2
Exp/Cntr=0.3,0.1

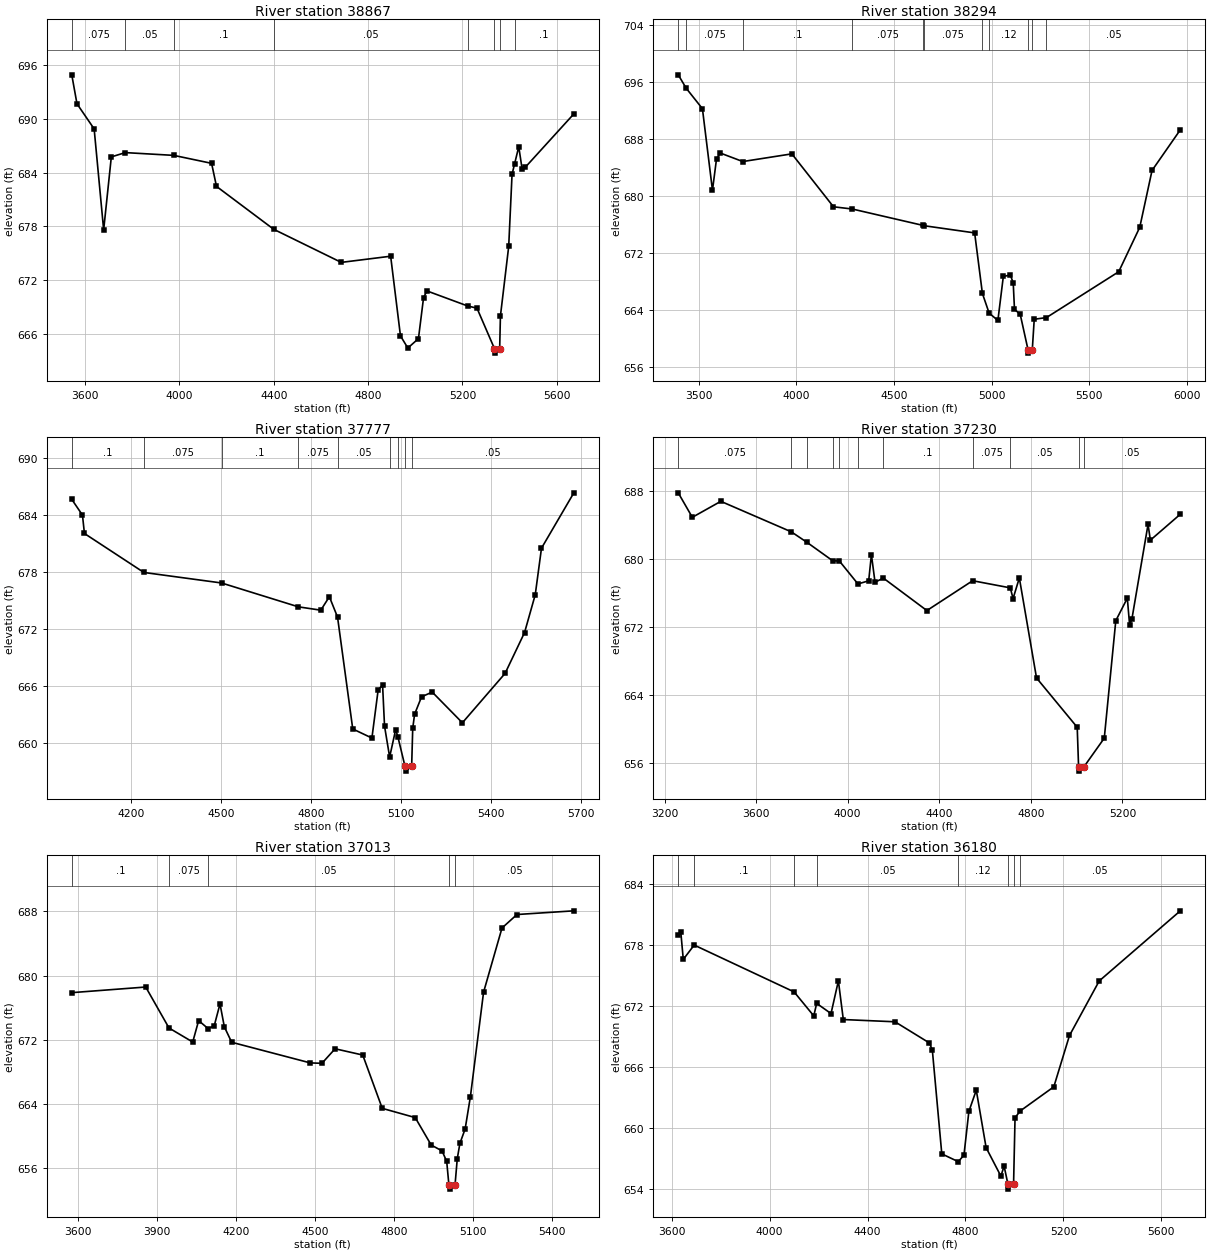
Type RM Length L Ch R = 1,38867,573,573,573
BEGIN DESCRIPTION:
Henrietta Creek 59.0
END DESCRIPTION:
XS GIS Cut Line= 3
      2326129.01      7041409.97      2326529.00      7040010.00
      2326078.98      7039509.98
#Sta/Elev= 30
  3543.5  694.95  3565.6  691.71  3638.4  688.90  3678.7  677.60  3711.2  685.77
  3770.5  686.25  3975.9  685.94  4136.3  685.05  4157.1  682.47  4399.8  677.67
  4686.2  673.97  4895.5  674.66  4937.1  665.75  4968.3  664.39  5013.3  665.44
  5035.0  670.02  5049.2  670.78  5222.4  669.09  5261.5  668.85  5335.7  664.32
  5337.9  663.82  5357.7  664.32  5360.9  667.97  5396.0  675.75  5410.2  683.82
  5420.6  684.95  5438.6  686.91  5452.8  684.43  5467.0  684.63  5672.2  690.58
#Mann=8,-1,0
  3543.5   0.075       0  3770.5    0.05       0  3975.9     0.1       0
  4399.8    0.05       0  5222.4    0.12       0  5335.7    0.04       0
  5357.7    0.12       0  5420.6     0.1       0
Bank Sta=5335.7,5357.7
Exp/Cntr=0.3,0.1

Type RM Length L Ch R = 1,38294,517,517,517
BEGIN DESCRIPTION:
Henrietta Creek 58.0
END DESCRIPTION:
XS GIS Cut Line= 3
      2326629.00      7041760.02      2327029.00      7040210.00
      2327828.98      7039660.01
#Sta/Elev= 30
  3394.3  697.01  3435.5  695.11  3518.2  692.25  3569.6  680.78  3590.5  685.22
  3610.2  686.01  3724.9  684.82  3976.2  685.90  4189.5  678.46  4285.3  678.15
  4648.7  675.84  4650.9  675.81  4912.5  674.79  4952.2  666.28  4986.6  663.52
  5031.5  662.48  5059.4  668.67  5095.2  668.87  5110.1  667.77  5116.5  664.06
  5146.0  663.33  5185.7  658.39  5187.9  657.89  5207.8  658.39  5217.7  662.65
  5280.5  662.89  5650.4  669.33  5758.2  675.58  5821.1  683.57  5965.9  689.28
#Mann=11,-1,0
  3394.3     0.1       0  3435.5   0.075       0  3724.9     0.1       0
  4285.3   0.075       0  4648.7     0.1       0  4650.9   0.075       0
  4952.2    0.05       0  4986.6    0.12       0  5185.7    0.07       0
  5207.8    0.12       0  5280.5    0.05       0
Bank Sta=5185.7,5207.8
Exp/Cntr=0.3,0.1

Type RM Length L Ch R = 1,37777,547,547,547
BEGIN DESCRIPTION:
Henrietta Creek 57.0
END DESCRIPTION:
XS GIS Cut Line= 3
      2326829.01      7041159.99      2327479.00      7040410.00
      2327878.98      7039860.03
#Sta/Elev= 30
  4002.8  685.67  4038.4  684.01  4045.0  682.07  4242.9  677.96  4501.6  676.85
  4757.9  674.33  4832.4  673.98  4860.9  675.40  4888.1  673.25  4938.8  661.45
  5002.6  660.49  5023.5  665.59  5038.2  666.06  5044.7  661.74  5061.7  658.49
  5081.8  661.39  5089.3  660.60  5112.9  657.50  5115.1  657.00  5135.0  657.50
  5138.6  661.52  5144.8  663.00  5168.0  664.84  5203.5  665.34  5304.0  662.10
  5446.2  667.31  5511.1  671.62  5546.7  675.61  5567.5  680.52  5675.3  686.36
#Mann=9,-1,0
  4002.8     0.1       0  4242.9   0.075       0  4501.6     0.1       0
  4757.9   0.075       0  4888.1    0.05       0  5061.7    0.12       0
  5089.3    0.05       0  5112.9    0.04       0  5135.0    0.05       0
Bank Sta=5112.9,5135
Exp/Cntr=0.3,0.1

Type RM Length L Ch R = 1,37230,217,217,217
BEGIN DESCRIPTION:
Henrietta Creek 56.0
END DESCRIPTION:
XS GIS Cut Line= 3
      2327070.42      7041923.53      2327929.00      7040410.00
      2327879.00      7039959.97
#Sta/Elev= 30
  3259.9  687.84  3321.4  684.96  3445.9  686.84  3753.9  683.25  3823.0  682.00
  3933.9  679.86  3964.1  679.81  4044.8  677.12  4091.7  677.49  4103.6  680.57
  4119.4  677.32  4155.7  677.81  4345.9  673.99  4545.8  677.50  4710.2  676.66
  4722.4  675.40  4749.7  677.83  4824.8  666.06  5002.5  660.26  5008.5  655.60
  5010.8  655.10  5031.7  655.60  5120.7  658.98  5171.0  672.80  5221.4  675.45
  5231.4  672.27  5241.5  673.02  5311.9  684.13  5322.0  682.27  5452.8  685.32
#Mann=11,-1,0
  3259.9   0.075       0  3753.9    0.05       0  3823.0   0.075       0
  3933.9     0.1       0  3964.1   0.075       0  4044.8    0.05       0
  4155.7     0.1       0  4545.8   0.075       0  4710.2    0.05       0
  5008.5   0.033       0  5031.7    0.05       0
Bank Sta=5008.5,5031.7
Exp/Cntr=0.3,0.1

Type RM Length L Ch R = 1,37013,833,833,833
BEGIN DESCRIPTION:
Henrietta Creek 55.0
END DESCRIPTION:
XS GIS Cut Line= 3
      2328711.06      7041628.41      2328066.52      7040380.46
      2328079.54      7039877.00
#Sta/Elev= 30
  3575.0  677.89  3856.1  678.59  3944.5  673.49  4034.7  671.74  4057.2  674.41
  4092.8  673.42  4116.2  673.74  4138.4  676.49  4154.9  673.63  4182.7  671.71
  4481.5  669.14  4525.8  669.09  4575.8  670.90  4680.9  670.12  4755.0  663.48
  4880.3  662.33  4941.1  658.91  4982.3  658.18  5000.0  656.87  5008.4  653.92
  5010.7  653.42  5031.6  653.92  5040.1  657.20  5050.1  659.11  5070.1  660.92
  5090.1  664.95  5140.1  677.95  5210.1  685.94  5267.0  687.62  5483.2  688.08
#Mann=5,-1,0
  3575.0     0.1       0  3944.5   0.075       0  4092.8    0.05       0
  5008.4   0.033       0  5031.6    0.05       0
Bank Sta=5008.4,5031.6
Exp/Cntr=0.3,0.1

Type RM Length L Ch R = 1,36180,530,530,530
BEGIN DESCRIPTION:
Henrietta Creek 54.0
END DESCRIPTION:
XS GIS Cut Line= 3
      2328919.39      7041680.52      2328779.00      7040310.00
      2328355.16      7039788.12
#Sta/Elev= 30
  3627.1  679.01  3637.7  679.24  3647.7  676.59  3692.2  678.00  4100.2  673.39
  4180.5  671.03  4192.3  672.26  4250.9  671.26  4281.0  674.48  4301.1  670.67
  4512.2  670.45  4653.0  668.36  4664.7  667.64  4703.2  657.45  4770.6  656.68
  4793.7  657.33  4813.8  661.63  4844.0  663.72  4884.2  658.06  4944.5  655.26
  4957.6  656.25  4973.1  654.48  4975.4  653.98  4996.3  654.48  5002.3  661.01
  5023.8  661.68  5160.6  664.05  5224.6  669.10  5346.0  674.47  5677.1  681.37
#Mann=8,-1,0
  3627.1   0.075       0  3692.2     0.1       0  4100.2   0.075       0
  4192.3    0.05       0  4770.6    0.12       0  4973.1    0.07       0
  4996.3    0.12       0  5023.8    0.05       0
Bank Sta=4973.1,4996.3
Exp/Cntr=0.3,0.1

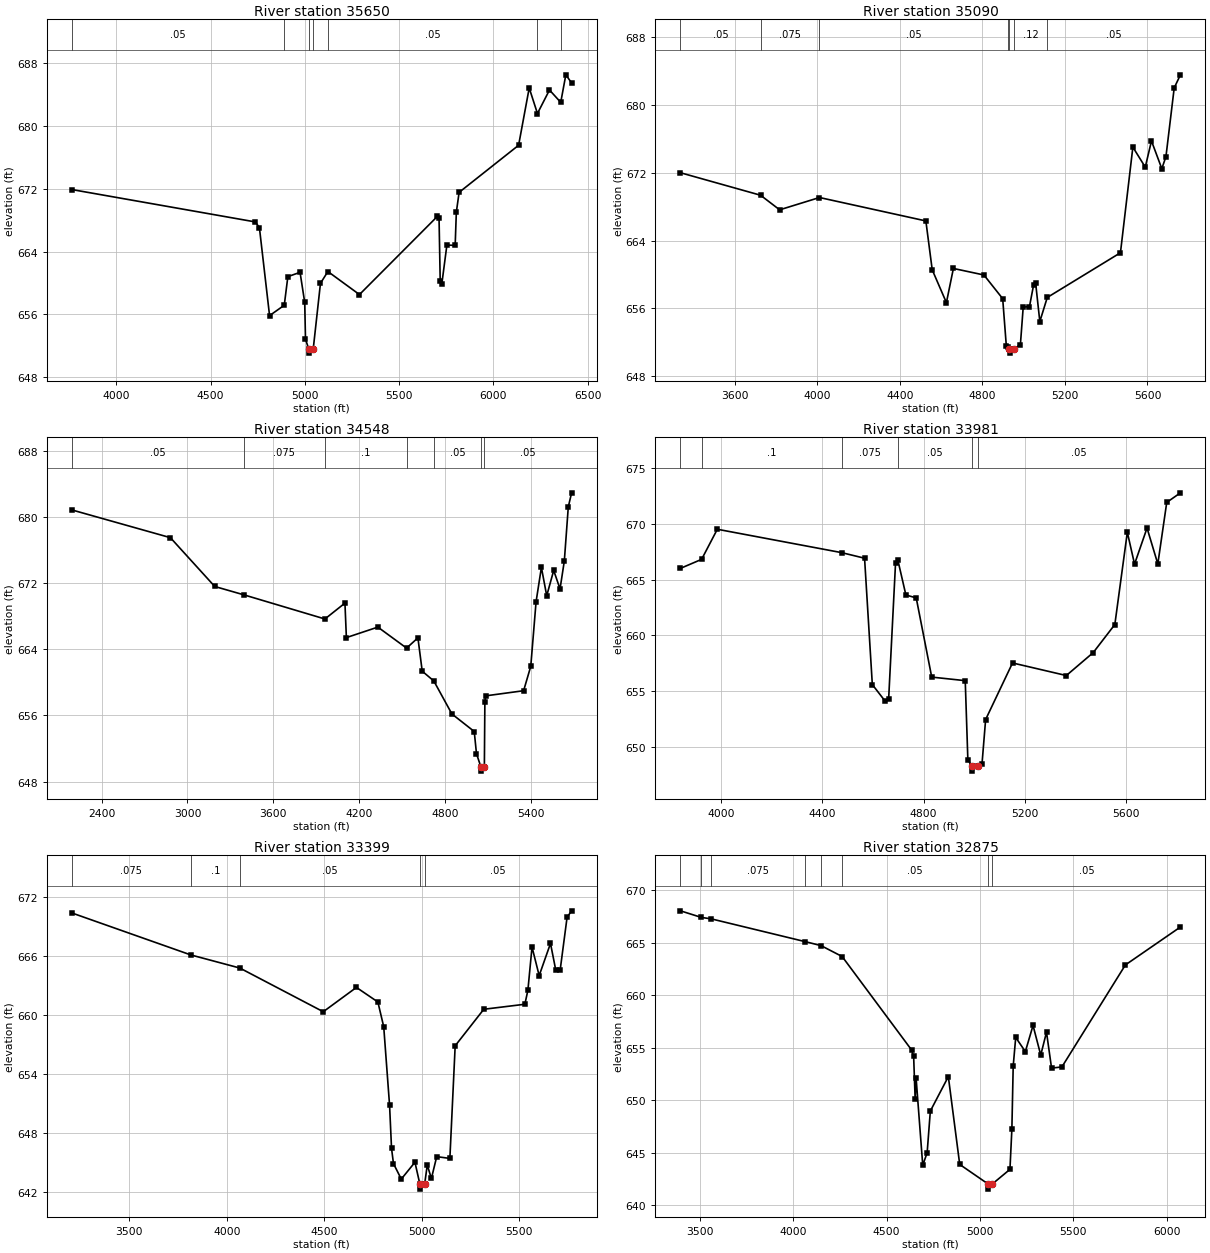
Type RM Length L Ch R = 1,35650,560,560,560
BEGIN DESCRIPTION:
Henrietta Creek 53.0
END DESCRIPTION:
XS GIS Cut Line= 3
      2329740.53      7041453.86      2329279.00      7040310.00
      2328439.80      7039165.20
#Sta/Elev= 30
  3762.7  671.89  4737.1  667.77  4758.9  667.05  4812.8  655.85  4890.8  657.17
  4909.9  660.81  4974.6  661.36  4999.3  657.53  5003.5  652.85  5021.1  651.58
  5023.5  651.08  5044.4  651.58  5082.9  659.96  5122.3  661.46  5289.8  658.53
  5703.6  668.48  5712.1  668.29  5718.3  660.23  5726.7  659.85  5753.8  664.83
  5797.7  664.78  5803.9  669.01  5818.6  671.53  6134.3  677.52  6190.6  684.81
  6234.3  681.56  6298.1  684.55  6357.9  682.98  6384.9  686.48  6415.6  685.45
#Mann=7,-1,0
  3762.7    0.05       0  4890.8    0.12       0  5021.1    0.07       0
  5044.4    0.12       0  5122.3    0.05       0  6234.3   0.075       0
  6357.9    0.05       0
Bank Sta=5021.1,5044.4
Exp/Cntr=0.3,0.1

Type RM Length L Ch R = 1,35090,542,542,542
BEGIN DESCRIPTION:
Henrietta Creek 52.0
END DESCRIPTION:
XS GIS Cut Line= 3
      2329952.36      7041489.47      2329579.00      7039860.00
      2329629.00      7039109.97
#Sta/Elev= 30
  3336.2  672.00  3724.4  669.35  3817.0  667.63  4010.1  669.08  4525.7  666.32
  4556.5  660.56  4625.3  656.69  4659.1  660.72  4807.1  659.95  4898.1  657.16
  4915.6  651.62  4924.1  651.52  4929.1  651.24  4931.5  650.74  4952.9  651.24
  4983.9  651.74  4997.6  656.17  5027.9  656.22  5048.0  658.79  5058.0  658.95
  5078.1  654.46  5114.2  657.30  5468.9  662.57  5529.1  675.02  5589.2  672.66
  5619.3  675.75  5669.4  672.48  5689.4  673.89  5729.5  682.00  5759.6  683.54
#Mann=7,-1,0
  3336.2    0.05       0  3724.4   0.075       0  4010.1    0.05       0
  4924.1    0.12       0  4929.1    0.07       0  4952.9    0.12       0
  5114.2    0.05       0
Bank Sta=4929.1,4952.9
Exp/Cntr=0.3,0.1

Type RM Length L Ch R = 1,34548,567,567,567
BEGIN DESCRIPTION:
Henrietta Creek 51.0
END DESCRIPTION:
XS GIS Cut Line= 3
      2330129.00      7042510.00      2330029.00      7039710.00
      2329679.00      7039110.00
#Sta/Elev= 30
  2190.4  680.85  2880.8  677.49  3191.0  671.59  3394.7  670.58  3961.6  667.66
  4101.6  669.58  4111.6  665.41  4331.8  666.68  4532.6  664.14  4611.9  665.38
  4642.0  661.35  4723.1  660.17  4849.6  656.18  5005.8  654.06  5021.5  651.38
  5052.5  649.77  5054.9  649.27  5076.6  649.77  5080.2  657.67  5086.0  658.37
  5351.1  658.99  5401.1  661.94  5438.3  669.75  5475.5  673.89  5512.7  670.47
  5561.5  673.53  5605.8  671.29  5635.9  674.68  5663.6  681.22  5686.8  682.91
#Mann=7,-1,0
  2190.4    0.05       0  3394.7   0.075       0  3961.6     0.1       0
  4532.6   0.075       0  4723.1    0.05       0  5052.5   0.033       0
  5076.6    0.05       0
Bank Sta=5052.5,5076.6
Exp/Cntr=0.3,0.1

Type RM Length L Ch R = 1,33981,582,582,582
BEGIN DESCRIPTION:
Henrietta Creek 50.0
END DESCRIPTION:
XS GIS Cut Line= 3
      2330753.16      7040693.00      2330529.00      7039560.00
      2329984.93      7038948.18
#Sta/Elev= 30
  3840.4  666.02  3923.9  666.83  3985.9  669.53  4477.1  667.43  4567.2  666.93
  4597.8  655.59  4648.8  654.09  4662.3  654.32  4689.5  666.51  4698.2  666.80
  4730.3  663.63  4771.1  663.37  4832.3  656.26  4964.6  655.94  4975.0  648.82
  4990.3  648.32  4992.8  647.82  5014.6  648.32  5030.9  648.49  5045.1  652.45
  5151.3  657.53  5363.7  656.40  5469.9  658.46  5555.2  660.98  5604.5  669.26
  5633.0  666.40  5682.3  669.64  5724.9  666.42  5760.1  671.94  5814.1  672.80
#Mann=6,-1,0
  3840.4    0.05       0  3923.9     0.1       0  4477.1   0.075       0
  4698.2    0.05       0  4990.3    0.04       0  5014.6    0.05       0
Bank Sta=4990.3,5014.6
Exp/Cntr=0.3,0.1

Type RM Length L Ch R = 1,33399,524,524,524
BEGIN DESCRIPTION:
Henrietta Creek 49.0
END DESCRIPTION:
XS GIS Cut Line= 3
      2330929.00      7040960.04      2330929.00      7039160.00
      2330278.96      7038759.97
#Sta/Elev= 30
  3205.0  670.35  3815.9  666.08  4067.0  664.75  4495.0  660.31  4665.0  662.78
  4775.0  661.30  4805.0  658.78  4835.0  650.79  4845.0  646.43  4855.0  644.88
  4895.0  643.31  4965.0  645.02  4990.4  642.79  4992.8  642.29  5014.7  642.79
  5028.2  644.74  5049.4  643.37  5076.6  645.59  5144.1  645.41  5171.3  656.85
  5318.0  660.56  5528.6  661.07  5544.1  662.49  5565.3  666.88  5602.0  663.98
  5660.0  667.25  5687.2  664.52  5709.5  664.53  5745.1  669.91  5768.3  670.56
#Mann=5,-1,0
  3205.0   0.075       0  3815.9     0.1       0  4067.0    0.05       0
  4990.4   0.033       0  5014.7    0.05       0
Bank Sta=4990.4,5014.7
Exp/Cntr=0.3,0.1

Type RM Length L Ch R = 1,32875,1348,1348,1348
BEGIN DESCRIPTION:
Henrietta Creek 48.0
END DESCRIPTION:
XS GIS Cut Line= 3
      2330978.99      7040510.03      2331379.00      7038960.00
      2331115.79      7037914.02
#Sta/Elev= 30
  3395.0  668.04  3507.3  667.41  3558.8  667.28  4065.0  665.10  4148.2  664.73
  4261.5  663.69  4634.3  654.78  4644.7  654.18  4652.7  650.14  4657.9  652.11
  4693.4  643.82  4717.0  645.01  4734.1  648.98  4830.6  652.26  4891.6  643.90
  5042.8  642.05  5045.2  641.55  5067.1  642.05  5160.8  643.43  5171.1  647.25
  5178.2  653.25  5191.7  655.99  5243.3  654.64  5284.5  657.13  5325.8  654.31
  5356.7  656.49  5383.8  653.07  5439.2  653.18  5779.5  662.89  6074.4  666.50
#Mann=8,-1,0
  3395.0   0.075       0  3507.3     0.1       0  3558.8   0.075       0
  4065.0    0.05       0  4148.2   0.075       0  4261.5    0.05       0
  5042.8   0.033       0  5067.1    0.05       0
Bank Sta=5042.8,5067.1
Exp/Cntr=0.3,0.1