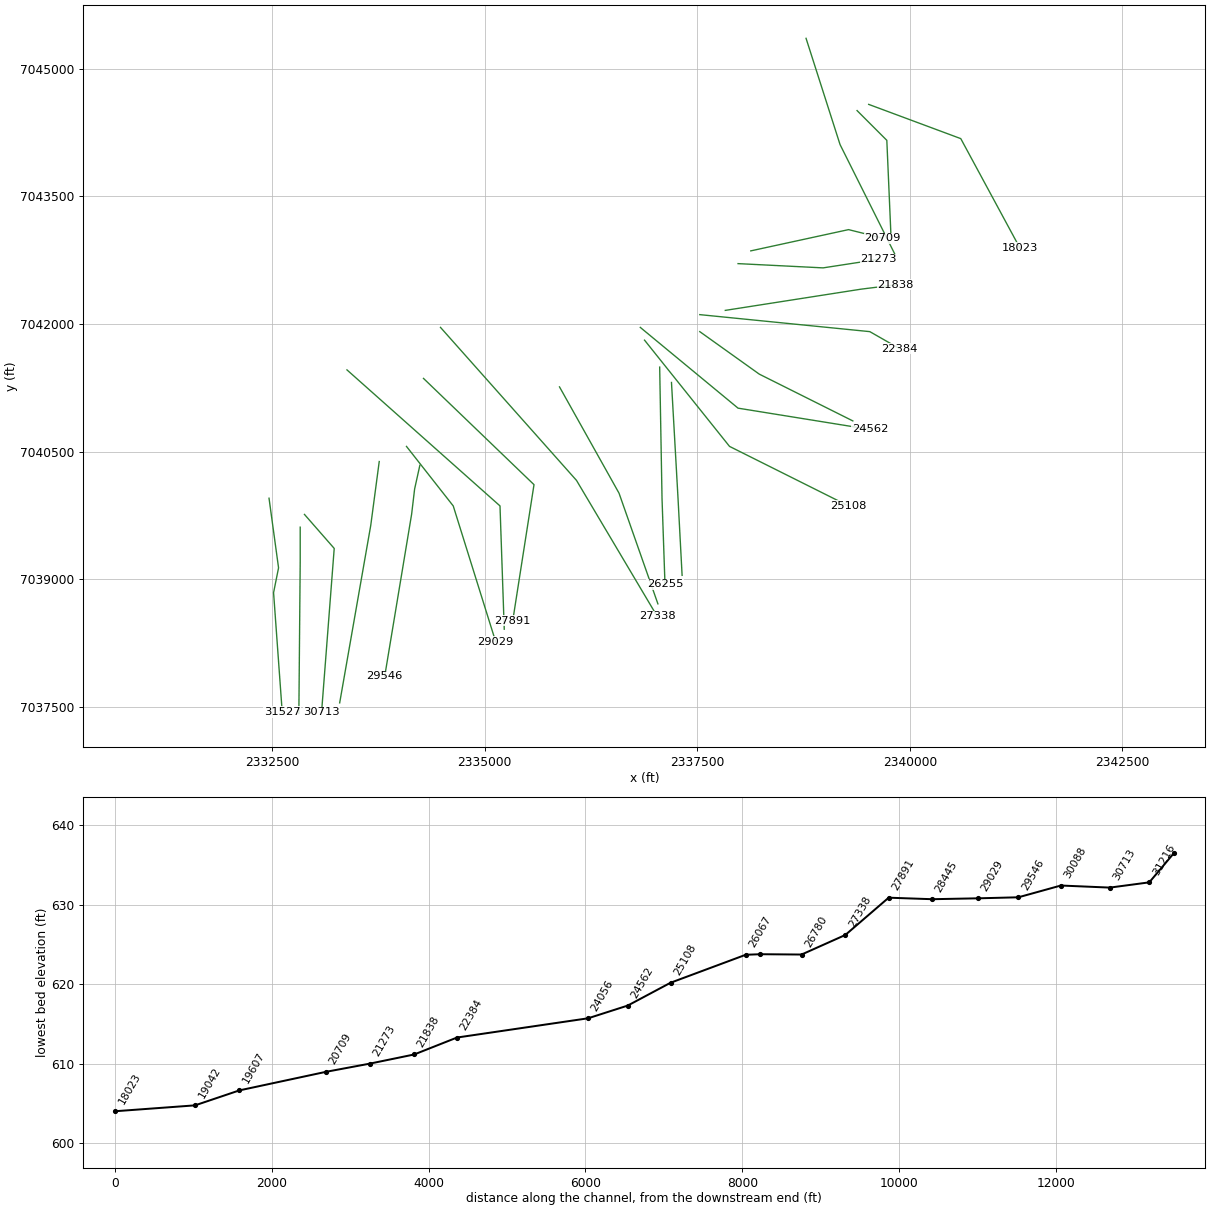
HEC-RAS study Henrietta Creek.prj: Henrietta Creek Base Level Engineering

--- Henrietta Creek.g01 (geometry) --- (continued)

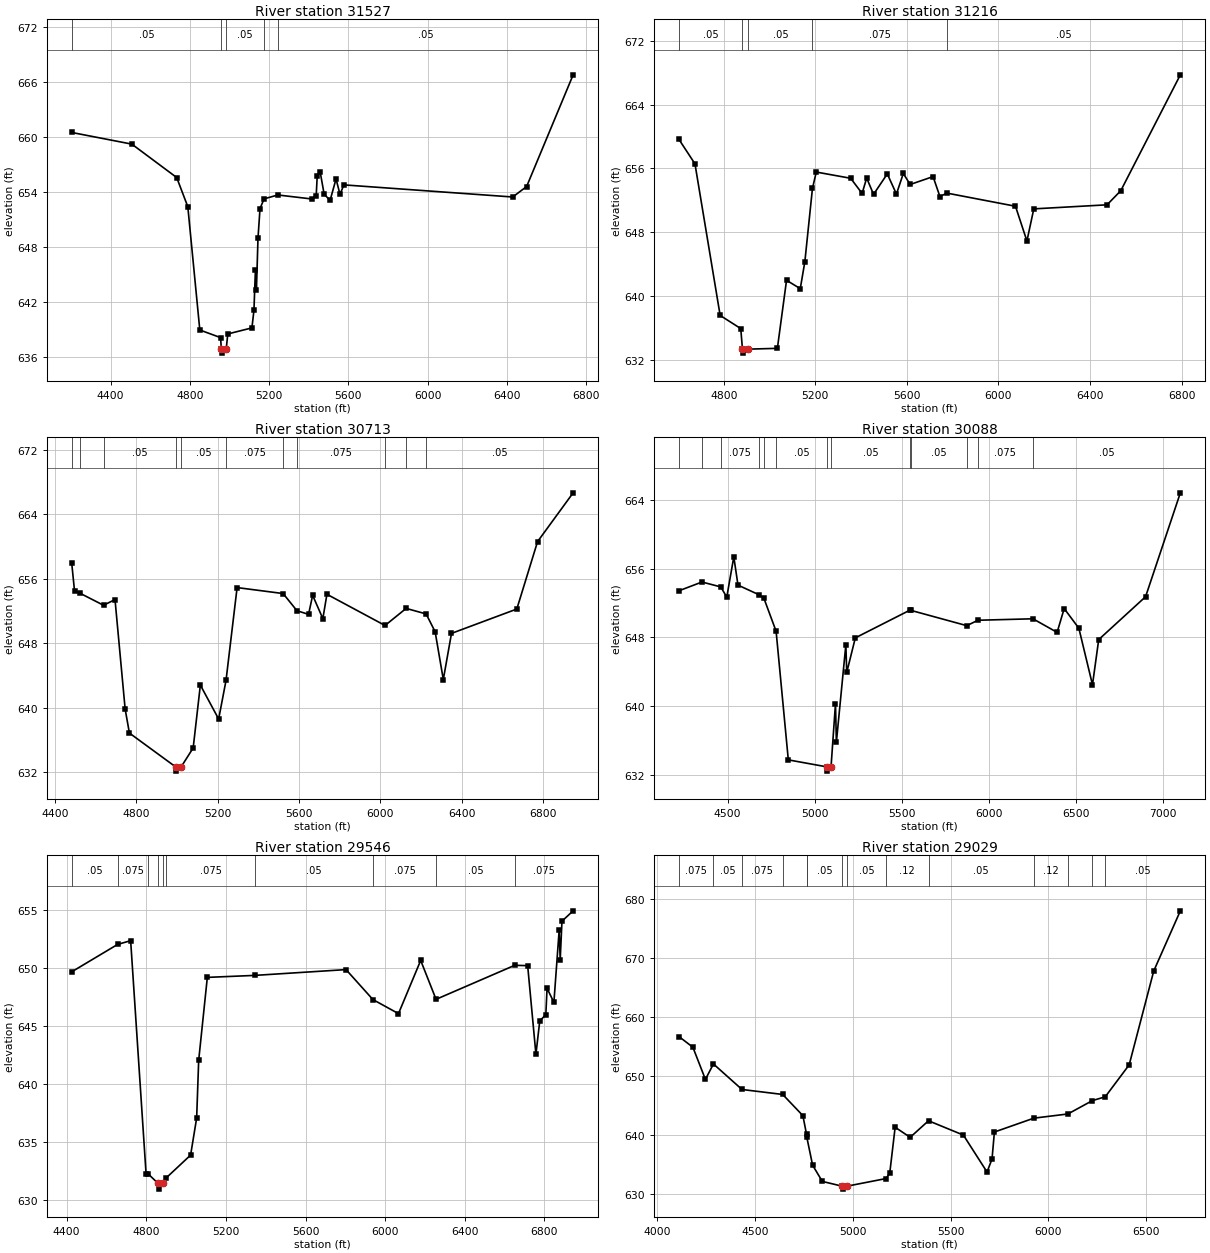
Type RM Length L Ch R = 1,31527,311,311,311
BEGIN DESCRIPTION:
Henrietta Creek 47.0
END DESCRIPTION:
XS GIS Cut Line= 4
      2332462.14      7039950.77      2332574.31      7039131.70
      2332515.66      7038839.68      2332617.30      7037435.72
#Sta/Elev= 30
  4203.3  660.51  4506.8  659.24  4733.4  655.60  4789.5  652.42  4850.1  638.99
  4955.0  638.16  4958.7  636.97  4961.2  636.47  4983.7  636.97  4991.4  638.56
  5113.3  639.22  5123.5  641.14  5130.9  645.52  5136.0  643.31  5143.9  648.97
  5154.1  652.22  5174.8  653.28  5244.2  653.70  5417.8  653.26  5437.8  653.59
  5443.1  655.79  5457.9  656.22  5477.9  653.80  5508.0  653.10  5538.1  655.45
  5558.1  653.76  5577.5  654.80  6430.4  653.48  6500.6  654.62  6735.5  666.79
#Mann=5,-1,0
  4203.3    0.05       0  4958.7   0.033       0  4983.7    0.05       0
  5174.8   0.075       0  5244.2    0.05       0
Bank Sta=4958.7,4983.7
Exp/Cntr=0.3,0.1

Type RM Length L Ch R = 1,31216,503,503,503
BEGIN DESCRIPTION:
Henrietta Creek 46.0
END DESCRIPTION:
XS GIS Cut Line= 3
      2332829.00      7039610.04      2332829.00      7039210.00
      2332813.12      7037419.81
#Sta/Elev= 30
  4604.2  659.65  4674.2  656.58  4784.2  637.56  4874.2  635.91  4881.7  633.33
  4884.2  632.83  4906.7  633.33  5034.2  633.43  5074.2  641.97  5134.2  640.92
  5154.2  644.30  5187.4  653.50  5204.2  655.55  5354.3  654.77  5404.3  652.87
  5424.3  654.80  5454.3  652.75  5514.3  655.32  5554.3  652.79  5584.3  655.37
  5614.3  653.99  5714.3  654.98  5744.3  652.47  5774.5  652.91  6074.3  651.26
  6124.3  646.90  6154.3  650.93  6474.3  651.44  6534.3  653.21  6794.5  667.75
#Mann=5,-1,0
  4604.2    0.05       0  4881.7   0.033       0  4906.7    0.05       0
  5187.4   0.075       0  5774.5    0.05       0
Bank Sta=4881.7,4906.7
Exp/Cntr=0.3,0.1

Type RM Length L Ch R = 1,30713,625,625,625
BEGIN DESCRIPTION:
Henrietta Creek 45.0
END DESCRIPTION:
XS GIS Cut Line= 3
      2332879.00      7039760.00      2333229.00      7039360.00
      2333080.28      7037434.14
#Sta/Elev= 30
  4483.3  657.94  4497.1  654.49  4524.6  654.22  4639.4  652.74  4695.9  653.44
  4745.7  639.86  4766.6  636.89  4995.2  632.67  4997.7  632.17  5020.2  632.67
  5079.9  635.05  5115.1  642.84  5205.0  638.63  5241.2  643.41  5295.6  654.93
  5521.7  654.19  5589.8  652.06  5646.7  651.61  5666.7  653.97  5716.9  651.08
  5736.9  654.10  6022.4  650.23  6126.0  652.35  6224.3  651.66  6268.5  649.45
  6308.6  643.53  6348.8  649.25  6669.7  652.27  6771.6  660.63  6946.4  666.68
#Mann=11,-1,0
  4483.3    0.05       0  4524.6   0.075       0  4639.4    0.05       0
  4995.2   0.033       0  5020.2    0.05       0  5241.2   0.075       0
  5521.7    0.05       0  5589.8   0.075       0  6022.4     0.1       0
  6126.0   0.075       0  6224.3    0.05       0
Bank Sta=4995.2,5020.2
Exp/Cntr=0.3,0.1

Type RM Length L Ch R = 1,30088,542,542,542
BEGIN DESCRIPTION:
Henrietta Creek 44.0
END DESCRIPTION:
XS GIS Cut Line= 3
      2333758.43      7040382.03      2333658.74      7039631.37
      2333293.25      7037543.47
#Sta/Elev= 30
  4220.7  653.42  4352.7  654.44  4460.7  653.87  4495.1  652.68  4535.5  657.37
  4559.4  654.08  4677.6  652.98  4707.4  652.59  4778.2  648.71  4848.2  633.74
  5068.4  632.93  5070.9  632.43  5093.4  632.93  5118.9  640.29  5124.0  635.80
  5178.4  647.14  5183.4  643.91  5232.7  647.94  5548.4  651.19  5553.3  651.13
  5872.4  649.36  5936.1  649.99  6251.9  650.16  6390.5  648.58  6431.1  651.35
  6515.3  649.06  6593.5  642.48  6629.2  647.74  6898.1  652.73  7097.6  664.82
#Mann=13,-1,0
  4220.7   0.075       0  4352.7    0.05       0  4460.7   0.075       0
  4677.6    0.05       0  4707.4   0.075       0  4778.2    0.05       0
  5068.4   0.033       0  5093.4    0.05       0  5548.4   0.075       0
  5553.3    0.05       0  5872.4     0.1       0  5936.1   0.075       0
  6251.9    0.05       0
Bank Sta=5068.4,5093.4
Exp/Cntr=0.3,0.1

Type RM Length L Ch R = 1,29546,517,517,517
BEGIN DESCRIPTION:
Henrietta Creek 43.0
END DESCRIPTION:
XS GIS Cut Line= 4
      2334236.37      7040338.03      2334174.79      7040059.46
      2334139.60      7039763.32      2333822.72      7037854.67
#Sta/Elev= 30
  4425.8  649.66  4656.4  652.02  4721.7  652.34  4799.3  632.23  4808.9  632.27
  4859.2  631.45  4861.7  630.95  4884.2  631.45  4901.7  631.94  5022.8  633.88
  5053.2  637.07  5063.4  642.04  5106.8  649.18  5343.9  649.35  5803.4  649.85
  5938.5  647.27  6066.9  646.06  6178.4  650.64  6255.6  647.29  6650.8  650.22
  6715.7  650.19  6757.2  642.56  6776.5  645.44  6806.9  645.96  6813.1  648.24
  6847.5  647.03  6874.0  653.25  6879.1  650.69  6888.0  654.02  6944.1  654.91
#Mann=10,-1,0
  4425.8    0.05       0  4656.4   0.075       0  4808.9     0.1       0
  4859.2    0.07       0  4884.2     0.1       0  4901.7   0.075       0
  5343.9    0.05       0  5938.5   0.075       0  6255.6    0.05       0
  6650.8   0.075       0
Bank Sta=4859.2,4884.2
Exp/Cntr=0.3,0.1

Type RM Length L Ch R = 1,29029,584,584,584
BEGIN DESCRIPTION:
Henrietta Creek 42.0
END DESCRIPTION:
XS GIS Cut Line= 3
      2334079.01      7040559.99      2334629.00      7039860.00
      2335129.00      7038260.02
#Sta/Elev= 30
  4109.8  656.69  4181.2  654.87  4245.3  649.42  4286.3  652.04  4432.6  647.71
  4640.8  646.87  4744.2  643.28  4762.8  640.13  4763.9  639.69  4793.9  634.88
  4843.6  632.13  4945.0  631.32  4947.5  630.82  4970.0  631.32  5170.8  632.62
  5189.1  633.61  5216.4  641.31  5293.4  639.60  5387.2  642.41  5565.8  639.98
  5686.8  633.72  5712.4  635.93  5724.5  640.50  5926.4  642.85  6100.7  643.56
  6226.2  645.83  6291.8  646.47  6414.4  651.89  6540.1  667.80  6676.3  678.00
#Mann=14,-1,0
  4109.8   0.075       0  4286.3    0.05       0  4432.6   0.075       0
  4640.8    0.05       0  4762.8    0.12       0  4763.9    0.05       0
  4945.0   0.033       0  4970.0    0.05       0  5170.8    0.12       0
  5387.2    0.05       0  5926.4    0.12       0  6100.7    0.05       0
  6226.2   0.075       0  6291.8    0.05       0
Bank Sta=4945,4970
Exp/Cntr=0.3,0.1

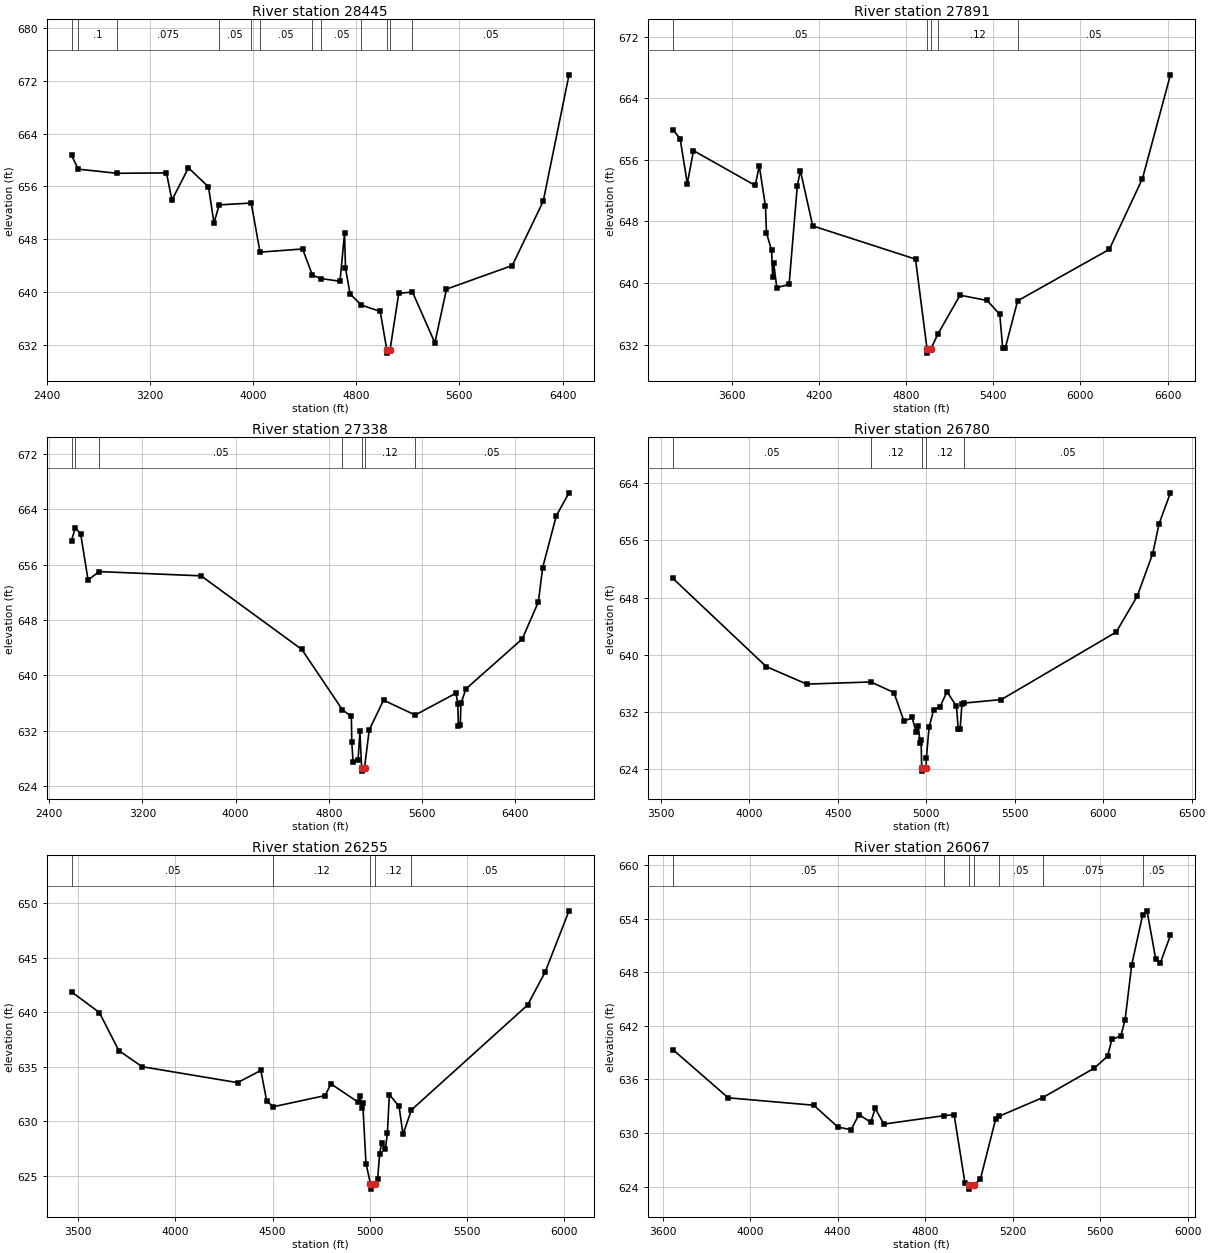
Type RM Length L Ch R = 1,28445,554,554,554
BEGIN DESCRIPTION:
Henrietta Creek 41.0
END DESCRIPTION:
XS GIS Cut Line= 3
      2333379.04      7041459.97      2335179.00      7039860.00
      2335229.00      7038410.03
#Sta/Elev= 30
  2591.1  660.73  2643.1  658.62  2944.0  657.99  3327.3  658.05  3370.0  653.93
  3497.9  658.82  3653.5  655.93  3696.1  650.45  3736.2  653.20  3984.7  653.48
  4053.4  646.03  4383.5  646.51  4460.1  642.52  4529.2  642.01  4673.7  641.61
  4708.8  648.86  4716.3  643.61  4751.4  639.70  4839.4  638.00  4985.6  637.04
  5036.9  631.21  5039.4  630.71  5061.9  631.21  5129.4  639.77  5235.5  639.99
  5409.6  632.27  5499.7  640.42  6010.0  644.00  6250.1  653.75  6450.2  672.93
#Mann=12,-1,0
  2591.1    0.05       0  2643.1     0.1       0  2944.0   0.075       0
  3736.2    0.05       0  3984.7   0.075       0  4053.4    0.05       0
  4460.1    0.12       0  4529.2    0.05       0  4839.4    0.12       0
  5036.9    0.07       0  5061.9    0.12       0  5235.5    0.05       0
Bank Sta=5036.9,5061.9
Exp/Cntr=0.3,0.1

Type RM Length L Ch R = 1,27891,553,553,553
BEGIN DESCRIPTION:
Henrietta Creek 40.0
END DESCRIPTION:
XS GIS Cut Line= 3
      2334279.01      7041359.99      2335579.00      7040110.00
      2335329.00      7038509.97
#Sta/Elev= 30
  3196.5  659.92  3246.0  658.73  3295.4  652.91  3337.9  657.19  3762.4  652.67
  3790.7  655.21  3833.1  649.95  3840.1  646.49  3875.6  644.23  3882.5  640.80
  3889.7  642.65  3910.8  639.40  3995.7  639.82  4052.3  652.65  4073.4  654.59
  4158.3  647.42  4865.5  643.10  4945.1  631.40  4947.6  630.90  4970.1  631.40
  5018.2  633.33  5172.0  638.42  5357.7  637.74  5445.3  635.93  5465.5  631.54
  5483.3  631.57  5568.0  637.69  6198.8  644.37  6427.1  653.56  6619.4  667.03
#Mann=5,-1,0
  3196.5    0.05       0  4945.1   0.033       0  4970.1    0.05       0
  5018.2    0.12       0  5568.0    0.05       0
Bank Sta=4945.1,4970.1
Exp/Cntr=0.3,0.1

Type RM Length L Ch R = 1,27338,558,558,558
BEGIN DESCRIPTION:
Henrietta Creek 39.0
END DESCRIPTION:
XS GIS Cut Line= 3
      2334478.97      7041960.03      2336079.00      7040160.00
      2337028.98      7038560.04
#Sta/Elev= 30
  2592.2  659.45  2624.4  661.30  2670.4  660.41  2734.0  653.79  2830.6  654.98
  3704.0  654.37  4568.7  643.75  4915.4  635.08  4993.5  634.09  4997.2  630.34
  5008.4  627.48  5051.2  627.83  5066.8  631.93  5081.6  626.71  5084.1  626.21
  5106.6  626.71  5146.7  632.13  5269.4  636.44  5541.2  634.30  5891.0  637.45
  5906.6  635.96  5912.4  632.74  5928.0  632.84  5933.9  635.99  5977.5  638.08
  6460.0  645.27  6598.3  650.60  6635.3  655.57  6752.2  663.03  6861.3  666.34
#Mann=7,-1,0
  2592.2    0.05       0  2624.4   0.075       0  2830.6    0.05       0
  4915.4    0.12       0  5081.6    0.07       0  5106.6    0.12       0
  5541.2    0.05       0
Bank Sta=5081.6,5106.6
Exp/Cntr=0.3,0.1

Type RM Length L Ch R = 1,26780,525,525,525
BEGIN DESCRIPTION:
Henrietta Creek 38.0
END DESCRIPTION:
XS GIS Cut Line= 3
      2335879.02      7041259.96      2336579.00      7040010.00
      2337036.36      7038708.11
#Sta/Elev= 30
  3567.4  650.68  4094.8  638.36  4323.8  635.91  4686.3  636.21  4816.6  634.73
  4873.9  630.70  4919.8  631.25  4942.7  629.16  4954.4  630.07  4964.6  627.74
  4970.3  628.09  4973.8  624.25  4976.3  623.75  4998.8  624.25  5000.0  625.58
  5015.5  629.88  5041.2  632.30  5077.5  632.74  5116.6  634.86  5170.4  632.80
  5180.2  629.63  5190.8  629.62  5201.4  633.12  5214.1  633.26  5424.0  633.75
  6073.4  643.18  6192.1  648.19  6279.7  654.14  6316.0  658.33  6379.9  662.64
#Mann=5,-1,0
  3567.4    0.05       0  4686.3    0.12       0  4973.8    0.07       0
  4998.8    0.12       0  5214.1    0.05       0
Bank Sta=4973.8,4998.8
Exp/Cntr=0.3,0.1

Type RM Length L Ch R = 1,26255,188,188,188
BEGIN DESCRIPTION:
Henrietta Creek 37.0
END DESCRIPTION:
XS GIS Cut Line= 3
      2337057.19      7041492.83      2337084.97      7039944.22
      2337119.69      7038937.28
#Sta/Elev= 30
  3466.9  641.89  3609.8  639.99  3709.8  636.50  3829.8  635.02  4319.9  633.56
  4439.9  634.68  4469.9  631.85  4504.1  631.35  4769.9  632.37  4799.9  633.45
  4940.0  631.76  4950.0  632.30  4958.3  631.27  4963.3  631.67  4980.0  626.14
  5002.9  624.29  5005.4  623.79  5027.9  624.29  5040.0  624.74  5050.0  627.00
  5060.0  627.98  5080.0  627.50  5090.0  628.91  5100.0  632.47  5150.1  631.37
  5170.1  628.82  5213.8  631.06  5810.5  640.68  5900.5  643.70  6023.3  649.32
#Mann=5,-1,0
  3466.9    0.05       0  4504.1    0.12       0  5002.9    0.07       0
  5027.9    0.12       0  5213.8    0.05       0
Bank Sta=5002.9,5027.9
Exp/Cntr=0.3,0.1

Type RM Length L Ch R = 1,26067,959,959,959
BEGIN DESCRIPTION:
Henrietta Creek 36.0
END DESCRIPTION:
XS GIS Cut Line= 3
      2337196.08      7041312.23      2337272.47      7039958.11
      2337320.98      7039043.27
#Sta/Elev= 30
  3647.7  639.33  3900.3  633.94  4291.0  633.11  4401.1  630.67  4461.2  630.37
  4497.4  632.07  4551.4  631.20  4571.4  632.75  4611.5  631.00  4887.8  631.95
  4932.0  632.05  4982.0  624.35  4999.6  624.22  5002.1  623.72  5024.6  624.22
  5052.1  624.83  5122.2  631.60  5136.8  631.87  5337.2  633.97  5572.9  637.27
  5633.0  638.60  5653.0  640.51  5693.0  640.83  5713.1  642.67  5743.1  648.79
  5792.9  654.38  5813.2  654.87  5853.3  649.43  5873.3  648.99  5920.1  652.12
#Mann=7,-1,0
  3647.7    0.05       0  4887.8    0.12       0  4999.6    0.07       0
  5024.6    0.12       0  5136.8    0.05       0  5337.2   0.075       0
  5792.9    0.05       0
Bank Sta=4999.6,5024.6
Exp/Cntr=0.3,0.1

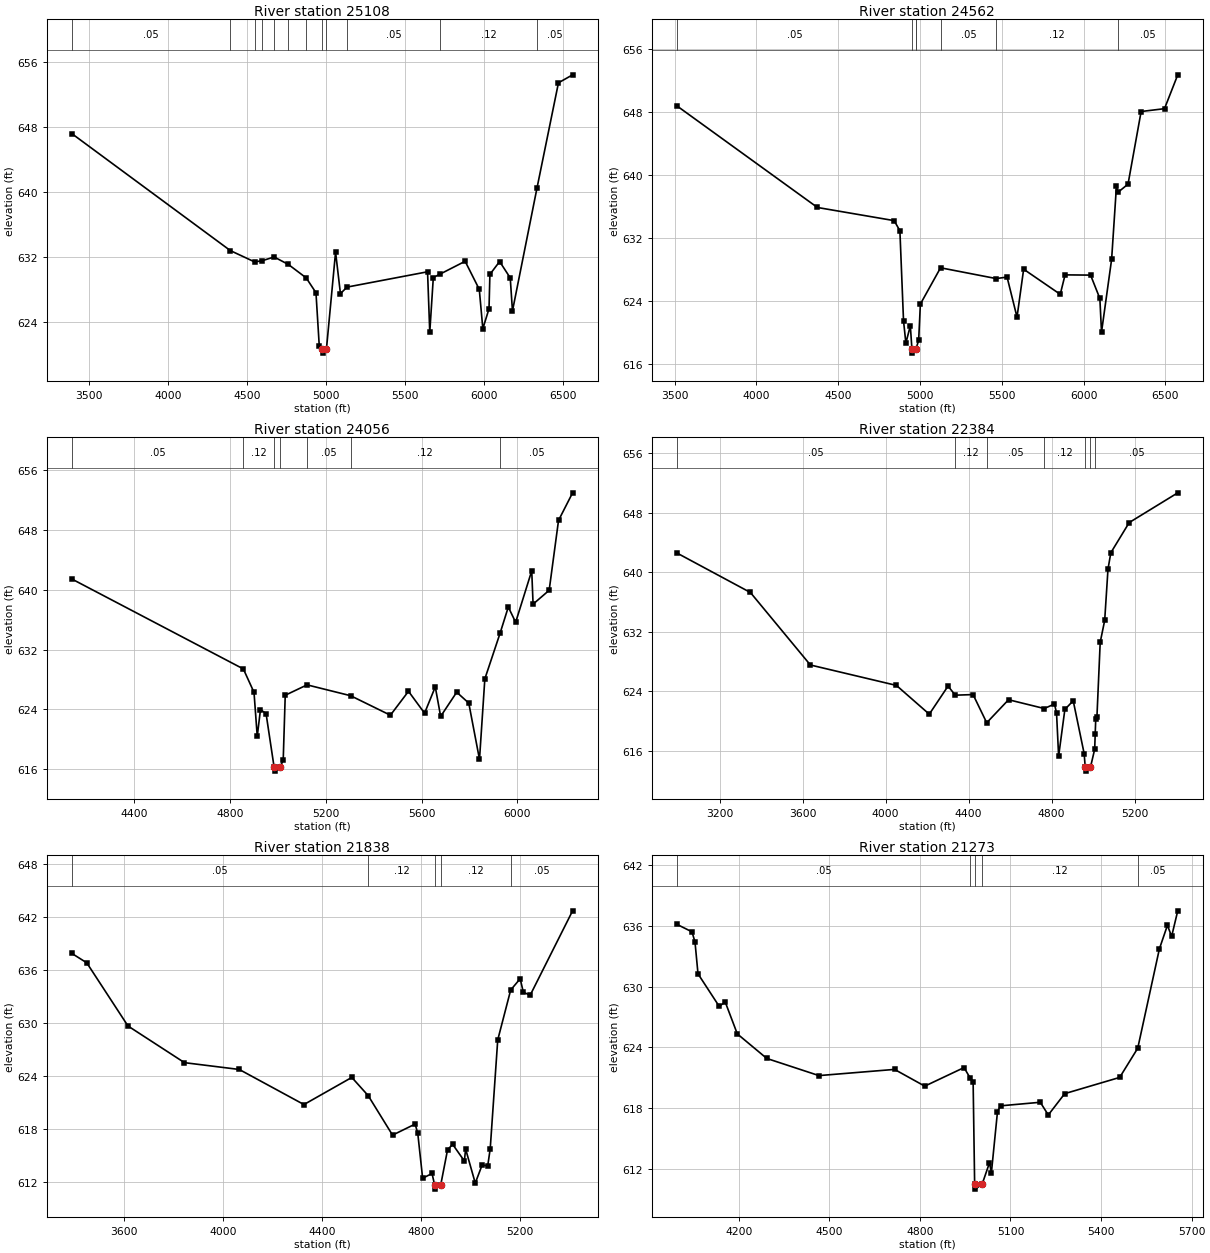
Type RM Length L Ch R = 1,25108,546,546,546
BEGIN DESCRIPTION:
Henrietta Creek 35.0
END DESCRIPTION:
XS GIS Cut Line= 3
      2336879.01      7041809.98      2337879.00      7040560.00
      2339278.99      7039860.00
#Sta/Elev= 30
  3393.1  647.17  4396.0  632.79  4549.6  631.40  4598.9  631.56  4672.4  632.01
  4762.6  631.09  4875.3  629.44  4937.0  627.62  4957.8  621.10  4978.2  620.70
  4980.7  620.20  5003.2  620.70  5060.9  632.61  5091.7  627.51  5133.5  628.31
  5642.3  630.19  5656.3  622.76  5678.7  629.48  5721.8  629.91  5879.9  631.48
  5969.3  628.03  5991.7  623.20  6030.8  625.65  6036.4  629.87  6097.9  631.45
  6165.0  629.44  6179.0  625.38  6334.4  640.51  6469.7  653.40  6559.1  654.38
#Mann=12,-1,0
  3393.1    0.05       0  4396.0    0.12       0  4549.6   0.075       0
  4598.9    0.05       0  4672.4   0.075       0  4762.6    0.05       0
  4875.3    0.12       0  4978.2    0.07       0  5003.2    0.12       0
  5133.5    0.05       0  5721.8    0.12       0  6334.4    0.05       0
Bank Sta=4978.2,5003.2
Exp/Cntr=0.3,0.1

Type RM Length L Ch R = 1,24562,506,506,506
BEGIN DESCRIPTION:
Henrietta Creek 34.0
END DESCRIPTION:
XS GIS Cut Line= 3
      2336828.99      7041960.01      2337979.00      7041010.00
      2339529.01      7040760.00
#Sta/Elev= 30
  3513.5  648.74  4372.7  635.83  4841.7  634.16  4876.8  632.87  4899.0  621.42
  4913.3  618.61  4940.6  620.81  4950.3  617.83  4952.8  617.33  4975.3  617.83
  4975.6  617.91  4991.5  618.95  5001.9  623.56  5125.3  628.17  5465.3  626.80
  5531.9  626.99  5592.7  621.90  5633.2  627.99  5857.0  624.80  5886.4  627.27
  6042.4  627.24  6099.1  624.27  6109.2  619.99  6171.0  629.25  6200.4  638.51
  6209.0  637.74  6271.3  638.80  6351.3  648.02  6494.2  648.38  6575.2  652.68
#Mann=7,-1,0
  3513.5    0.05       0  4950.3    0.07       0  4975.3    0.05       0
  4975.6    0.12       0  5125.3    0.05       0  5465.3    0.12       0
  6209.0    0.05       0
Bank Sta=4950.3,4975.3
Exp/Cntr=0.3,0.1

Type RM Length L Ch R = 1,24056,1672,1672,1672
BEGIN DESCRIPTION:
Henrietta Creek 33.0
END DESCRIPTION:
XS GIS Cut Line= 3
      2337528.98      7041910.01      2338229.00      7041410.00
      2339329.01      7040860.00
#Sta/Elev= 30
  4139.9  641.44  4856.1  629.40  4900.6  626.27  4914.1  620.38  4927.6  623.97
  4951.0  623.41  4984.6  616.23  4987.1  615.73  5009.6  616.23  5022.5  617.24
  5030.9  625.88  5122.0  627.27  5303.6  625.82  5469.7  623.21  5545.2  626.41
  5612.3  623.48  5657.0  627.00  5679.4  623.05  5746.4  626.29  5796.8  624.83
  5841.5  617.30  5863.8  628.07  5927.6  634.20  5961.7  637.68  5992.4  635.64
  6059.5  642.53  6065.1  638.07  6132.2  639.92  6171.3  649.27  6230.0  652.96
#Mann=7,-1,0
  4139.9    0.05       0  4856.1    0.12       0  4984.6    0.07       0
  5009.6    0.12       0  5122.0    0.05       0  5303.6    0.12       0
  5927.6    0.05       0
Bank Sta=4984.6,5009.6
Exp/Cntr=0.3,0.1

Type RM Length L Ch R = 1,22384,546,546,546
BEGIN DESCRIPTION:
Henrietta Creek 32.0
END DESCRIPTION:
XS GIS Cut Line= 3
      2337529.04      7042110.00      2339529.00      7041910.00
      2339878.96      7041710.02
#Sta/Elev= 30
  2994.4  642.58  3348.6  637.28  3637.6  627.55  4052.1  624.81  4210.4  620.95
  4300.8  624.72  4335.6  623.50  4421.4  623.58  4487.1  619.80  4592.3  622.89
  4764.2  621.71  4813.4  622.31  4823.4  621.14  4833.5  615.32  4863.6  621.59
  4903.8  622.75  4956.6  615.65  4961.7  613.81  4964.2  613.31  4986.7  613.81
  5007.2  616.24  5009.8  618.33  5012.3  620.33  5018.0  620.56  5033.8  630.60
  5055.4  633.53  5071.3  640.41  5085.0  642.61  5173.5  646.66  5407.4  650.65
#Mann=7,-1,0
  2994.4    0.05       0  4335.6    0.12       0  4487.1    0.05       0
  4764.2    0.12       0  4961.7    0.07       0  4986.7    0.12       0
  5009.8    0.05       0
Bank Sta=4961.7,4986.7
Exp/Cntr=0.3,0.1

Type RM Length L Ch R = 1,21838,565,565,565
BEGIN DESCRIPTION:
Henrietta Creek 31.0
END DESCRIPTION:
XS GIS Cut Line= 3
      2337829.03      7042160.01      2339429.00      7042410.00
      2339829.01      7042460.00
#Sta/Elev= 30
  3389.6  637.86  3450.3  636.79  3616.8  629.64  3845.0  625.49  4066.2  624.72
  4327.3  620.75  4520.6  623.82  4586.7  621.76  4685.1  617.29  4776.2  618.54
  4786.8  617.52  4806.6  612.41  4844.5  612.95  4854.8  611.68  4857.3  611.18
  4879.8  611.68  4907.3  615.65  4928.0  616.24  4975.1  614.36  4980.1  615.72
  5019.1  611.86  5046.8  613.91  5069.4  613.81  5079.5  615.76  5109.8  628.06
  5162.1  633.71  5200.5  634.99  5213.1  633.46  5240.8  633.12  5412.1  642.67
#Mann=5,-1,0
  3389.6    0.05       0  4586.7    0.12       0  4854.8    0.07       0
  4879.8    0.12       0  5162.1    0.05       0
Bank Sta=4854.8,4879.8
Exp/Cntr=0.3,0.1

Type RM Length L Ch R = 1,21273,564,564,564
BEGIN DESCRIPTION:
Henrietta Creek 30.0
END DESCRIPTION:
XS GIS Cut Line= 3
      2337979.04      7042710.00      2338979.00      7042660.00
      2339629.05      7042760.01
#Sta/Elev= 30
  3995.1  636.13  4045.1  635.39  4055.1  634.40  4065.1  631.25  4135.2  628.05
  4155.3  628.47  4195.3  625.33  4292.9  622.91  4465.6  621.22  4716.0  621.83
  4816.1  620.18  4946.2  622.01  4965.5  621.03  4976.3  620.61  4981.3  610.53
  4983.8  610.03  5006.3  610.53  5030.5  612.63  5036.8  611.65  5057.0  617.67
  5067.1  618.24  5198.7  618.59  5225.2  617.34  5279.6  619.44  5461.7  621.04
  5521.5  623.92  5593.2  633.71  5619.8  636.03  5633.7  634.94  5654.0  637.46
#Mann=5,-1,0
  3995.1    0.05       0  4965.5    0.12       0  4981.3    0.07       0
  5006.3    0.12       0  5521.5    0.05       0
Bank Sta=4981.3,5006.3
Exp/Cntr=0.3,0.1

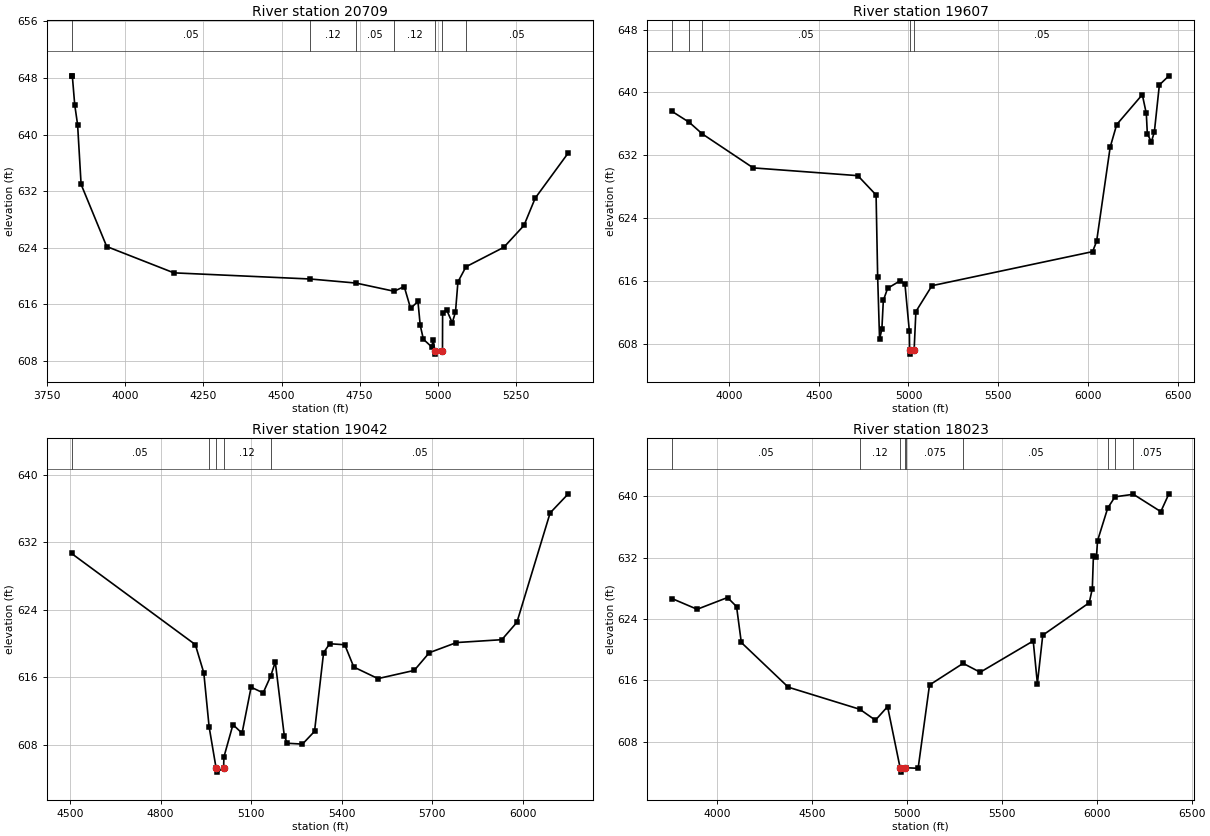
Type RM Length L Ch R = 1,20709,1102,1102,1102
BEGIN DESCRIPTION:
Henrietta Creek 29.0
END DESCRIPTION:
XS GIS Cut Line= 3
      2338128.97      7042859.99      2339279.00      7043110.00
      2339679.00      7043010.00
#Sta/Elev= 30
  3828.1  648.30  3830.7  648.30  3838.4  644.21  3847.6  641.39  3858.8  632.97
  3940.7  624.19  4155.6  620.47  4592.5  619.60  4737.8  619.03  4860.3  617.87
  4892.4  618.54  4912.9  615.45  4936.4  616.43  4943.6  613.09  4953.8  611.09
  4980.4  610.01  4985.5  611.05  4989.9  609.49  4992.4  608.99  5014.9  609.49
  5015.3  614.77  5028.2  615.24  5046.2  613.42  5056.5  614.94  5064.3  619.19
  5090.1  621.33  5211.1  624.08  5275.6  627.17  5311.6  631.03  5417.3  637.41
#Mann=7,-1,0
  3828.1    0.05       0  4592.5    0.12       0  4737.8    0.05       0
  4860.3    0.12       0  4989.9    0.07       0  5014.9    0.12       0
  5090.1    0.05       0
Bank Sta=4989.9,5014.9
Exp/Cntr=0.3,0.1

Type RM Length L Ch R = 1,19607,565,565,565
BEGIN DESCRIPTION:
Henrietta Creek 28.0
END DESCRIPTION:
XS GIS Cut Line= 3
      2338779.01      7045359.96      2339179.00      7044110.00
      2339828.98      7042810.04
#Sta/Elev= 30
  3684.0  637.58  3779.7  636.19  3851.3  634.73  4135.4  630.39  4717.8  629.40
  4819.5  626.94  4828.4  616.43  4838.9  608.57  4851.7  609.84  4859.9  613.50
  4883.9  615.05  4954.4  616.02  4980.3  615.57  5004.8  609.59  5006.3  607.16
  5008.8  606.66  5031.3  607.16  5041.1  612.08  5130.6  615.38  6025.0  619.72
  6047.4  621.04  6122.8  633.02  6159.2  635.91  6301.7  639.72  6324.1  637.32
  6329.7  634.74  6352.0  633.70  6368.8  634.96  6396.7  640.96  6449.8  642.12
#Mann=5,-1,0
  3684.0    0.05       0  3779.7   0.075       0  3851.3    0.05       0
  5006.3   0.033       0  5031.3    0.05       0
Bank Sta=5006.3,5031.3
Exp/Cntr=0.3,0.1

Type RM Length L Ch R = 1,19042,1019,1019,1019
BEGIN DESCRIPTION:
Henrietta Creek 27.0
END DESCRIPTION:
XS GIS Cut Line= 3
      2339378.98      7044510.02      2339729.00      7044160.00
      2339779.00      7043010.00
#Sta/Elev= 30
  4504.6  630.69  4914.8  619.89  4943.0  616.54  4960.5  610.17  4983.6  605.28
  4986.1  604.78  5008.6  605.28  5009.6  606.57  5039.6  610.41  5069.7  609.39
  5099.7  614.84  5139.7  614.17  5165.4  616.22  5179.8  617.84  5209.8  609.05
  5219.8  608.20  5269.9  608.10  5309.9  609.61  5339.9  618.93  5360.0  619.99
  5410.0  619.87  5440.0  617.23  5520.1  615.86  5640.2  616.83  5690.3  618.93
  5780.3  620.13  5930.5  620.47  5980.5  622.53  6090.6  635.49  6150.7  637.75
#Mann=5,-1,0
  4504.6    0.05       0  4960.5    0.12       0  4983.6    0.07       0
  5008.6    0.12       0  5165.4    0.05       0
Bank Sta=4983.6,5008.6
Exp/Cntr=0.3,0.1

Type RM Length L Ch R = 1,18023,632,632,632
BEGIN DESCRIPTION:
Henrietta Creek 26.5
END DESCRIPTION:
XS GIS Cut Line= 3
      2339515.56      7044583.10      2340598.86      7044180.33
      2341293.28      7042895.65
#Sta/Elev= 30
  3764.0  626.66  3895.7  625.27  4055.7  626.80  4103.3  625.62  4128.3  620.94
  4375.8  615.11  4752.7  612.23  4834.5  610.81  4898.6  612.58  4965.1  604.54
  4967.6  604.04  4990.1  604.54  4996.1  604.61  5059.5  604.54  5119.4  615.40
  5296.5  618.22  5386.2  617.06  5665.6  621.14  5687.5  615.59  5715.8  621.89
  5960.6  626.12  5976.8  627.96  5982.5  632.18  5998.7  632.13  6004.4  634.21
  6057.9  638.46  6096.3  639.93  6193.0  640.26  6337.5  638.00  6380.1  640.32
#Mann=9,-1,0
  3764.0    0.05       0  4752.7    0.12       0  4965.1    0.07       0
  4990.1    0.12       0  4996.1   0.075       0  5296.5    0.05       0
  6057.9   0.075       0  6096.3    0.05       0  6193.0   0.075       0
Bank Sta=4965.1,4990.1
Exp/Cntr=0.3,0.1