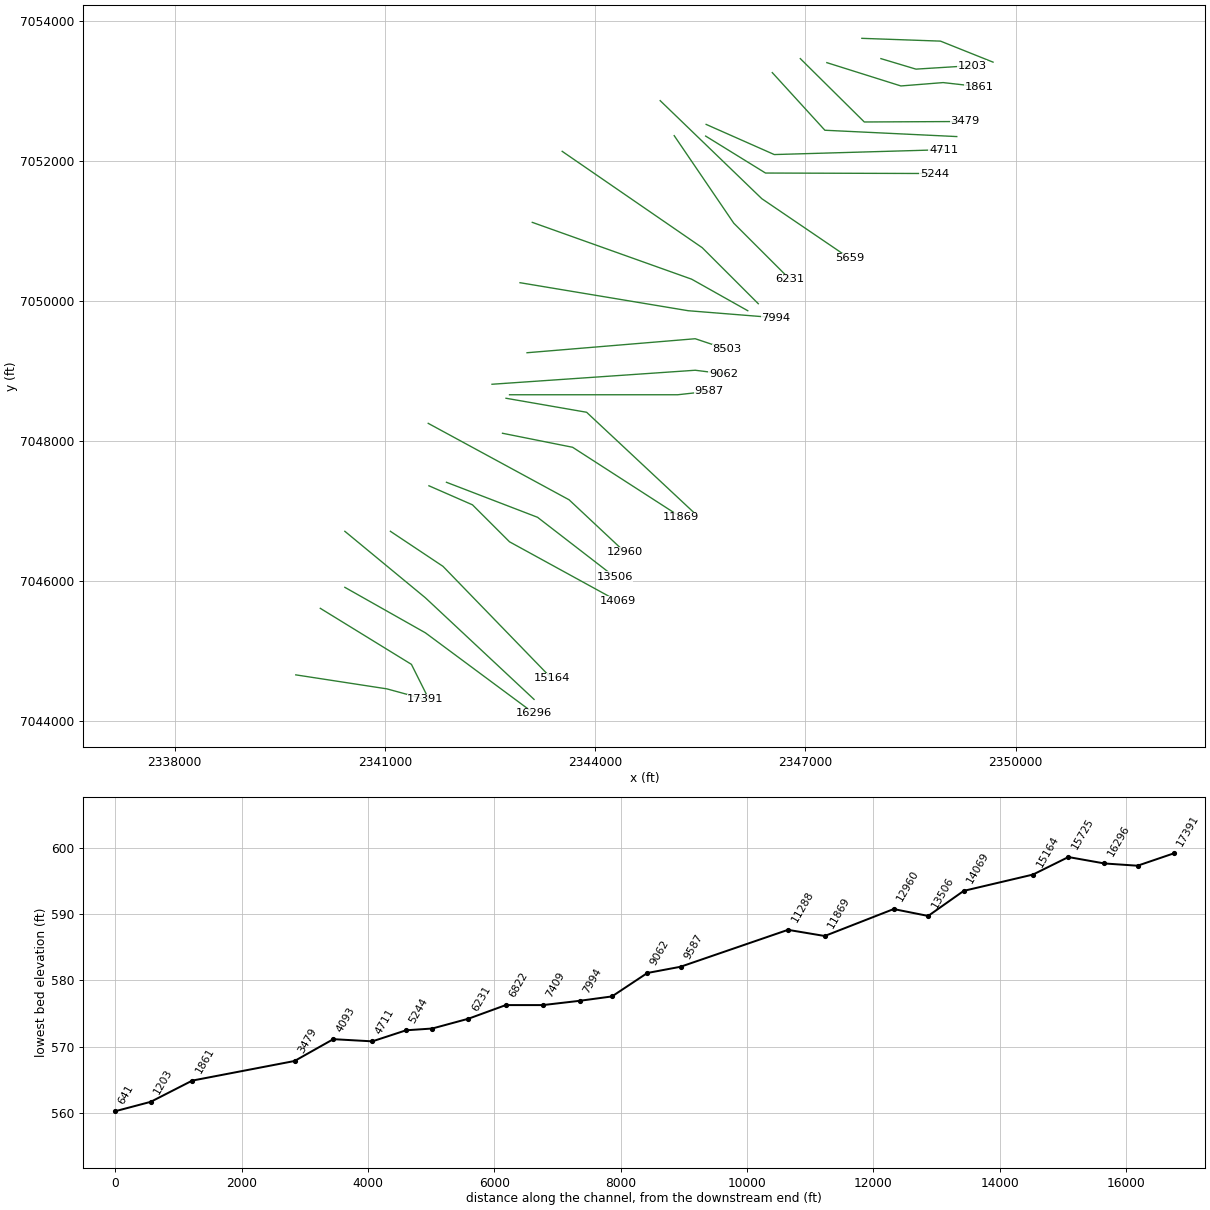
HEC-RAS study Henrietta Creek.prj: Henrietta Creek Base Level Engineering

--- Henrietta Creek.g01 (geometry) --- (continued)

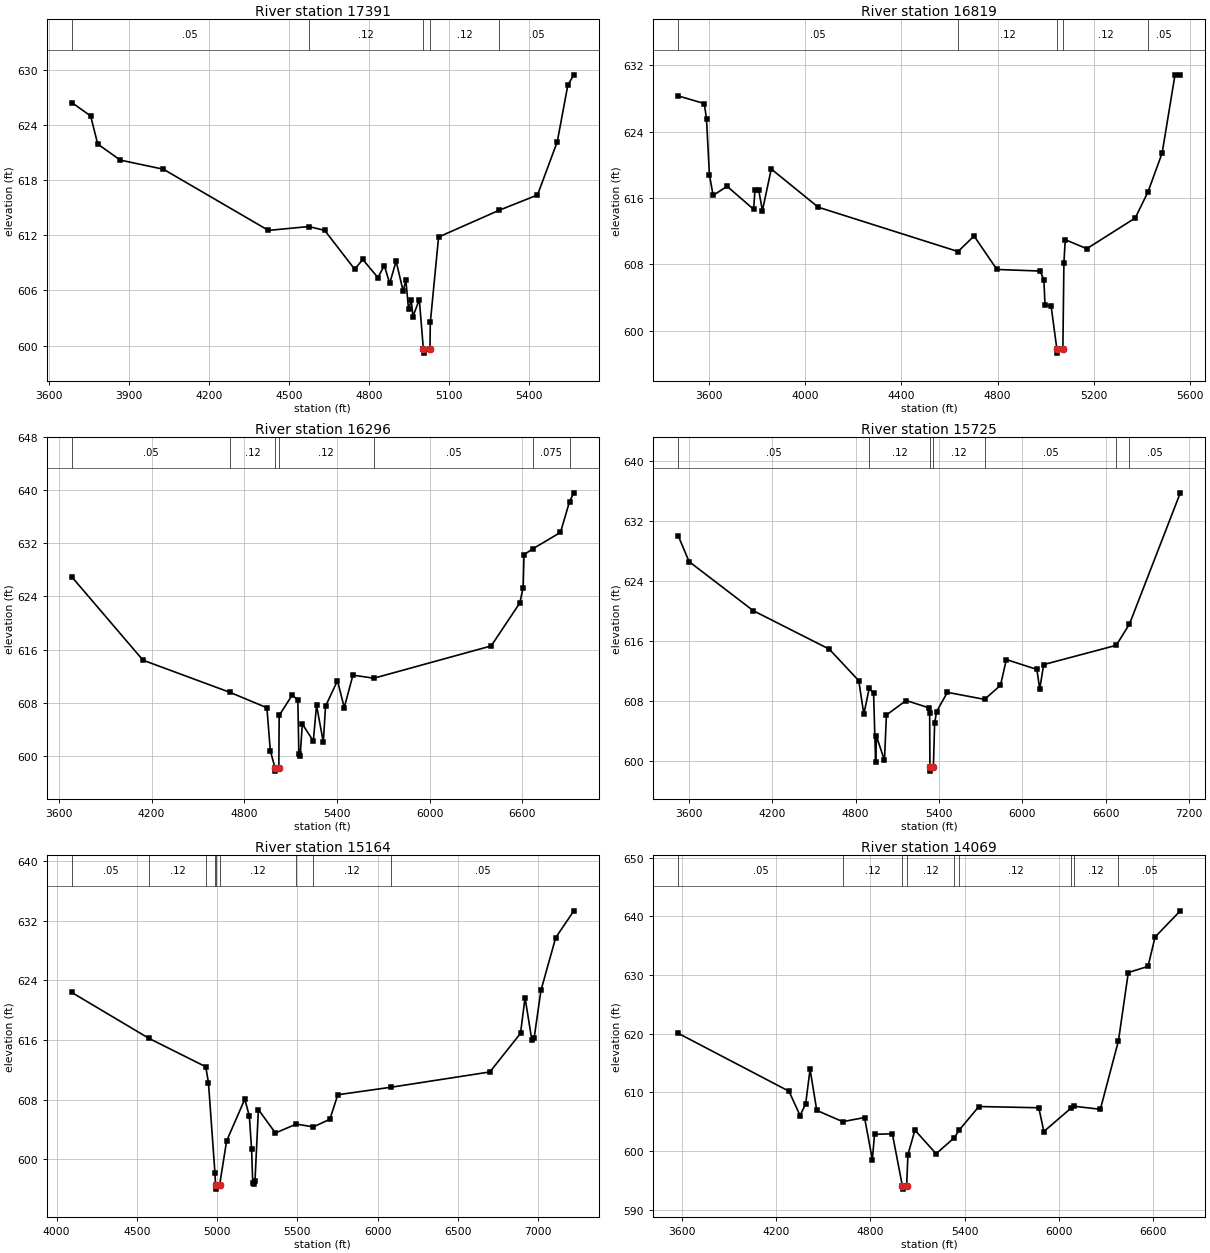
Type RM Length L Ch R = 1,17391,572,572,572
BEGIN DESCRIPTION:
Henrietta Creek 26.0
END DESCRIPTION:
XS GIS Cut Line= 3
      2339729.00      7044660.00      2341029.00      7044460.00
      2341579.01      7044310.00
#Sta/Elev= 30
  3684.7  626.42  3755.5  624.96  3782.1  621.91  3866.8  620.16  4028.7  619.17
  4423.3  612.52  4574.9  612.94  4634.5  612.52  4747.1  608.30  4777.4  609.36
  4834.3  607.39  4858.4  608.70  4878.6  606.76  4902.6  609.18  4929.2  605.92
  4939.3  607.11  4949.4  603.95  4959.5  604.92  4965.9  603.16  4989.9  605.00
  5004.8  599.68  5007.3  599.18  5029.8  599.68  5031.1  602.51  5062.2  611.80
  5288.9  614.70  5433.6  616.37  5507.9  622.16  5547.6  628.32  5570.1  629.43
#Mann=5,-1,0
  3684.7    0.05       0  4574.9    0.12       0  5004.8    0.07       0
  5029.8    0.12       0  5288.9    0.05       0
Bank Sta=5004.8,5029.8
Exp/Cntr=0.3,0.1

Type RM Length L Ch R = 1,16819,523,523,523
BEGIN DESCRIPTION:
Henrietta Creek 25.0
END DESCRIPTION:
XS GIS Cut Line= 3
      2340079.01      7045610.00      2341379.00      7044810.00
      2341628.98      7044310.04
#Sta/Elev= 30
  3473.3  628.31  3581.5  627.39  3590.7  625.54  3602.8  618.82  3618.2  616.32
  3676.2  617.42  3786.3  614.65  3792.2  617.03  3807.6  616.95  3823.0  614.49
  3859.7  619.50  4054.9  614.90  4635.4  609.56  4702.1  611.43  4796.8  607.40
  4976.6  607.21  4992.0  606.14  4996.8  603.12  5022.1  602.98  5045.9  597.82
  5048.4  597.32  5070.9  597.82  5075.2  608.20  5080.8  610.99  5170.2  609.90
  5371.5  613.60  5424.7  616.76  5483.3  621.44  5536.4  630.81  5558.7  630.85
#Mann=5,-1,0
  3473.3    0.05       0  4635.4    0.12       0  5045.9    0.07       0
  5070.9    0.12       0  5424.7    0.05       0
Bank Sta=5045.9,5070.9
Exp/Cntr=0.3,0.1

Type RM Length L Ch R = 1,16296,571,571,571
BEGIN DESCRIPTION:
Henrietta Creek 24.0
END DESCRIPTION:
XS GIS Cut Line= 3
      2340429.03      7045909.98      2341579.00      7045260.00
      2343129.02      7044109.99
#Sta/Elev= 30
  3683.4  626.96  4144.6  614.39  4708.7  609.53  4946.9  607.22  4969.0  600.75
  4999.2  598.16  5001.7  597.66  5024.2  598.16  5026.3  606.06  5111.8  609.16
  5147.3  608.34  5153.8  600.20  5161.9  599.90  5176.5  604.76  5247.4  602.20
  5268.3  607.60  5312.1  602.04  5326.7  607.46  5403.9  611.30  5447.7  607.25
  5504.0  612.14  5639.0  611.67  6399.0  616.54  6584.9  623.04  6605.8  625.33
  6612.0  630.31  6669.5  631.20  6847.8  633.66  6906.6  638.32  6934.4  639.63
#Mann=7,-1,0
  3683.4    0.05       0  4708.7    0.12       0  4999.2    0.07       0
  5024.2    0.12       0  5639.0    0.05       0  6669.5   0.075       0
  6906.6    0.05       0
Bank Sta=4999.2,5024.2
Exp/Cntr=0.3,0.1

Type RM Length L Ch R = 1,15725,561,561,561
BEGIN DESCRIPTION:
Henrietta Creek 23.0
END DESCRIPTION:
XS GIS Cut Line= 3
      2340429.00      7046710.00      2341579.00      7045760.00
      2343128.97      7044310.03
#Sta/Elev= 30
  3523.3  630.02  3601.1  626.58  4063.3  620.03  4610.5  614.90  4822.8  610.69
  4859.3  606.22  4897.8  609.67  4929.6  609.01  4943.9  599.87  4950.4  603.27
  5007.8  600.07  5022.0  606.12  5163.7  608.05  5326.4  607.08  5333.2  606.34
  5334.9  599.13  5337.4  598.63  5359.9  599.13  5368.9  605.03  5383.0  606.57
  5460.7  609.14  5728.5  608.20  5842.7  610.07  5885.2  613.51  6104.5  612.20
  6125.5  609.59  6153.9  612.84  6676.2  615.41  6771.6  618.25  7137.4  635.75
#Mann=7,-1,0
  3523.3    0.05       0  4897.8    0.12       0  5334.9    0.07       0
  5359.9    0.12       0  5728.5    0.05       0  6676.2    0.12       0
  6771.6    0.05       0
Bank Sta=5334.9,5359.9
Exp/Cntr=0.3,0.1

Type RM Length L Ch R = 1,15164,1095,1095,1095
BEGIN DESCRIPTION:
Henrietta Creek 22.0
END DESCRIPTION:
XS GIS Cut Line= 3
      2341079.01      7046710.00      2341829.00      7046210.00
      2343378.97      7044610.03
#Sta/Elev= 30
  4094.4  622.38  4576.2  616.21  4929.3  612.41  4946.2  610.29  4986.9  598.09
  4990.4  596.48  4992.9  595.98  5015.4  596.48  5059.4  602.45  5172.6  608.05
  5200.9  605.81  5215.1  601.33  5222.0  596.82  5229.2  596.64  5236.2  597.05
  5257.5  606.66  5363.5  603.52  5494.2  604.71  5599.5  604.33  5703.0  605.36
  5752.4  608.65  6084.6  609.66  6700.1  611.71  6891.0  616.89  6919.3  621.69
  6961.7  615.98  6975.9  616.27  7018.3  622.65  7110.4  629.74  7223.4  633.34
#Mann=9,-1,0
  4094.4    0.05       0  4576.2    0.12       0  4929.3    0.05       0
  4986.9    0.12       0  4990.4    0.07       0  5015.4    0.12       0
  5494.2    0.05       0  5599.5    0.12       0  6084.6    0.05       0
Bank Sta=4990.4,5015.4
Exp/Cntr=0.3,0.1

Type RM Length L Ch R = 1,14069,563,563,563
BEGIN DESCRIPTION:
Henrietta Creek 20.0
END DESCRIPTION:
XS GIS Cut Line= 4
      2341629.03      7047359.99      2342250.59      7047087.90
      2342779.00      7046560.00      2344329.01      7045710.00
#Sta/Elev= 30
  3578.9  620.08  4283.1  610.21  4353.8  606.07  4389.1  608.02  4417.4  613.95
  4459.9  606.94  4624.8  605.02  4763.9  605.72  4813.4  598.55  4827.5  602.86
  4940.7  602.95  5004.7  594.02  5007.3  593.52  5031.4  594.02  5039.9  599.42
  5084.2  603.58  5219.0  599.55  5334.4  602.28  5367.4  603.64  5491.0  607.60
  5872.1  607.39  5904.3  603.34  6079.4  607.38  6095.3  607.65  6263.6  607.13
  6378.7  618.81  6441.3  630.44  6566.8  631.49  6611.4  636.49  6772.1  640.96
#Mann=9,-1,0
  3578.9    0.05       0  4624.8    0.12       0  5004.7    0.07       0
  5031.4    0.12       0  5334.4    0.05       0  5367.4    0.12       0
  6079.4    0.05       0  6095.3    0.12       0  6378.7    0.05       0
Bank Sta=5004.7,5031.4
Exp/Cntr=0.3,0.1

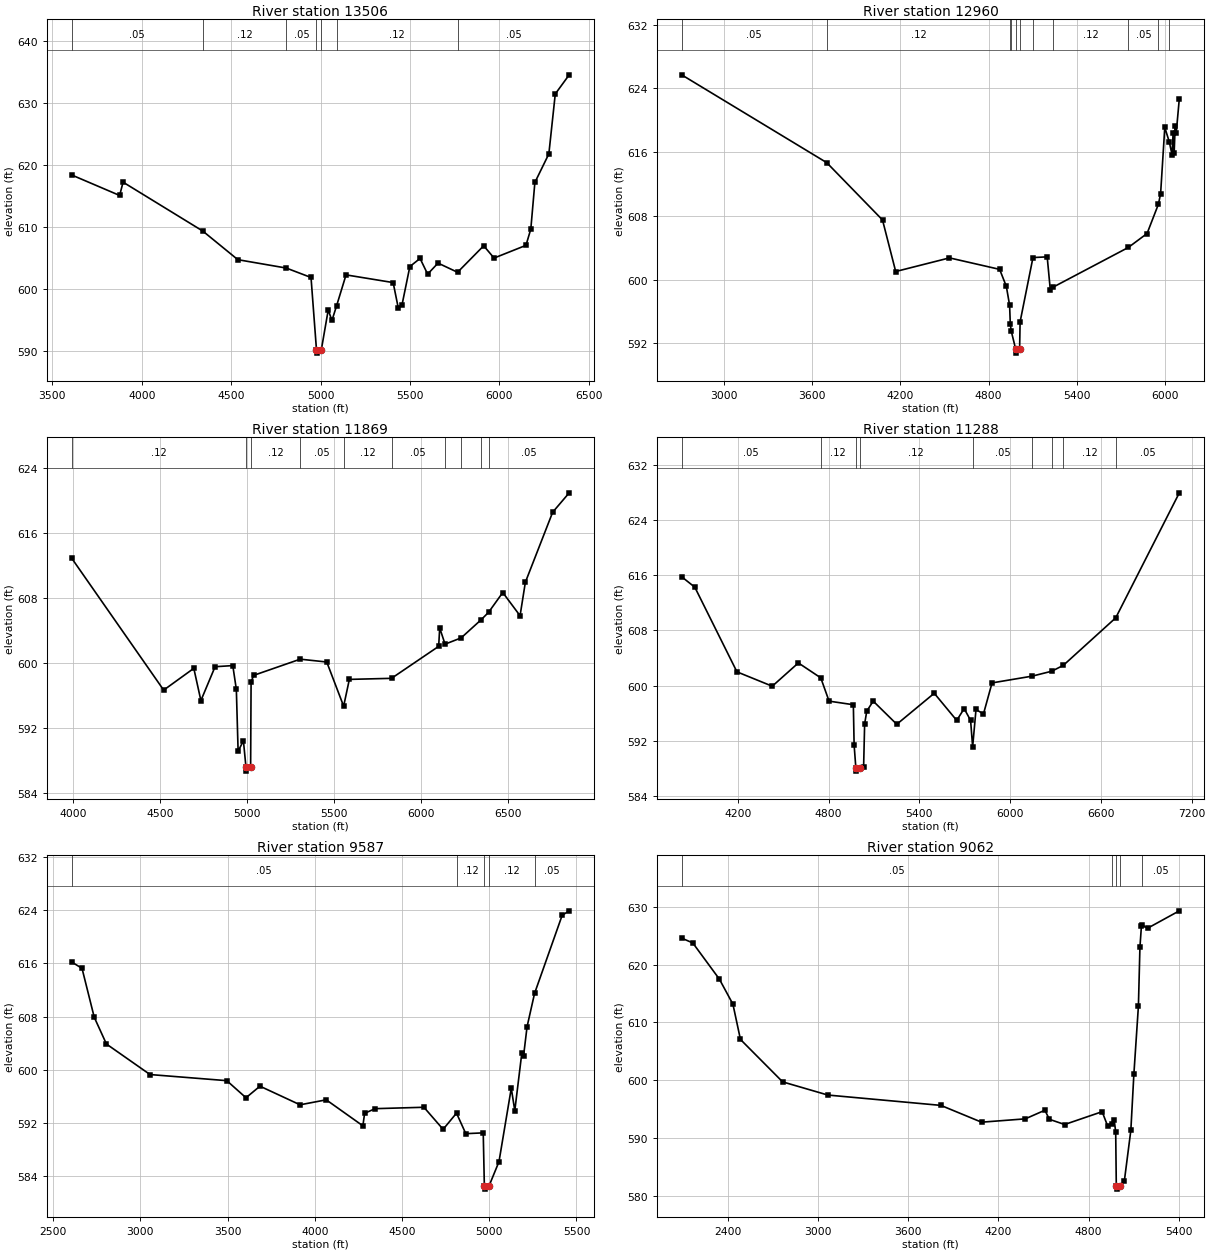
Type RM Length L Ch R = 1,13506,546,546,546
BEGIN DESCRIPTION:
Henrietta Creek 19.0
END DESCRIPTION:
XS GIS Cut Line= 3
      2341879.03      7047409.99      2343179.00      7046910.00
      2344279.04      7046059.97
#Sta/Elev= 30
  3607.2  618.45  3876.1  615.14  3895.4  617.28  4341.2  609.40  4537.2  604.79
  4808.1  603.44  4946.4  601.92  4977.0  590.23  4979.6  589.73  5003.8  590.23
  5042.6  596.69  5063.4  594.99  5089.5  597.37  5142.2  602.34  5405.7  601.10
  5434.7  596.95  5455.5  597.54  5499.0  603.68  5556.1  604.99  5598.6  602.46
  5656.6  604.24  5765.9  602.76  5912.0  607.03  5970.0  605.05  6148.4  607.10
  6175.5  609.72  6198.2  617.23  6276.4  621.84  6312.3  631.50  6390.2  634.58
#Mann=7,-1,0
  3607.2    0.05       0  4341.2    0.12       0  4808.1    0.05       0
  4977.0   0.033       0  5003.8    0.05       0  5089.5    0.12       0
  5765.9    0.05       0
Bank Sta=4977,5003.8
Exp/Cntr=0.3,0.1

Type RM Length L Ch R = 1,12960,1091,1091,1091
BEGIN DESCRIPTION:
Henrietta Creek 18.0
END DESCRIPTION:
XS GIS Cut Line= 3
      2341618.93      7048251.52      2343629.00      7047160.00
      2344429.00      7046410.00
#Sta/Elev= 30
  2712.9  625.69  3699.3  614.67  4078.5  607.48  4168.2  601.01  4534.0  602.72
  4875.0  601.28  4920.6  599.14  4942.7  596.78  4947.5  594.43  4953.7  593.55
  4984.0  591.27  4986.6  590.77  5010.8  591.27  5014.1  594.69  5101.6  602.76
  5198.3  602.85  5219.5  598.71  5239.7  599.06  5750.1  604.03  5877.5  605.78
  5954.3  609.44  5969.5  610.77  5997.9  619.09  6028.8  617.26  6047.2  615.68
  6054.5  618.39  6061.4  615.82  6068.7  619.23  6075.6  618.38  6096.8  622.71
#Mann=11,-1,0
  2712.9    0.05       0  3699.3    0.12       0  4947.5    0.05       0
  4953.7    0.12       0  4984.0    0.07       0  5010.8    0.12       0
  5101.6    0.05       0  5239.7    0.12       0  5750.1    0.05       0
  5954.3    0.12       0  6028.8    0.05       0
Bank Sta=4984,5010.8
Exp/Cntr=0.3,0.1

Type RM Length L Ch R = 1,11869,581,581,581
BEGIN DESCRIPTION:
Henrietta Creek 17.0
END DESCRIPTION:
XS GIS Cut Line= 3
      2342678.96      7048110.01      2343679.00      7047910.00
      2345228.98      7046910.02
#Sta/Elev= 30
  3989.9  612.95  4520.2  596.68  4693.6  599.36  4734.4  595.39  4816.0  599.56
  4918.0  599.70  4938.4  596.77  4948.6  589.15  4979.1  590.44  4993.8  587.20
  4996.4  586.70  5020.6  587.20  5023.3  597.71  5038.5  598.50  5306.2  600.49
  5458.8  600.14  5556.0  594.70  5588.9  598.00  5831.5  598.13  6103.0  602.07
  6108.9  604.34  6139.7  602.34  6232.2  603.11  6347.6  605.35  6390.1  606.26
  6471.9  608.70  6571.5  605.84  6601.9  609.96  6759.1  618.59  6854.3  620.98
#Mann=10,-1,0
  3989.9    0.12       0  4993.8    0.07       0  5020.6    0.12       0
  5306.2    0.05       0  5556.0    0.12       0  5831.5    0.05       0
  6139.7    0.12       0  6232.2    0.05       0  6347.6    0.12       0
  6390.1    0.05       0
Bank Sta=4993.8,5020.6
Exp/Cntr=0.3,0.1

Type RM Length L Ch R = 1,11288,1701,1701,1701
BEGIN DESCRIPTION:
Henrietta Creek 16.0
END DESCRIPTION:
XS GIS Cut Line= 3
      2342729.01      7048610.00      2343879.00      7048410.00
      2345429.04      7046959.97
#Sta/Elev= 30
  3828.5  615.76  3915.4  614.25  4193.9  602.00  4427.3  599.92  4599.9  603.29
  4748.0  601.13  4802.9  597.76  4963.4  597.24  4968.5  591.41  4979.8  588.13
  4982.4  587.63  5006.7  588.13  5031.2  588.18  5038.0  594.46  5052.2  596.32
  5094.7  597.76  5250.5  594.41  5498.2  598.90  5646.7  594.97  5696.0  596.68
  5738.5  594.97  5752.0  591.14  5774.2  596.55  5823.5  595.90  5880.2  600.40
  6145.8  601.38  6274.9  602.09  6351.5  602.94  6698.0  609.82  7118.3  627.91
#Mann=9,-1,0
  3828.5    0.05       0  4748.0    0.12       0  4979.8    0.07       0
  5006.7    0.12       0  5752.0    0.05       0  6145.8    0.12       0
  6274.9    0.05       0  6351.5    0.12       0  6698.0    0.05       0
Bank Sta=4979.8,5006.7
Exp/Cntr=0.3,0.1

Type RM Length L Ch R = 1,9587,525,525,525
BEGIN DESCRIPTION:
Henrietta Creek 15.0
END DESCRIPTION:
XS GIS Cut Line= 3
      2342778.99      7048660.00      2345179.00      7048660.00
      2345629.02      7048710.00
#Sta/Elev= 30
  2605.4  616.22  2665.4  615.25  2735.4  607.90  2805.4  603.87  3055.4  599.28
  3495.4  598.36  3605.4  595.79  3685.4  597.53  3915.4  594.73  4065.4  595.48
  4275.4  591.57  4285.4  593.45  4345.4  594.15  4625.4  594.36  4735.4  591.04
  4812.2  593.48  4865.4  590.39  4965.4  590.51  4971.8  582.55  4974.5  582.05
  4999.0  582.55  5055.7  586.18  5126.1  597.22  5146.3  593.85  5186.5  602.50
  5196.6  602.09  5216.7  606.48  5259.5  611.47  5417.9  623.23  5458.2  623.90
#Mann=5,-1,0
  2605.4    0.05       0  4812.2    0.12       0  4971.8    0.07       0
  4999.0    0.12       0  5259.5    0.05       0
Bank Sta=4971.8,4999
Exp/Cntr=0.3,0.1

Type RM Length L Ch R = 1,9062,559,559,559
BEGIN DESCRIPTION:
Henrietta Creek 14.0
END DESCRIPTION:
XS GIS Cut Line= 3
      2342529.01      7048810.00      2345429.00      7049010.00
      2345829.01      7048960.00
#Sta/Elev= 30
  2093.1  624.57  2167.0  623.74  2343.7  617.48  2433.9  613.14  2484.0  607.03
  2764.7  599.68  3065.4  597.40  3817.2  595.61  4087.8  592.70  4378.5  593.28
  4508.8  594.77  4538.9  593.20  4640.4  592.30  4889.7  594.52  4926.0  592.07
  4953.2  592.47  4969.9  593.06  4979.9  591.01  4983.9  581.61  4986.6  581.11
  5011.1  581.61  5037.8  582.60  5080.6  591.28  5100.8  601.02  5131.0  612.82
  5141.1  623.00  5151.1  626.71  5156.8  626.83  5191.5  626.28  5403.1  629.30
#Mann=5,-1,0
  2093.1    0.05       0  4953.2    0.12       0  4983.9    0.07       0
  5011.1    0.12       0  5156.8    0.05       0
Bank Sta=4983.9,5011.1
Exp/Cntr=0.3,0.1

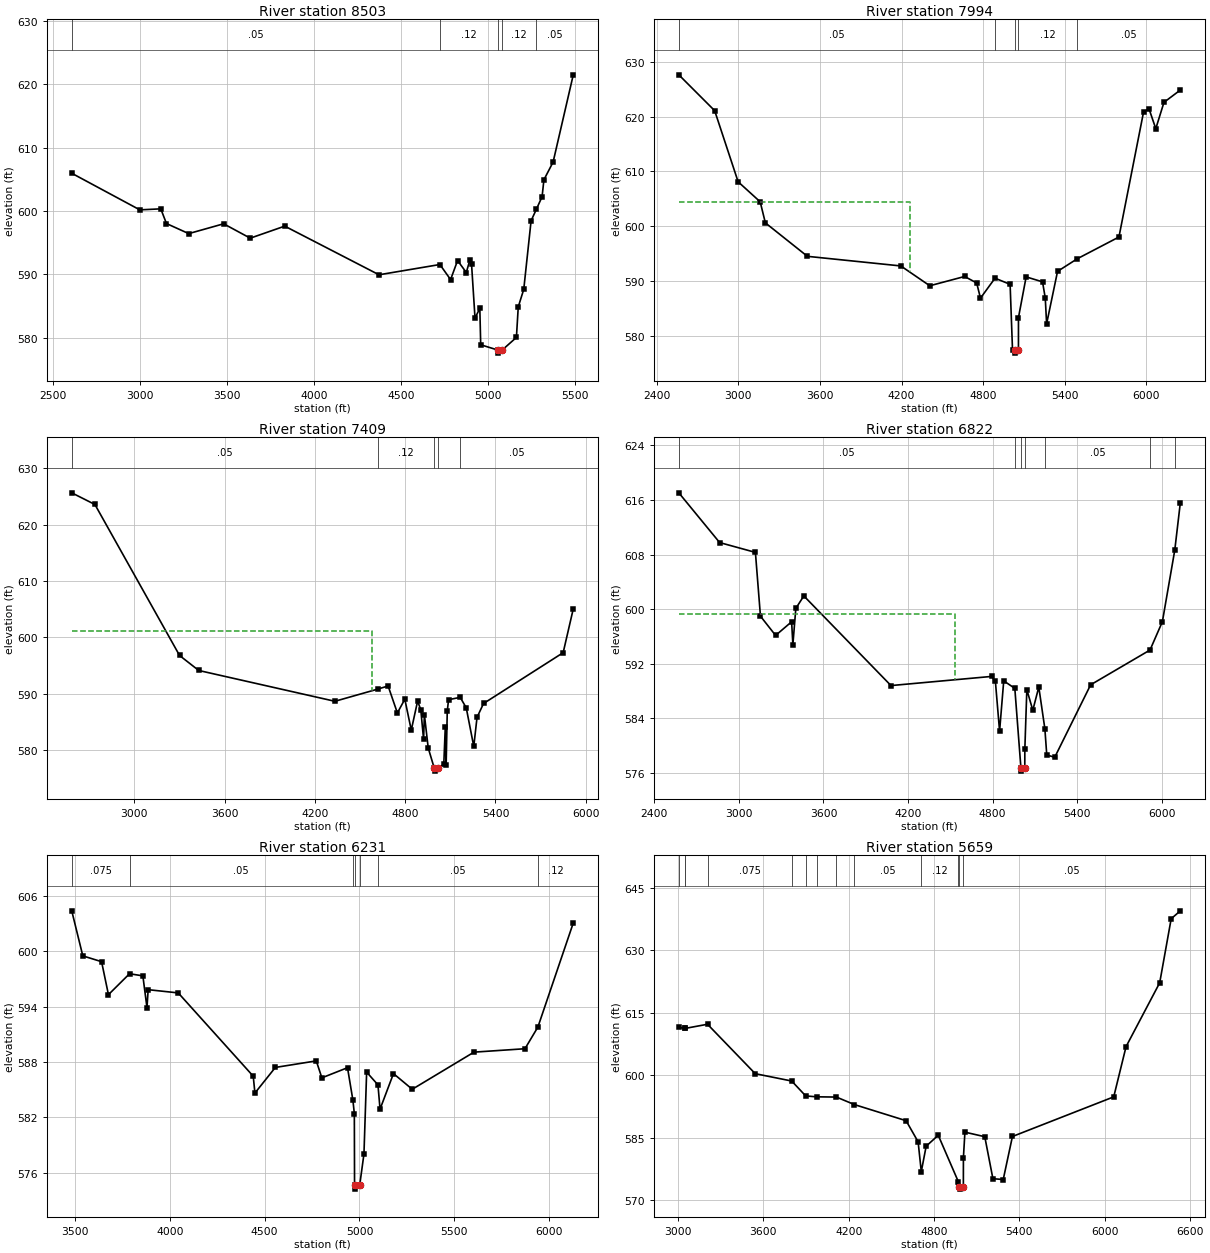
Type RM Length L Ch R = 1,8503,509,509,509
BEGIN DESCRIPTION:
Henrietta Creek 13.0
END DESCRIPTION:
XS GIS Cut Line= 3
      2343028.96      7049260.00      2345429.00      7049460.00
      2345879.00      7049310.00
#Sta/Elev= 30
  2605.6  605.97  2997.0  600.19  3117.4  600.35  3150.0  598.03  3278.0  596.44
  3478.7  597.99  3631.7  595.72  3829.9  597.62  4371.7  589.94  4721.6  591.56
  4783.2  589.18  4823.3  592.19  4873.5  590.30  4893.5  592.23  4903.6  591.64
  4923.6  583.09  4951.2  584.65  4956.3  578.89  5053.1  578.07  5055.8  577.57
  5080.3  578.07  5161.5  580.05  5172.1  584.87  5203.7  587.64  5245.9  598.47
  5275.7  600.25  5309.1  602.27  5319.6  604.94  5372.4  607.74  5488.3  621.51
#Mann=5,-1,0
  2605.6    0.05       0  4721.6    0.12       0  5053.1    0.07       0
  5080.3    0.12       0  5275.7    0.05       0
Bank Sta=5053.1,5080.3
Exp/Cntr=0.3,0.1

Type RM Length L Ch R = 1,7994,585,585,585
BEGIN DESCRIPTION:
Henrietta Creek 12.0
END DESCRIPTION:
XS GIS Cut Line= 3
      2342928.97      7050260.00      2345329.00      7049860.00
      2346578.97      7049760.00
#Sta/Elev= 30
  2562.3  627.60  2825.9  621.07  2998.3  608.12  3160.5  604.47  3198.5  600.64
  3507.7  594.54  4194.5  592.79  4407.4  589.18  4663.4  590.87  4752.1  589.69
  4780.0  586.92  4886.9  590.56  4997.9  589.44  5015.5  577.54  5032.0  577.41
  5034.7  576.91  5059.2  577.41  5059.4  583.39  5115.8  590.80  5236.2  589.89
  5256.3  586.96  5266.3  582.25  5346.6  591.80  5492.5  594.11  5798.0  598.06
  5978.6  620.78  6018.7  621.44  6068.9  617.79  6129.0  622.59  6249.4  624.83
#Mann=5,-1,0
  2562.3    0.05       0  4886.9    0.12       0  5032.0    0.07       0
  5059.2    0.12       0  5492.5    0.05       0
#XS Ineff=2,0
    0.00 4261.00  604.47               0
Permanent Ineff=
       F       F
Bank Sta=5032,5059.2
Exp/Cntr=0.3,0.1

Type RM Length L Ch R = 1,7409,587,587,587
BEGIN DESCRIPTION:
Henrietta Creek 11.0
END DESCRIPTION:
XS GIS Cut Line= 3
      2343103.97      7051121.84      2345379.00      7050310.00
      2346178.98      7049860.01
#Sta/Elev= 30
  2583.6  625.67  2737.6  623.60  3300.3  596.79  3427.7  594.13  4332.6  588.66
  4616.1  590.81  4686.3  591.38  4747.9  586.59  4797.4  589.03  4840.3  583.54
  4882.4  588.69  4903.6  587.16  4922.1  581.90  4927.4  586.30  4952.9  580.38
  4993.4  576.76  4996.1  576.26  5020.9  576.76  5056.5  577.51  5066.4  584.11
  5072.1  577.42  5079.5  586.90  5088.1  588.94  5165.5  589.36  5205.7  587.50
  5255.7  580.64  5277.4  585.81  5320.7  588.27  5849.8  597.29  5917.0  605.07
#Mann=5,-1,0
  2583.6    0.05       0  4616.1    0.12       0  4993.4    0.07       0
  5020.9    0.12       0  5165.5    0.05       0
#XS Ineff=2,0
    0.00 4580.50  601.19               0
Permanent Ineff=
       F       F
Bank Sta=4993.4,5020.9
Exp/Cntr=0.3,0.1

Type RM Length L Ch R = 1,6822,591,591,591
BEGIN DESCRIPTION:
Henrietta Creek 10.0
END DESCRIPTION:
XS GIS Cut Line= 3
      2343530.61      7052135.87      2345529.00      7050760.00
      2346329.00      7049960.00
#Sta/Elev= 30
  2573.8  617.05  2863.4  609.76  3117.1  608.32  3152.9  598.97  3260.4  596.15
  3374.0  598.15  3382.9  594.80  3403.8  600.11  3460.6  601.94  4078.8  588.80
  4792.4  590.14  4819.4  589.42  4849.2  582.11  4878.6  589.49  4957.3  588.39
  5000.4  576.76  5003.1  576.26  5028.0  576.76  5028.3  579.44  5042.5  588.21
  5084.9  585.18  5127.3  588.59  5170.4  582.47  5183.9  578.63  5240.4  578.29
  5495.0  588.91  5916.3  594.01  6004.1  598.17  6091.9  608.65  6131.4  615.61
#Mann=7,-1,0
  2573.8    0.05       0  4957.3    0.12       0  5000.4    0.07       0
  5028.0    0.12       0  5170.4    0.05       0  5916.3    0.12       0
  6091.9    0.05       0
#XS Ineff=2,0
    0.00 4534.90  599.33               0
Permanent Ineff=
       F       F
Bank Sta=5000.4,5028
Exp/Cntr=0.3,0.1

Type RM Length L Ch R = 1,6231,572,572,572
BEGIN DESCRIPTION:
Henrietta Creek 9.0
END DESCRIPTION:
XS GIS Cut Line= 3
      2345129.03      7052359.96      2345979.00      7051110.00
      2346778.97      7050310.03
#Sta/Elev= 30
  3483.6  604.41  3541.9  599.52  3640.8  598.89  3677.0  595.31  3788.1  597.58
  3858.4  597.35  3880.1  593.89  3886.2  595.85  4044.8  595.50  4440.0  586.46
  4448.9  584.63  4556.6  587.41  4772.2  588.12  4801.7  586.28  4936.8  587.38
  4965.2  583.86  4972.8  582.40  4973.9  574.70  4976.7  574.20  5001.5  574.70
  5023.5  578.02  5037.6  586.90  5097.2  585.52  5108.3  582.88  5179.0  586.74
  5278.0  585.04  5603.3  589.07  5872.0  589.44  5940.0  591.79  6126.5  603.09
#Mann=7,-1,0
  3483.6   0.075       0  3788.1    0.05       0  4965.2    0.12       0
  4973.9    0.07       0  5001.5    0.12       0  5097.2    0.05       0
  5940.0    0.12       0
Bank Sta=4973.9,5001.5
Exp/Cntr=0.3,0.1

Type RM Length L Ch R = 1,5659,415,415,415
BEGIN DESCRIPTION:
Henrietta Creek 8.0
END DESCRIPTION:
XS GIS Cut Line= 3
      2344929.02      7052859.98      2346379.00      7051460.00
      2347629.03      7050609.98
#Sta/Elev= 30
  3005.5  611.56  3045.5  611.27  3049.0  611.28  3207.3  612.28  3543.0  600.42
  3799.5  598.66  3897.9  595.08  3976.1  594.87  4113.8  594.81  4241.0  593.00
  4603.9  589.14  4688.5  584.07  4710.8  576.92  4745.1  583.02  4830.0  585.65
  4971.2  574.52  4979.0  573.22  4981.8  572.72  5006.7  573.22  5007.0  580.21
  5017.6  586.39  5157.3  585.30  5214.5  575.22  5287.1  575.03  5351.8  585.35
  6064.2  594.86  6151.0  606.92  6387.5  622.23  6468.3  637.60  6532.7  639.50
#Mann=13,-1,0
  3005.5    0.05       0  3045.5   0.075       0  3049.0    0.05       0
  3207.3   0.075       0  3799.5    0.05       0  3897.9   0.075       0
  3976.1    0.05       0  4113.8   0.075       0  4241.0    0.05       0
  4710.8    0.12       0  4971.2    0.05       0  4979.0   0.033       0
  5006.7    0.05       0
Bank Sta=4979,5006.7
Exp/Cntr=0.3,0.1

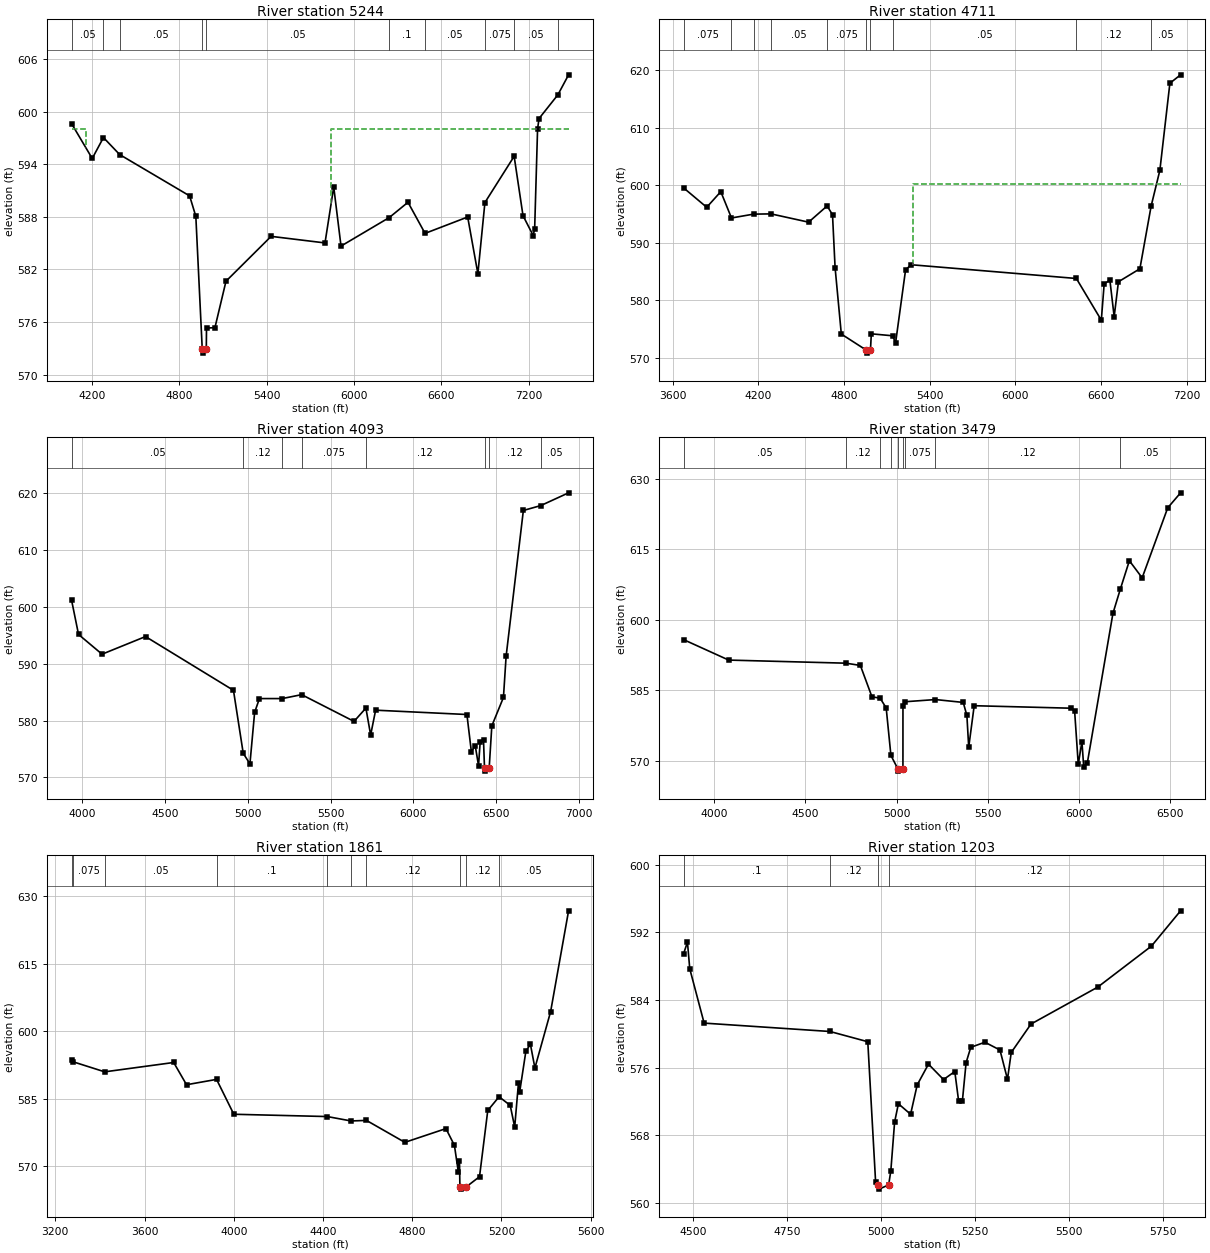
Type RM Length L Ch R = 1,5244,533,533,533
BEGIN DESCRIPTION:
Henrietta Creek 7.0
END DESCRIPTION:
XS GIS Cut Line= 3
      2345577.99      7052353.97      2346432.19      7051826.17
      2348841.87      7051819.22
#Sta/Elev= 30
  4059.4  598.66  4201.6  594.67  4278.7  597.06  4389.9  595.12  4870.6  590.40
  4913.2  588.06  4957.1  572.95  4959.9  572.45  4985.1  572.95  4986.5  575.31
  5044.4  575.36  5120.3  580.66  5430.3  585.78  5800.3  585.03  5860.3  591.42
  5910.3  584.67  6241.9  587.93  6370.3  589.67  6487.5  586.12  6780.3  587.99
  6850.3  581.52  6898.6  589.64  7099.4  594.92  7160.3  588.14  7230.3  585.87
  7240.3  586.66  7260.3  598.04  7270.3  599.23  7399.8  601.94  7473.2  604.22
#Mann=10,-1,0
  4059.4    0.05       0  4278.7   0.075       0  4389.9    0.05       0
  4957.1   0.033       0  4985.1    0.05       0  6241.9     0.1       0
  6487.5    0.05       0  6898.6   0.075       0  7099.4    0.05       0
  7399.8   0.075       0
#XS Ineff=2,0
    0.00 4157.90  598.06 5842.10    0.00  598.06
Permanent Ineff=
       F       F
Bank Sta=4957.1,4985.1
Exp/Cntr=0.3,0.1

Type RM Length L Ch R = 1,4711,618,618,618
BEGIN DESCRIPTION:
Henrietta Creek 6.0
END DESCRIPTION:
XS GIS Cut Line= 3
      2345584.98      7052520.61      2346557.19      7052090.06
      2348973.82      7052159.50
#Sta/Elev= 30
  3676.6  599.55  3839.1  596.16  3937.7  598.88  4012.5  594.30  4167.7  594.97
  4289.7  595.01  4552.6  593.57  4682.2  596.39  4720.0  594.88  4738.1  585.67
  4781.7  574.10  4957.8  571.28  4960.5  570.78  4985.8  571.28  4991.8  574.14
  5140.4  573.80  5161.9  572.58  5231.9  585.30  5271.9  586.16  6427.8  583.77
  6602.5  576.51  6622.5  582.82  6662.5  583.49  6692.5  577.13  6722.5  583.20
  6872.6  585.46  6951.4  596.37  7012.6  602.60  7082.7  617.75  7157.5  619.21
#Mann=10,-1,0
  3676.6   0.075       0  4012.5    0.05       0  4167.7   0.075       0
  4289.7    0.05       0  4682.2   0.075       0  4957.8    0.07       0
  4985.8   0.075       0  5140.4    0.05       0  6427.8    0.12       0
  6951.4    0.05       0
#XS Ineff=2,0
       0                 5286.20    0.00  600.29
Permanent Ineff=
       F       F
Bank Sta=4957.8,4985.8
Exp/Cntr=0.3,0.1

Type RM Length L Ch R = 1,4093,614,614,614
BEGIN DESCRIPTION:
Henrietta Creek 5.0
END DESCRIPTION:
XS GIS Cut Line= 3
      2346528.98      7053260.03      2347279.41      7052437.28
      2349161.37      7052347.00
#Sta/Elev= 30
  3938.1  601.20  3980.4  595.13  4122.2  591.66  4384.4  594.76  4914.8  585.31
  4973.7  574.24  5014.1  572.39  5042.4  581.43  5071.3  583.86  5208.3  583.86
  5326.1  584.55  5641.9  579.85  5713.5  582.19  5742.1  577.46  5772.1  581.82
  6322.7  581.06  6349.6  574.52  6372.8  575.59  6392.8  572.08  6402.8  576.29
  6422.8  576.58  6428.8  571.61  6431.6  571.11  6456.9  571.61  6472.9  579.06
  6543.0  584.06  6559.1  591.29  6663.1  616.92  6768.3  617.78  6935.8  620.02
#Mann=8,-1,0
  3938.1    0.05       0  4973.7    0.12       0  5208.3    0.05       0
  5326.1   0.075       0  5713.5    0.12       0  6428.8    0.07       0
  6456.9    0.12       0  6768.3    0.05       0
Bank Sta=6428.8,6456.9
Exp/Cntr=0.3,0.1

Type RM Length L Ch R = 1,3479,1618,1618,1618
BEGIN DESCRIPTION:
Henrietta Creek 4.0
END DESCRIPTION:
XS GIS Cut Line= 3
      2346928.99      7053460.01      2347841.91      7052555.33
      2349279.44      7052562.28
#Sta/Elev= 30
  3833.0  595.80  4080.5  591.44  4722.8  590.78  4801.8  590.30  4865.4  583.61
  4909.6  583.35  4943.2  581.27  4969.1  571.16  5006.9  568.31  5009.7  567.81
  5035.0  568.31  5035.1  581.74  5045.2  582.57  5213.1  583.04  5365.3  582.43
  5385.3  579.65  5395.3  572.88  5425.3  581.73  5955.3  581.20  5975.3  580.70
  5995.4  569.24  6015.4  574.10  6025.4  568.67  6045.4  569.62  6185.4  601.39
  6225.7  606.52  6275.4  612.58  6345.4  608.94  6485.4  623.83  6555.8  627.03
#Mann=9,-1,0
  3833.0    0.05       0  4722.8    0.12       0  4909.6    0.05       0
  4969.1    0.12       0  5006.9    0.07       0  5035.0    0.12       0
  5045.2   0.075       0  5213.1    0.12       0  6225.7    0.05       0
Bank Sta=5006.9,5035
Exp/Cntr=0.3,0.1

Type RM Length L Ch R = 1,1861,658,658,658
BEGIN DESCRIPTION:
Henrietta Creek 3.0
END DESCRIPTION:
XS GIS Cut Line= 4
      2347307.17      7053402.56      2348363.97      7053069.81
      2348966.91      7053117.83      2349478.96      7053060.01
#Sta/Elev= 30
  3272.6  593.50  3280.6  593.17  3421.4  590.95  3730.6  593.03  3788.2  588.08
  3922.8  589.27  4000.1  581.51  4418.9  581.00  4525.7  580.02  4594.8  580.14
  4766.8  575.26  4951.0  578.32  4989.0  574.59  5006.6  568.66  5011.7  571.21
  5013.6  565.35  5016.4  564.85  5042.0  565.35  5101.5  567.62  5138.5  582.35
  5189.2  585.41  5239.1  583.48  5259.2  578.67  5276.1  588.48  5281.2  586.38
  5309.5  595.59  5329.7  597.07  5349.8  591.81  5420.2  604.34  5500.7  626.78
#Mann=10,-1,0
  3272.6    0.05       0  3280.6   0.075       0  3421.4    0.05       0
  3922.8     0.1       0  4418.9    0.12       0  4525.7     0.1       0
  4594.8    0.12       0  5013.6    0.07       0  5042.0    0.12       0
  5189.2    0.05       0
Bank Sta=5013.6,5042
Exp/Cntr=0.3,0.1

Type RM Length L Ch R = 1,1203,562,562,562
BEGIN DESCRIPTION:
Henrietta Creek 2.0
END DESCRIPTION:
XS GIS Cut Line= 3
      2348078.96      7053460.01      2348579.00      7053310.00
      2349378.98      7053360.00
#Sta/Elev= 30
  4473.9  589.43  4484.4  590.83  4490.5  587.69  4528.8  581.26  4863.9  580.27
  4964.6  579.06  4985.5  562.43  4991.8  562.14  4994.6  561.64  5020.2  562.14
  5026.0  563.82  5036.0  569.55  5046.1  571.73  5078.6  570.49  5096.2  573.96
  5126.2  576.41  5166.3  574.59  5196.3  575.54  5206.4  572.09  5216.4  572.01
  5226.4  576.59  5238.9  578.40  5276.5  579.00  5316.6  578.08  5336.6  574.62
  5346.6  577.79  5399.2  581.15  5577.1  585.52  5719.9  590.36  5797.5  594.53
#Mann=4,-1,0
  4473.9     0.1       0  4863.9    0.12       0  4991.8    0.07       0
  5020.2    0.12       0
Bank Sta=4991.8,5020.2
Exp/Cntr=0.3,0.1

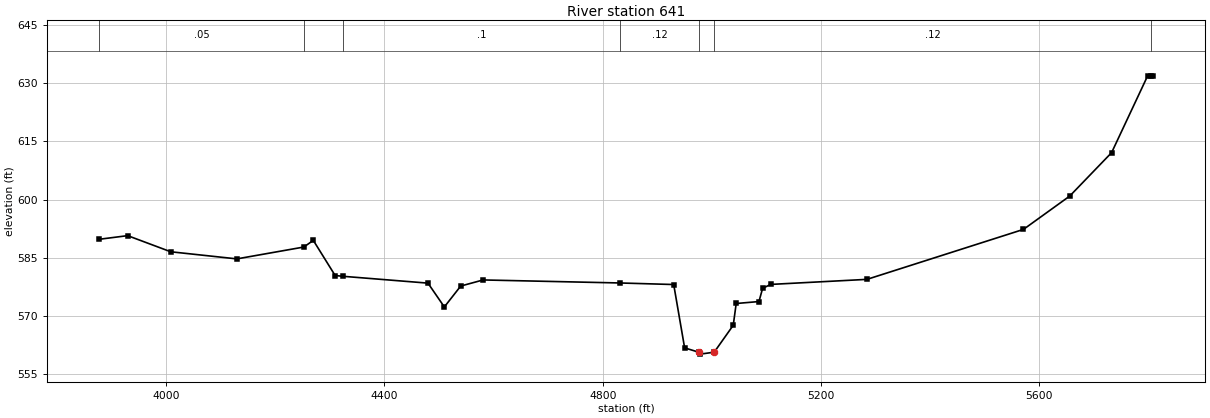
Type RM Length L Ch R = 1,641,0,0,0
BEGIN DESCRIPTION:
Henrietta Creek 1.0
END DESCRIPTION:
XS GIS Cut Line= 3
      2347807.17      7053749.78      2348929.00      7053710.00
      2349678.99      7053410.00
#Sta/Elev= 30
  3877.5  589.78  3929.4  590.71  4008.4  586.56  4129.5  584.73  4252.2  587.78
  4269.6  589.49  4309.6  580.45  4324.8  580.24  4479.7  578.49  4509.7  572.36
  4539.7  577.74  4580.8  579.31  4832.1  578.53  4930.0  578.13  4950.0  561.83
  4975.8  560.72  4978.6  560.22  5004.2  560.72  5039.1  567.65  5044.5  573.25
  5086.2  573.75  5092.9  577.15  5107.7  578.16  5284.1  579.46  5570.9  592.32
  5655.7  600.90  5732.4  612.07  5798.4  631.82  5805.4  631.84  5807.8  631.84
#Mann=7,-1,0
  3877.5    0.05       0  4252.2    0.12       0  4324.8     0.1       0
  4832.1    0.12       0  4975.8    0.07       0  5004.2    0.12       0
  5805.4    0.05       0
Bank Sta=4975.8,5004.2
Exp/Cntr=0.3,0.1

Chan Stop Cuts=-1