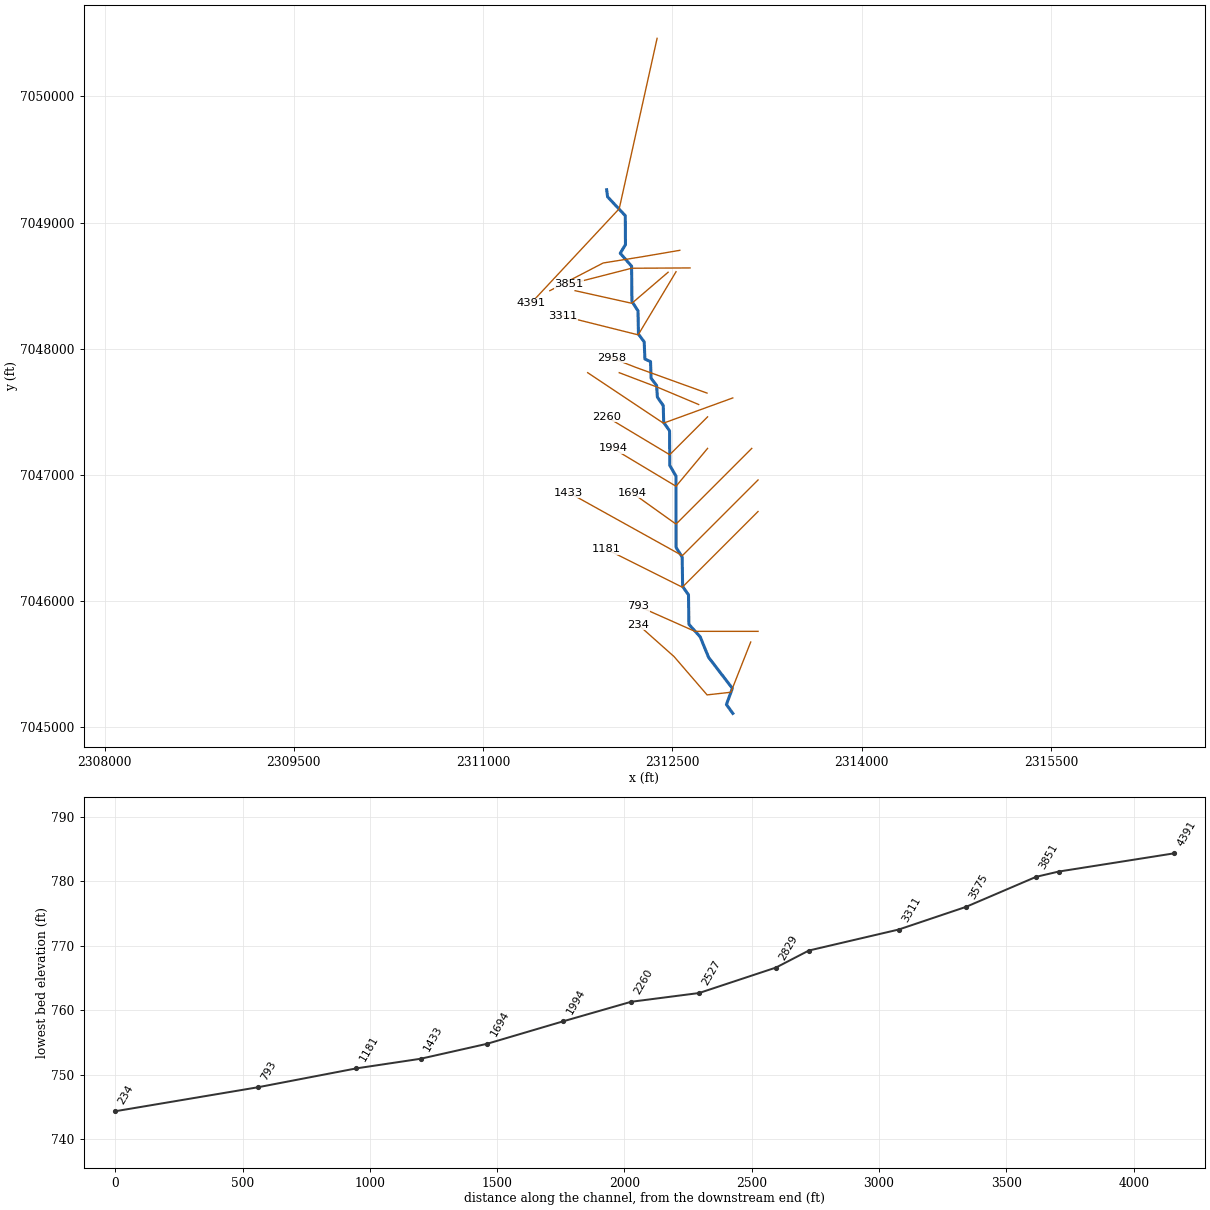
--- Henrietta Creek 5.prj (project) ---

Proj Title=Henrietta Creek 5 Base Level Engineering
Current Plan=p01
Default Exp/Contr=0.3,0.1
English Units
Geom File=g01
Flow File=f01
Plan File=p01
Y Axis Title=Elevation
X Axis Title(PF)=Main Channel Distance
X Axis Title(XS)=Station
BEGIN DESCRIPTION:
Henrietta Creek 5
END DESCRIPTION:
DSS File=dss
DSS Export Rating Curves= 0
DSS Export Rating Curve Sorted= 0
DSS Export Volume Flow Curves= 0
DXF OffsetX= 0
DXF OffsetY= 0
DXF ScaleX= 1
DXF ScaleY= 10

--- Henrietta Creek 5.p01 (plan) ---

Plan Title=Multiple Run
Program Version=4.10
Short Identifier=Multiple Run
Geom File=g01
Flow File=f01
Subcritical Flow
K Sum by GR= 0
Std Step Tol= 0.01
Critical Tol= 0.01
Num of Std Step Trials= 20
Max Error Tol= 0.3
Flow Tol Ratio= 0.001
Split Flow NTrial= 30
Split Flow Tol= 0.02
Split Flow Ratio= 0.02
Log Output Level= 0
Friction Slope Method= 0
Unsteady Friction Slope Method= 2
Unsteady Bridges Friction Slope Method= 1
Parabolic Critical Depth
Global Vel Dist= 1 , 1 , 1
Global Log Level= 0
CheckData=True
Encroach Param=-1 ,0,0, 0
BEGIN DESCRIPTION:
Multiple Run
END DESCRIPTION:
Computation Interval=1HOUR
Output Interval=1HOUR
Run HTab= 0
Run UNet= 0
Run PostProcess= 0
Run WQNet= 0
UNET Theta= 1
UNET Theta Warmup= 1
UNET ZTol= 0.02
UNET ZSATol= 0.05
UNET MxIter= 20
UNET MaxInSteps= 0
UNET DtIC= 0
UNET DtMin= 0
UNET MaxCRTS= 20
UNET WFStab= 2
UNET SFStab= 1
UNET WFX= 1
UNET SFX= 1
UNET DSS MLevel= 4
UNET DZMax Abort= 100
UNET Convert EG Bridges= 0
UNET Use Existing IB Tables=-1
UNET Froude Reduction=False
UNET Froude Limit= 1
UNET Froude Power= 10
UNET Time Slicing=0,0, 5
UNET Junction Losses=0
Instantaneous Interval=1HOUR
DSS File=dss
Write IC File= 0
Write IC File at Sim End=0
Echo Input=False
Echo Parameters=False
Echo Output=False
Write Detailed= 0
WQ AD Non Conservative
WQ ULTIMATE=-1
WQ Max Comp Step=1HOUR
WQ Output Interval=15MIN
WQ Output Selected Increments= 0
WQ Output face flow=0
WQ Output face velocity=0
WQ Output face area=0
WQ Output face dispersion=0
WQ Output cell volume=0
WQ Output cell surface area=0
WQ Output cell continuity=0
WQ Output cumulative cell continuity=0
WQ Output face conc=0
WQ Output face dconc_dx=0
WQ Output face courant=0
WQ Output face peclet=0
WQ Output face adv mass=0
WQ Output face disp mass=0
WQ Output cell mass=0
WQ Output cell source sink temp=0
WQ Output cell source sink nsm=0
WQ Output MaxMinRange=-1
WQ Daily Max Min Mean=-1
WQ Daily Range=0
WQ Daily Time=0
WQ Create Restart=0
WQ Fixed Restart=0
WQ System Summary=0
WQ Use Fixed Temperature=0
Sorting and Armoring Iterations= 10
XS Update Threshold= 0.02
Hydraulics Update Threshold= 0.02
Energy Slope Method= 1
Volume Change Method= 0
XS Weighting Method= 0
Number of US Weighted Cross Sections= 1
Number of DS Weighted Cross Sections= 1
Upstream XS Weight=0.25
Main XS Weight=0.5
Downstream XS Weight=0.25
Number of DS XS's Weighted with US Boundary= 1
Upstream Boundary Weight= 1
Weight of XSs Associated with US Boundary= 0
Number of US XS's Weighted with DS Boundary= 1
Downstream Boundary Weight= 0.5
Weight of XSs Associated with DS Boundary= 0.5
Sediment Output Level= 4
Mass or Volume Output= 0
Output Increment Type= 1
Profile and TS Output Increment= 10
XS Output Flag= 0
XS Output Increment= 10
Disregard all LS=0
Disregard all Conn=0
Disregard all Breaches=0
Disregard all Pumps=0

--- Henrietta Creek 5.f01 (steady flow) ---

Flow Title=Multiple
Number of Profiles=7
Profile Names=10-year,25-year,50-year,1pct_min,100-year,1pct_plu,500-year
River Rch & RM= Henrietta Creek ,Reach-1,4391
     459     615     740     442     882    1760    1250
River Rch & RM= Henrietta Creek ,Reach-1,793
     453     608     733     439     875    1750    1250
Boundary for River Rch & Prof#=Henrietta Creek ,Reach-1,1
Up Type=0
Dn Type=3
Dn Slope=0.005
Boundary for River Rch & Prof#=Henrietta Creek ,Reach-1,2
Up Type=0
Dn Type=3
Dn Slope=0.005
Boundary for River Rch & Prof#=Henrietta Creek ,Reach-1,3
Up Type=0
Dn Type=3
Dn Slope=0.005
Boundary for River Rch & Prof#=Henrietta Creek ,Reach-1,4
Up Type=0
Dn Type=3
Dn Slope=0.005
Boundary for River Rch & Prof#=Henrietta Creek ,Reach-1,5
Up Type=0
Dn Type=3
Dn Slope=0.005
Boundary for River Rch & Prof#=Henrietta Creek ,Reach-1,6
Up Type=0
Dn Type=3
Dn Slope=0.005
Boundary for River Rch & Prof#=Henrietta Creek ,Reach-1,7
Up Type=0
Dn Type=3
Dn Slope=0.005

--- Henrietta Creek 5.g01 (geometry) ---

Geom Title=Existing Conditions
Program Version=4.10

River Reach=Henrietta Creek ,Reach-1
Reach XY= 30
        2311979.        7049260.      2311986.76      7049203.79
      2312126.94      7049054.15      2312128.34      7048825.16
      2312086.81      7048756.59      2312176.93      7048654.15
      2312179.52      7048375.22      2312227.78      7048299.49
      2312231.26      7048115.94      2312276.72      7048054.05
      2312282.47      7047918.47      2312327.02      7047898.03
      2312331.27      7047765.95      2312375.14       7047708.4
      2312381.36      7047615.98      2312427.77      7047549.49
      2312431.27      7047415.94      2312477.78       7047349.5
      2312479.52      7047075.22      2312528.93      7046989.97
      2312529.52      7046425.22      2312577.78       7046349.5
      2312581.26      7046115.94      2312627.78       7046049.5
      2312631.06      7045815.86      2312720.84      7045716.05
      2312787.14      7045553.94      2312975.66      7045308.28
      2312928.46      7045180.22        2312979.        7045110.

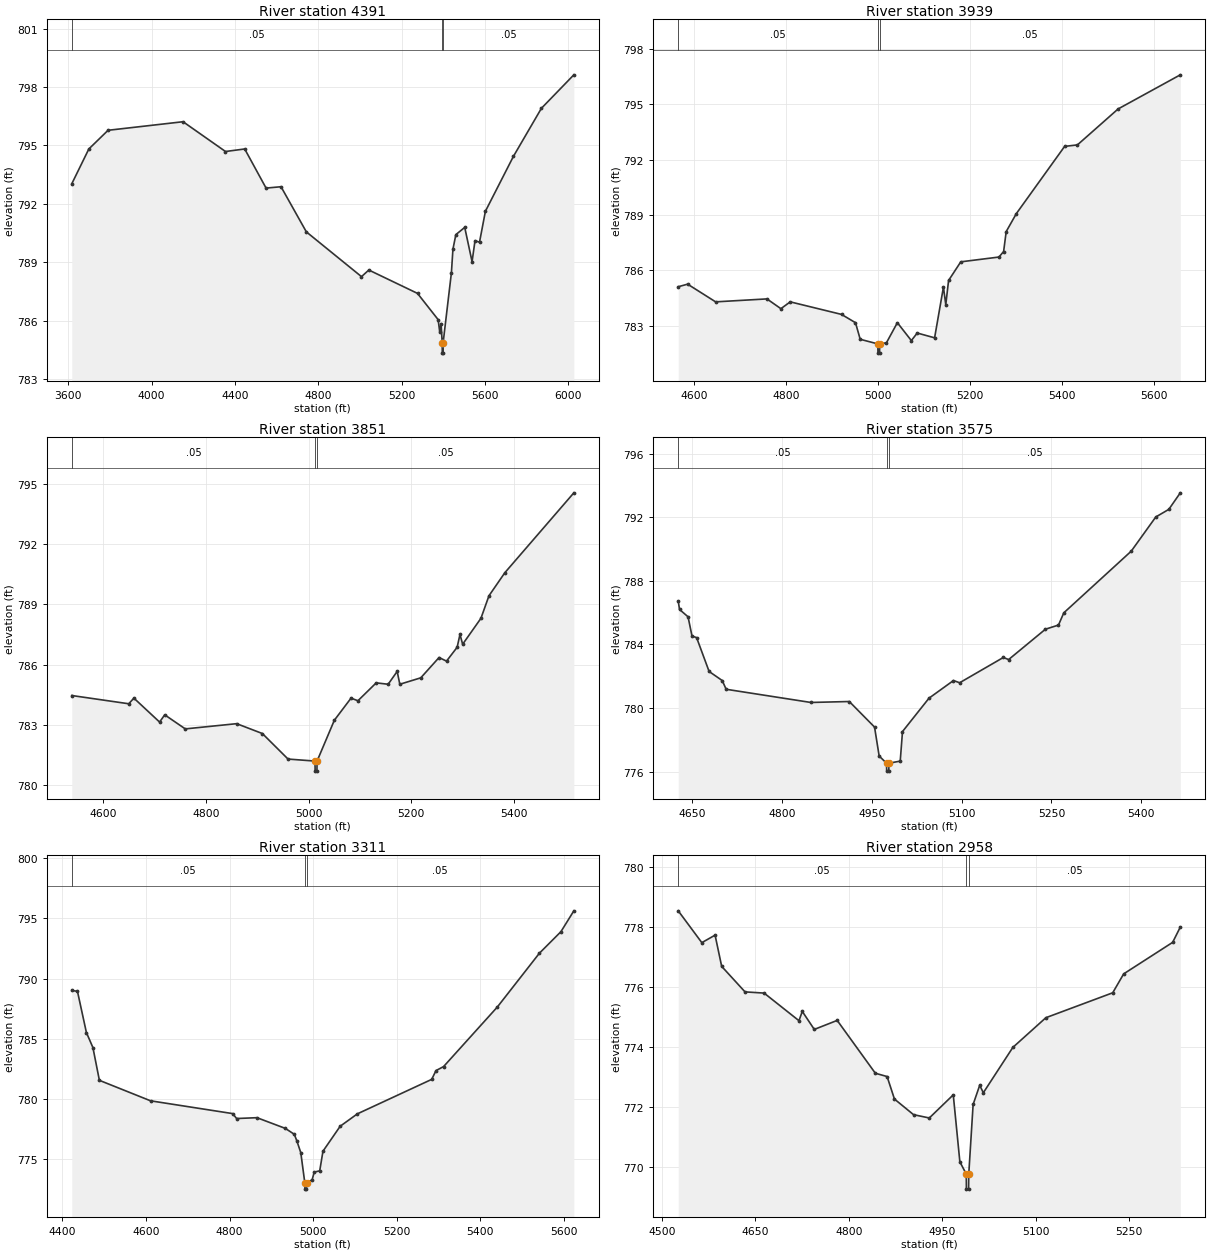
Type RM Length L Ch R = 1 ,4391    ,452,452,452
BEGIN DESCRIPTION:
Henrietta Creek 5 14.0
END DESCRIPTION:
XS GIS Cut Line= 3
      2312378.99      7050459.96        2312079.        7049110.
      2311379.01      7048360.01
#Sta/Elev= 30
  3617.4  793.03  3699.3  794.82  3791.5  795.78  4151.3  796.22  4354.9  794.69
  4447.1  794.82  4549.6  792.81  4621.3  792.88  4742.9  790.56  5007.4  788.26
  5042.6   788.6  5276.1   787.4  5375.2  786.05  5382.6  785.43  5389.4  785.85
  5394.7  784.83    5395  784.33  5398.5  784.33  5398.7  784.83  5438.8  788.46
  5446.1  789.67  5460.2  790.42  5502.7  790.79  5537.9  789.03  5552.1  790.11
  5573.6  790.03  5601.9  791.62  5736.3  794.44  5870.6  796.91  6026.2  798.63
#Mann= 3 ,-1 , 0
  3617.4     .05       0  5394.7     .04       0  5398.7     .05       0
Bank Sta=5394.7,5398.7
XS Rating Curve= 0 ,0
Exp/Cntr=0.3,0.1

Type RM Length L Ch R = 1 ,3939    ,88,88,88
BEGIN DESCRIPTION:
Henrietta Creek 5 13.0
END DESCRIPTION:
XS GIS Cut Line= 4
      2312559.11      7048779.91      2312257.88      7048728.48
      2311951.76       7048679.5      2311528.96      7048459.98
#Sta/Elev= 30
  4565.7  785.11  4586.1  785.25    4647  784.29  4758.6  784.45    4789  783.92
  4809.3  784.29  4920.8  783.61  4951.2  783.16  4961.5  782.26  4999.8  782.01
  5000.1  781.51  5003.6  781.51  5003.8  782.01  5018.5  782.07  5042.3  783.16
  5072.7  782.19  5085.5   782.6  5123.3  782.34  5142.5  785.09  5147.6  784.14
  5153.7  785.45  5180.2  786.46  5263.3  786.72  5273.4  787.02    5279   788.1
  5301.2  789.08  5406.1  792.72  5433.9   792.8  5522.4  794.75  5657.7   796.6
#Mann= 3 ,-1 , 0
  4565.7     .05       0  4999.8    .033       0  5003.8     .05       0
Bank Sta=4999.8,5003.8
XS Rating Curve= 0 ,0
Exp/Cntr=0.3,0.1

Type RM Length L Ch R = 1 ,3851    ,276,276,276
BEGIN DESCRIPTION:
Henrietta Creek 5 12.0
END DESCRIPTION:
XS GIS Cut Line= 3
      2312639.94      7048640.32      2312177.07      7048637.87
        2311679.        7048510.
#Sta/Elev= 30
  4539.2  784.46  4650.1  784.05  4660.1  784.33  4710.1  783.14  4720.1   783.5
  4760.1   782.8  4860.1  783.06  4910.1  782.57  4960.1   781.3  5012.6   781.2
  5012.8   780.7  5016.3   780.7  5016.6   781.2  5050.2  783.23  5082.7  784.33
  5096.1   784.2  5131.7  785.09  5154.9  785.02  5172.5  785.66  5177.6  785.02
  5218.4  785.34    5254  786.35  5268.5  786.17  5289.2  786.86  5294.7   787.5
  5299.9  787.01  5335.5   788.3  5351.1  789.42  5382.1  790.57  5516.3  794.54
#Mann= 3 ,-1 , 0
  4539.2     .05       0  5012.6    .033       0  5016.6     .05       0
Bank Sta=5012.6,5016.6
XS Rating Curve= 0 ,0
Exp/Cntr=0.3,0.1

Type RM Length L Ch R = 1 ,3575    ,264,264,264
BEGIN DESCRIPTION:
Henrietta Creek 5 11.0
END DESCRIPTION:
XS GIS Cut Line= 3
      2312466.07      7048606.05        2312179.        7048360.
      2311728.97      7048460.01
#Sta/Elev= 30
  4626.3  786.72  4628.5   786.2  4642.7  785.74  4649.3  784.53    4657  784.43
  4677.9   782.3  4699.8  781.73  4706.4  781.18    4848  780.35  4912.2  780.41
  4954.4   778.8  4962.1  776.98  4974.4  776.53  4974.7  776.03  4978.2  776.03
  4978.4  776.53  4997.3  776.66  5001.1  778.52  5045.4  780.62  5086.3  781.73
  5096.6  781.59  5169.6  783.18  5178.5  783.05    5240  784.96  5261.8  785.22
  5270.7  785.99  5383.4  789.87  5424.4  792.02  5446.2   792.5  5465.4  793.54
#Mann= 3 ,-1 , 0
  4626.3     .05       0  4974.4    .033       0  4978.4     .05       0
Bank Sta=4974.4,4978.4
XS Rating Curve= 0 ,0
Exp/Cntr=0.3,0.1

Type RM Length L Ch R = 1 ,3311    ,353,353,353
BEGIN DESCRIPTION:
Henrietta Creek 5 10.0
END DESCRIPTION:
XS GIS Cut Line= 3
      2312529.01      7048610.02        2312229.        7048110.
      2311628.99        7048260.
#Sta/Elev= 30
  4422.2  789.01  4435.8  788.94  4457.2  785.52  4472.8  784.27  4488.3  781.55
  4610.8  779.85  4807.1  778.79  4816.8  778.38  4865.4  778.45  4933.4  777.56
  4954.8  777.07  4960.6  776.55  4970.3  775.55    4980  773.02  4980.3  772.52
  4983.8  772.52    4984  773.02  4997.5   773.3  5002.4  773.93  5015.6  774.04
  5023.4  775.67  5064.6  777.74  5105.8  778.77  5283.6  781.63  5293.9  782.36
    5312  782.69  5440.8  787.64  5541.3   792.1  5592.9  793.89  5623.8  795.62
#Mann= 3 ,-1 , 0
  4422.2     .05       0    4980    .033       0    4984     .05       0
Bank Sta=4980,4984
XS Rating Curve= 0 ,0
Exp/Cntr=0.3,0.1

Type RM Length L Ch R = 1 ,2958    ,129,129,129
BEGIN DESCRIPTION:
Henrietta Creek 5 9.0
END DESCRIPTION:
XS GIS Cut Line= 3
      2312774.66      7047648.48      2312211.35      7047851.76
      2312017.88      7047927.68
#Sta/Elev= 30
  4525.9  778.53  4563.8  777.47  4585.1  777.72  4595.7  776.68  4633.2  775.83
  4663.9  775.79  4719.9  774.87  4725.2  775.18  4744.5  774.58  4781.3  774.88
  4842.6  773.12  4861.5  773.01  4873.3  772.26    4904  771.74  4929.3  771.63
  4967.8   772.4  4978.4  770.17  4988.7  769.76  4988.9  769.26  4992.4  769.26
  4992.7  769.76  4999.7  772.08  5010.3  772.72  5016.1  772.47  5063.5  773.98
  5116.6  774.97    5224   775.8  5241.6  776.43  5320.3  777.48  5332.6  777.99
#Mann= 3 ,-1 , 0
  4525.9     .05       0  4988.7    .055       0  4992.7     .05       0
Bank Sta=4988.7,4992.7
XS Rating Curve= 0 ,0
Exp/Cntr=0.5,0.3

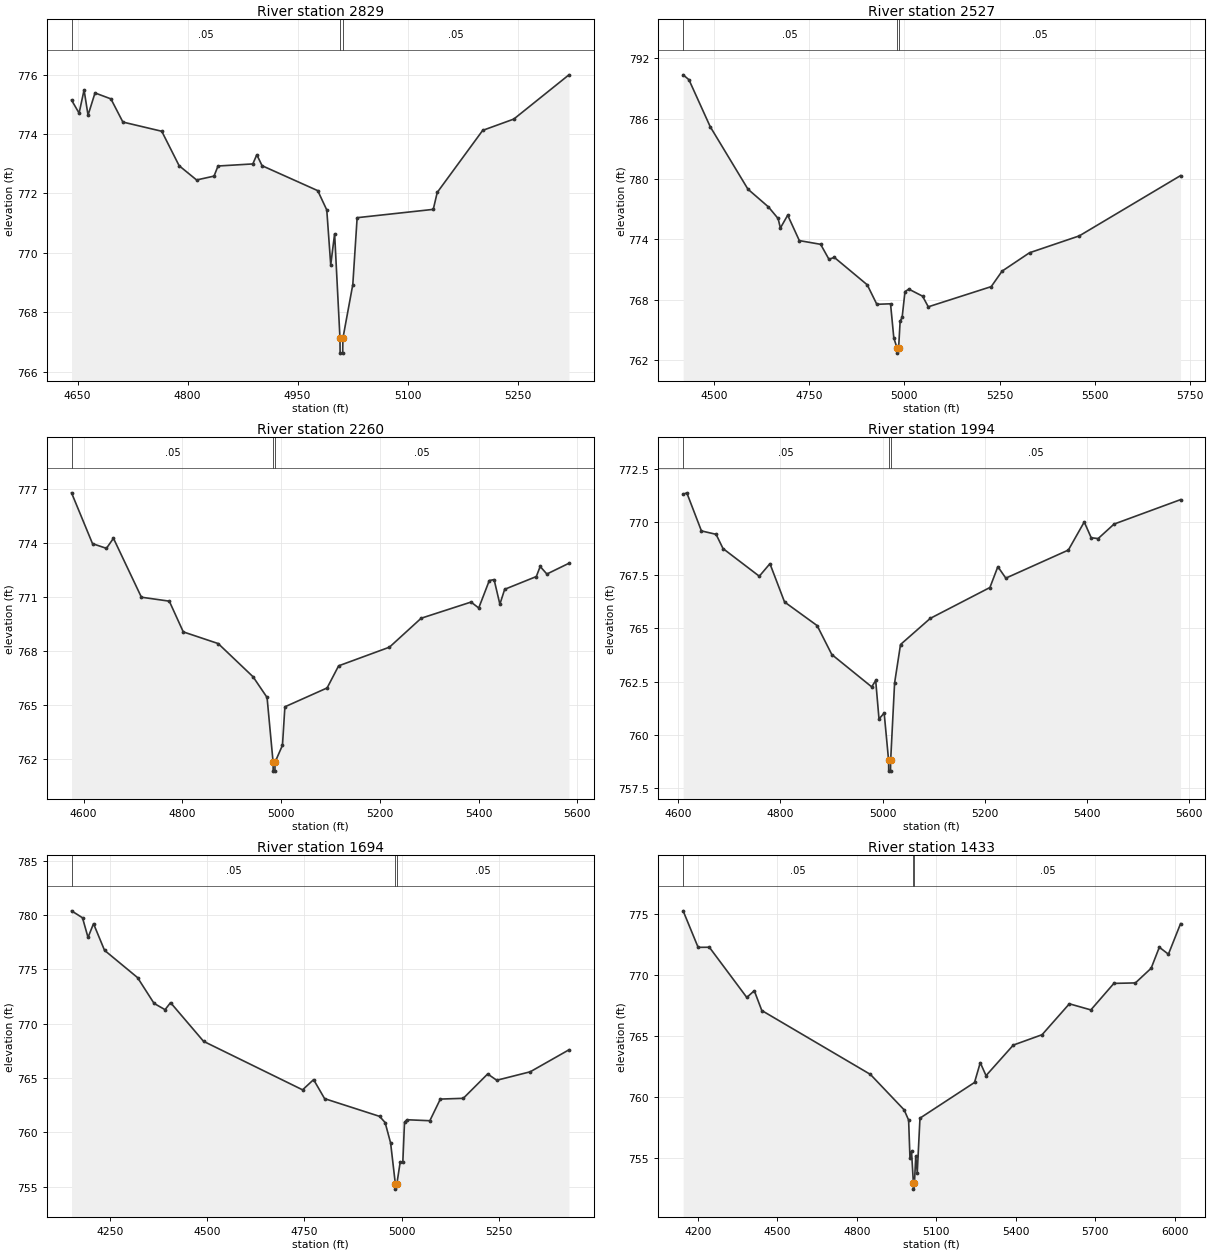
Type RM Length L Ch R = 1 ,2829    ,302,302,302
BEGIN DESCRIPTION:
Henrietta Creek 5 8.0
END DESCRIPTION:
XS GIS Cut Line= 3
      2312708.53      7047557.87      2312387.68      7047692.57
      2312079.04      7047809.99
#Sta/Elev= 30
  4641.8  775.14  4652.1   774.7  4658.9  775.48  4664.3  774.63  4673.8  775.38
  4695.5  775.18  4711.8   774.4  4764.8  774.09  4788.5  772.93  4812.3  772.45
  4836.1  772.58  4841.5  772.92    4889  772.99  4894.4   773.3  4901.6  772.93
  4977.5  772.09  4989.8  771.44  4995.2  769.59  5000.5  770.64  5007.8  767.12
    5008  766.62  5011.5  766.62  5011.8  767.12  5025.3  768.93  5031.2  771.18
    5135  771.46  5140.4  772.03  5202.4  774.12  5244.8   774.5    5320  775.99
#Mann= 3 ,-1 , 0
  4641.8     .05       0  5007.8    .033       0  5011.8     .05       0
Bank Sta=5007.8,5011.8
XS Rating Curve= 0 ,0
Exp/Cntr=0.5,0.3

Type RM Length L Ch R = 1 ,2527    ,267,267,267
BEGIN DESCRIPTION:
Henrietta Creek 5 7.0
END DESCRIPTION:
XS GIS Cut Line= 3
      2312978.98      7047609.99        2312429.        7047410.
      2311829.02      7047809.98
#Sta/Elev= 30
  4418.9  790.37  4434.2  789.88    4490  785.21  4589.1  778.99    4643  777.22
  4668.3  776.07  4674.3  775.12  4693.5   776.4  4724.1  773.87    4780   773.5
  4801.9  772.01  4815.9   772.2  4902.4  769.47  4927.6  767.53  4963.6  767.58
  4972.2  764.18  4980.8  763.17  4981.1  762.67  4984.8  763.17  4988.8  765.84
  4994.1  766.24  5001.5  768.79  5011.6  769.04  5047.7  768.34  5062.7  767.28
    5228  769.29  5256.5  770.83  5328.6  772.66  5459.3  774.34  5725.2  780.34
#Mann= 3 ,-1 , 0
  4418.9     .05       0  4980.8    .033       0  4984.8     .05       0
Bank Sta=4980.8,4984.8
XS Rating Curve= 0 ,0
Exp/Cntr=0.3,0.1

Type RM Length L Ch R = 1 ,2260    ,266,266,266
BEGIN DESCRIPTION:
Henrietta Creek 5 6.0
END DESCRIPTION:
XS GIS Cut Line= 3
      2312779.03      7047460.03        2312479.        7047160.
        2311979.        7047460.
#Sta/Elev= 30
  4575.6   776.8  4618.1  773.97  4646.3  773.71  4660.5  774.27  4717.1  770.99
  4773.6  770.77  4801.9  769.06  4872.6  768.41  4943.3  766.56  4971.6  765.41
  4983.8  761.81    4984  761.31  4987.5  761.31  4987.8  761.81  5002.8  762.75
  5007.7  764.89  5093.2  765.94  5116.5  767.17  5219.5  768.21  5283.7  769.82
  5384.7  770.72  5400.3  770.39  5421.7  771.92  5431.4  771.97  5443.1   770.6
  5452.8  771.43  5516.9  772.14  5524.7   772.7  5538.3  772.28    5583  772.88
#Mann= 3 ,-1 , 0
  4575.6     .05       0  4983.8    .033       0  4987.8     .05       0
Bank Sta=4983.8,4987.8
XS Rating Curve= 0 ,0
Exp/Cntr=0.3,0.1

Type RM Length L Ch R = 1 ,1994    ,300,300,300
BEGIN DESCRIPTION:
Henrietta Creek 5 5.0
END DESCRIPTION:
XS GIS Cut Line= 3
      2312779.02      7047210.03        2312529.        7046910.
      2312029.04      7047209.98
#Sta/Elev= 30
  4609.6   771.3  4616.8  771.37  4645.4  769.58  4674.1  769.42  4687.7  768.75
  4758.7  767.45  4779.5  768.04  4808.1  766.24  4871.9  765.13  4900.6  763.77
  4978.7  762.25  4986.5  762.55    4993  760.74  5003.1  761.02  5011.8  758.79
    5012  758.29  5015.5  758.29  5015.8  758.79  5023.5  762.43  5035.1  764.24
  5093.4  765.47  5210.1  766.92  5225.6   767.9  5241.2  767.36  5363.6  768.68
  5394.7     770  5408.3  769.26  5421.9  769.22    5453   769.9  5583.2  771.05
#Mann= 3 ,-1 , 0
  4609.6     .05       0  5011.8    .033       0  5015.8     .05       0
Bank Sta=5011.8,5015.8
XS Rating Curve= 0 ,0
Exp/Cntr=0.3,0.1

Type RM Length L Ch R = 1 ,1694    ,261,261,261
BEGIN DESCRIPTION:
Henrietta Creek 5 4.0
END DESCRIPTION:
XS GIS Cut Line= 3
      2313128.97      7047209.97        2312529.        7046610.
        2312179.        7046860.
#Sta/Elev= 30
  4151.5  780.38  4179.7  779.74  4193.9  777.93    4208   779.2  4236.3  776.75
  4321.2  774.24  4363.6  771.87  4391.9  771.29    4406  771.94  4490.9  768.38
  4745.4  763.92  4773.7  764.86    4802  763.11  4943.4  761.48  4957.6  760.91
  4971.7  759.03  4983.8  755.29  4984.1  754.79  4987.8  755.29  4996.4   757.3
  5003.1   757.3  5007.4  760.93  5013.5  761.17  5072.5  761.08  5099.5  763.07
  5158.5  763.14  5221.2  765.38  5244.5   764.8  5330.6  765.58  5430.1   767.6
#Mann= 3 ,-1 , 0
  4151.5     .05       0  4983.8    .033       0  4987.8     .05       0
Bank Sta=4983.8,4987.8
XS Rating Curve= 0 ,0
Exp/Cntr=0.3,0.1

Type RM Length L Ch R = 1 ,1433    ,252,252,252
BEGIN DESCRIPTION:
Henrietta Creek 5 3.0
END DESCRIPTION:
XS GIS Cut Line= 3
      2313179.01      7046960.01        2312579.        7046360.
        2311679.        7046860.
#Sta/Elev= 30
  4143.9  775.25  4200.5  772.26  4242.9  772.27  4384.3  768.16  4412.6  768.71
  4440.9  767.09    4851  761.86  4978.3  758.96  4995.3  758.12  5000.4  755.02
  5006.2  755.57  5013.3  752.97  5013.6  752.47  5017.3  752.97  5022.2  755.16
  5027.9  753.83  5038.2  758.28  5244.1   761.2  5265.8  762.82  5287.6  761.76
  5390.5  764.26  5499.2  765.11  5602.2  767.64  5683.4  767.14  5770.3  769.31
  5851.6  769.35    5911  770.55  5941.9  772.27  5976.2   771.7    6022   774.2
#Mann= 3 ,-1 , 0
  4143.9     .05       0  5013.3    .033       0  5017.3     .05       0
Bank Sta=5013.3,5017.3
XS Rating Curve= 0 ,0
Exp/Cntr=0.3,0.1

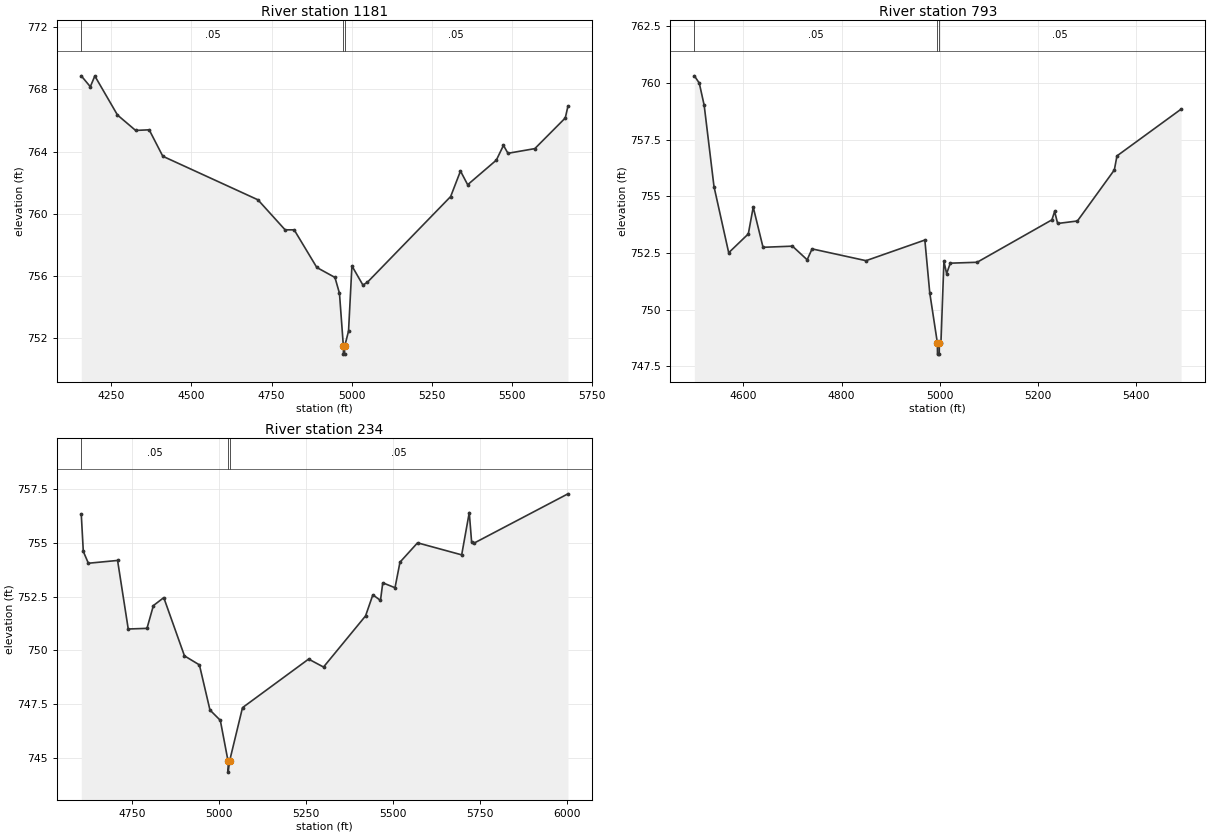
Type RM Length L Ch R = 1 ,1181    ,388,388,388
BEGIN DESCRIPTION:
Henrietta Creek 5 2.0
END DESCRIPTION:
XS GIS Cut Line= 3
      2313179.01      7046710.01        2312579.        7046110.
      2311978.96      7046410.02
#Sta/Elev= 30
    4156  768.87  4184.3  768.17  4198.4  768.86  4269.1  766.35  4325.7  765.36
  4368.1   765.4  4410.6   763.7  4707.6   760.9  4792.4  758.97  4820.7  758.97
  4891.4  756.55    4948  755.91  4962.1  754.89  4974.3  751.48  4974.5  750.98
    4978  750.98  4978.3  751.48  4990.4  752.46    5001  756.65  5035.3  755.42
  5049.3   755.6  5309.2  761.11  5339.9  762.75  5362.3  761.87  5451.8  763.45
  5474.1   764.4  5488.1  763.89  5571.9  764.19    5667  766.16  5675.4  766.92
#Mann= 3 ,-1 , 0
    4156     .05       0  4974.3    .033       0  4978.3     .05       0
Bank Sta=4974.3,4978.3
XS Rating Curve= 0 ,0
Exp/Cntr=0.3,0.1

Type RM Length L Ch R = 1 ,793     ,559,559,559
BEGIN DESCRIPTION:
Henrietta Creek 5 1.0
END DESCRIPTION:
XS GIS Cut Line= 3
      2313179.02        7045760.        2312679.        7045760.
      2312228.96      7045960.02
#Sta/Elev= 30
  4499.9  760.31  4509.9  759.99  4519.9  759.01  4539.9  755.43  4569.9  752.51
  4609.9  753.34  4619.9  754.52  4639.9  752.75  4699.9   752.8  4729.9   752.2
  4739.9  752.68  4849.9  752.16  4969.9  753.07  4979.9  750.74  4995.4  748.54
  4995.7  748.04  4999.2  748.04  4999.4  748.54  5002.7  748.54  5008.8  752.13
  5014.3  751.59  5021.8  752.05  5076.5  752.09    5229  753.96  5234.5  754.33
  5240.7   753.8    5281  753.91  5356.3  756.16  5361.7  756.78  5492.4  758.84
#Mann= 3 ,-1 , 0
  4499.9     .05       0  4995.4    .033       0  4999.4     .05       0
Bank Sta=4995.4,4999.4
XS Rating Curve= 0 ,0
Exp/Cntr=0.3,0.1

Type RM Length L Ch R = 1 ,234     ,0,0,0
BEGIN DESCRIPTION:
Henrietta Creek 5 0.5
END DESCRIPTION:
XS GIS Cut Line= 5
       2313120.9      7045675.48      2312963.77      7045277.42
      2312775.21      7045256.47      2312513.32      7045560.26
      2312230.47      7045811.68
#Sta/Elev= 30
  4604.8  756.34  4610.7   754.6  4625.2  754.05  4709.1  754.18  4739.7  750.99
  4793.5  751.02  4811.9  752.08  4841.7  752.45  4901.1  749.74    4944  749.32
  4974.3  747.22    5004  746.74  5026.4  744.83  5026.6  744.33  5030.4  744.83
  5067.7  747.33  5257.5  749.59  5300.3  749.22    5421   751.6  5441.9  752.58
  5463.8  752.32  5470.4  753.14  5505.5  752.91  5519.8   754.1  5570.2     755
  5696.9  754.44  5718.7  756.41  5725.4  755.04  5732.9  754.99    6002  757.28
#Mann= 3 ,-1 , 0
  4604.8     .05       0  5026.4    .033       0  5030.4     .05       0
Bank Sta=5026.4,5030.4
XS Rating Curve= 0 ,0
Exp/Cntr=0.3,0.1

Chan Stop Cuts=-1
Use User Specified Reach Order=0
Composite Channel Slope=5