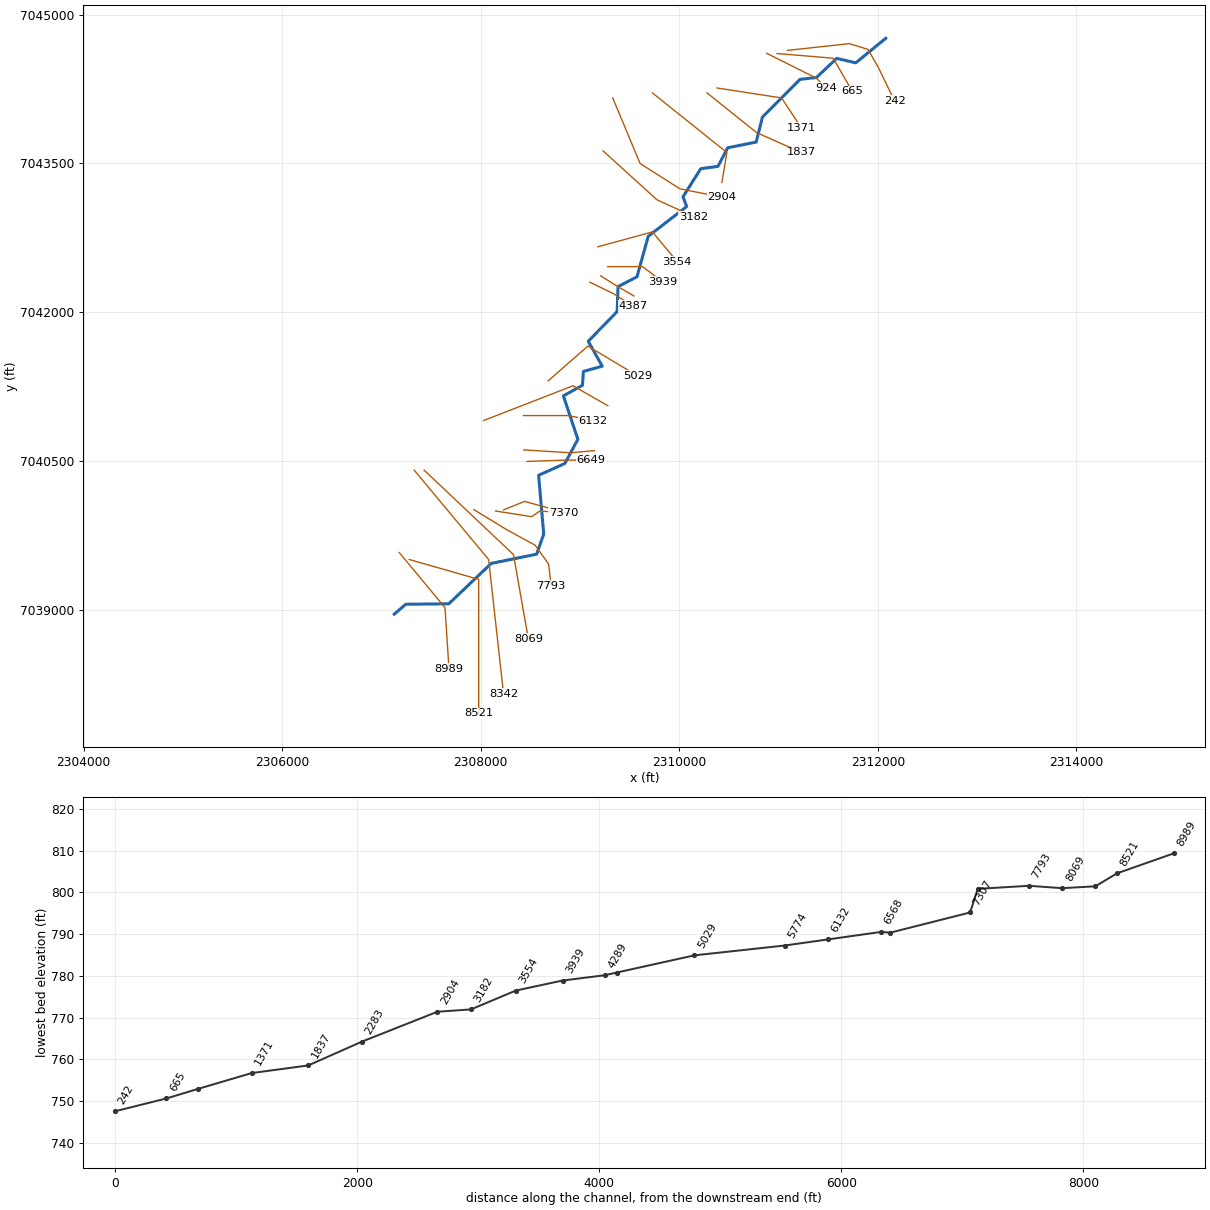
--- Henrietta Creek 6.prj (project) ---

Proj Title=Henrietta Creek 6 Base Level Engineering
Current Plan=p01
Default Exp/Contr=0.3,0.1
English Units
Geom File=g01
Flow File=f01
Plan File=p01
BEGIN DESCRIPTION:
Henrietta Creek 6
END DESCRIPTION:

--- Henrietta Creek 6.p01 (plan) ---

Plan Title=Multiple Run
Short Identifier=Multiple
Geom File=g01
Flow File=f01
Subcritical Flow
K Sum by GR= 0
Std Step Tol= 0.01
Critical Tol= 0.01
Num of Std Step Trials= 20
Max Error Tol= 0.3
Flow Tol Ratio= 0.001
Split Flow NTrial= 30
Split Flow Tol= 0.02
Split Flow Ratio= 0.02
Log Output Level= 0
Friction Slope Method= 1
Unsteady Friction Slope Method= 2
Unsteady Bridges Friction Slope Method= 1
Parabolic Critical Depth
Global Vel Dist=  1 , 1 , 1
Global Log Level= 0
CheckData=True
Encroach Param= -1, 0, 0, 0
BEGIN DESCRIPTION:
Multiple Run
END DESCRIPTION:

--- Henrietta Creek 6.f01 (steady flow) ---

Flow Title=Multiple
Number of Profiles=7
Profile Names=10-year,25-year,50-year,1pct_min,100-year,1pct_plu,500-year
River Rch & RM= Henrietta Creek ,Reach-1,8989
     375     493     586     346     690    1380     955
River Rch & RM= Henrietta Creek ,Reach-1,7793
     608     825    1000     601    1200    2390    1720
River Rch & RM= Henrietta Creek ,Reach-1,2283
     991    1380    1710    1050    2090    4170    3120
Boundary for River Rch & Prof#=Henrietta Creek ,Reach-1,1
Up Type=0
Dn Type=3
Dn Slope=0.005
Boundary for River Rch & Prof#=Henrietta Creek ,Reach-1,2
Up Type=0
Dn Type=3
Dn Slope=0.005
Boundary for River Rch & Prof#=Henrietta Creek ,Reach-1,3
Up Type=0
Dn Type=3
Dn Slope=0.005
Boundary for River Rch & Prof#=Henrietta Creek ,Reach-1,4
Up Type=0
Dn Type=3
Dn Slope=0.005
Boundary for River Rch & Prof#=Henrietta Creek ,Reach-1,5
Up Type=0
Dn Type=3
Dn Slope=0.005
Boundary for River Rch & Prof#=Henrietta Creek ,Reach-1,6
Up Type=0
Dn Type=3
Dn Slope=0.005
Boundary for River Rch & Prof#=Henrietta Creek ,Reach-1,7
Up Type=0
Dn Type=3
Dn Slope=0.005

--- Henrietta Creek 6.g01 (geometry) ---

Geom Title=Existing Conditions

River Reach=Henrietta Creek ,Reach-1
Reach XY= 30
      2307129.00      7038960.00      2307244.82      7039059.34
      2307677.53      7039063.55      2308105.37      7039470.88
      2308562.53      7039563.31      2308633.98      7039765.80
      2308582.53      7040358.55      2308846.14      7040476.28
      2308977.92      7040720.55      2308832.12      7041158.38
      2309023.96      7041265.09      2309034.01      7041404.98
      2309223.75      7041457.35      2309082.44      7041708.43
      2309373.55      7042007.53      2309382.44      7042258.78
      2309573.29      7042357.42      2309686.88      7042766.17
      2310074.20      7043065.62      2310037.08      7043163.28
      2310215.64      7043446.72      2310389.12      7043470.35
      2310487.28      7043656.94      2310773.82      7043715.41
      2310837.02      7043966.34      2311215.33      7044346.77
      2311381.45      7044365.47      2311584.89      7044558.04
      2311777.38      7044513.12      2312079.00      7044760.00

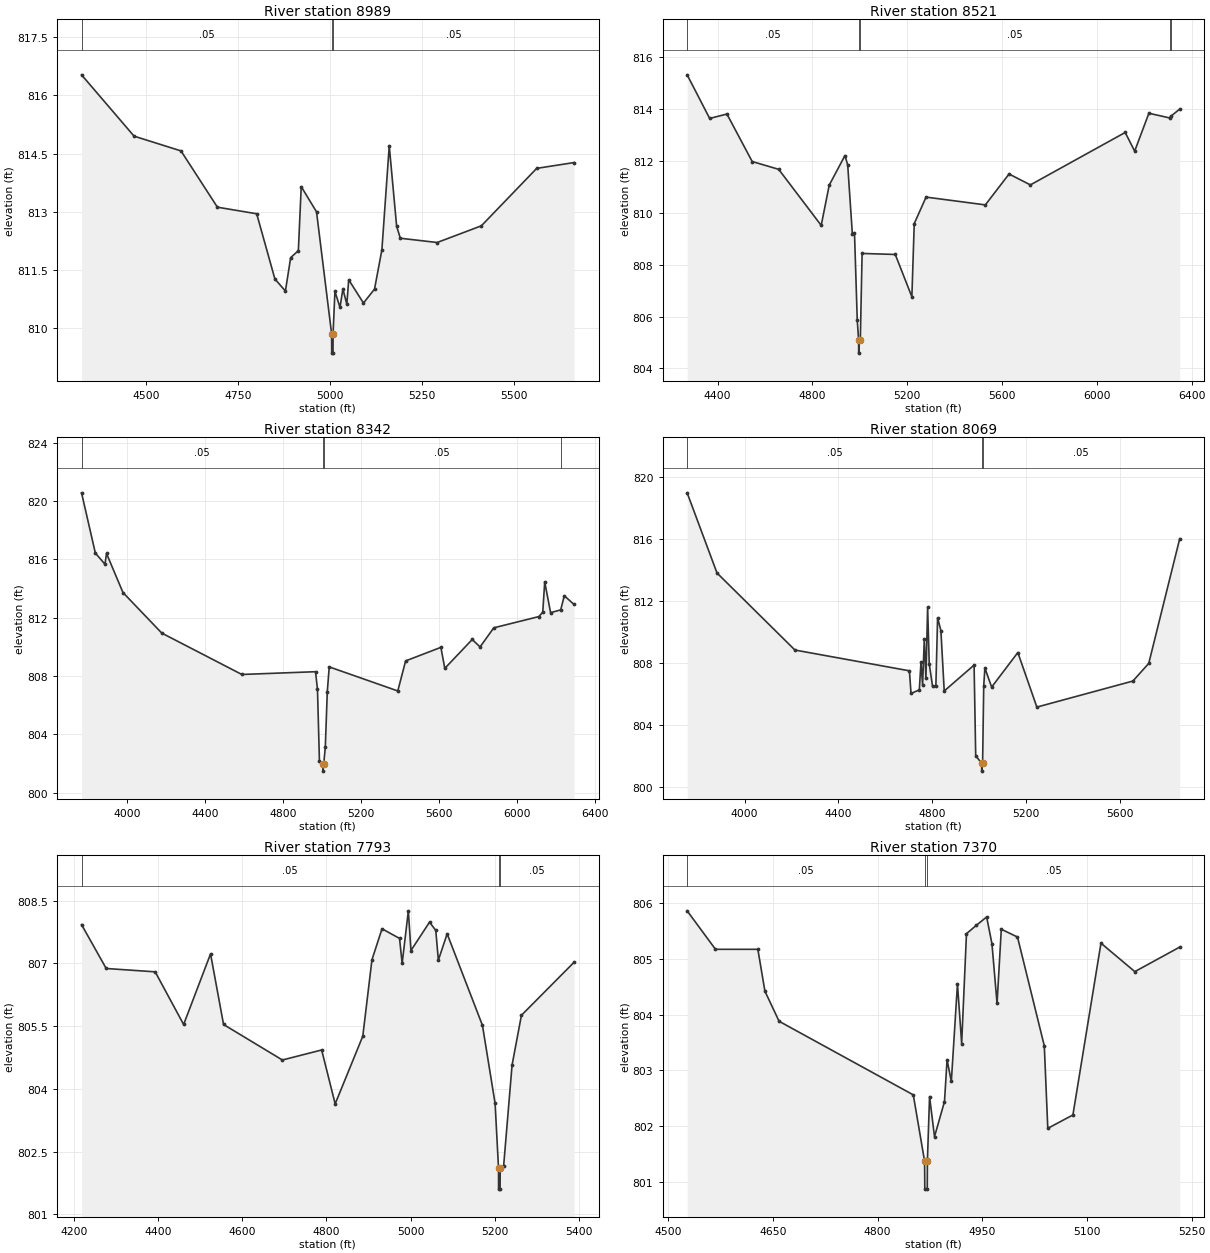
Type RM Length L Ch R = 1,8989,468,468,468
BEGIN DESCRIPTION:
Henrietta Creek 6 21.0
END DESCRIPTION:
XS GIS Cut Line= 3
      2307178.78      7039580.10      2307639.46      7039025.11
      2307679.36      7038408.47
#Sta/Elev= 30
  4323.7  816.53  4466.5  814.95  4594.1  814.57  4693.1  813.12  4799.9  812.95
  4849.4  811.27  4878.0  810.96  4892.3  811.82  4913.2  812.00  4921.0  813.65
  4962.6  813.00  5003.6  809.86  5003.9  809.36  5007.4  809.36  5007.6  809.86
  5012.6  810.95  5026.4  810.54  5034.3  811.01  5045.0  810.62  5050.1  811.25
  5090.2  810.65  5120.3  811.01  5140.3  812.02  5160.3  814.70  5180.4  812.63
  5190.4  812.32  5290.6  812.21  5410.8  812.64  5561.2  814.12  5662.9  814.27
#Mann=3,-1,0
  4323.7    0.05       0  5003.6   0.033       0  5007.6    0.05       0
Bank Sta=5003.6,5007.6
Exp/Cntr=0.3,0.1

Type RM Length L Ch R = 1,8521,179,179,179
BEGIN DESCRIPTION:
Henrietta Creek 6 20.0
END DESCRIPTION:
XS GIS Cut Line= 3
      2307278.95      7039510.01      2307979.00      7039310.00
      2307979.00      7037959.96
#Sta/Elev= 30
  4271.6  815.31  4366.6  813.63  4439.4  813.80  4546.0  811.97  4657.8  811.67
  4837.2  809.51  4871.0  811.06  4937.3  812.20  4949.0  811.84  4968.5  809.19
  4977.6  809.23  4989.3  805.86  4995.1  805.09  4995.3  804.59  4999.1  805.09
  5002.2  805.09  5009.7  808.43  5149.7  808.39  5219.7  806.76  5229.7  809.58
  5279.7  810.60  5529.7  810.30  5629.7  811.49  5719.7  811.07  6119.7  813.09
  6159.7  812.37  6219.7  813.83  6307.1  813.65  6311.6  813.71  6349.7  813.99
#Mann=5,-1,0
  4271.6    0.05       0  4995.1   0.033       0  4999.1    0.05       0
  6307.1   0.075       0  6311.6    0.05       0
Bank Sta=4995.1,4999.1
Exp/Cntr=0.3,0.1

Type RM Length L Ch R = 1,8342,273,273,273
BEGIN DESCRIPTION:
Henrietta Creek 6 19.0
END DESCRIPTION:
XS GIS Cut Line= 3
      2307329.01      7040409.98      2308079.00      7039510.00
      2308229.00      7038160.03
#Sta/Elev= 30
  3765.0  820.57  3835.9  816.44  3885.4  815.67  3893.2  816.41  3977.8  813.73
  4177.0  810.95  4588.3  808.11  4966.7  808.30  4976.8  807.10  4986.8  802.20
  5004.9  801.98  5005.2  801.48  5008.9  801.98  5017.0  803.12  5027.1  806.91
  5037.1  808.63  5389.3  806.98  5429.5  809.04  5610.6  809.97  5630.8  808.53
  5771.6  810.51  5811.9  810.00  5882.3  811.31  6113.7  812.08  6133.8  812.38
  6143.9  814.46  6174.1  812.35  6225.9  812.54  6244.5  813.51  6294.8  812.91
#Mann=4,-1,0
  3765.0    0.05       0  5004.9   0.033       0  5008.9    0.05       0
  6225.9   0.075       0
Bank Sta=5004.9,5008.9
Exp/Cntr=0.3,0.1

Type RM Length L Ch R = 1,8069,276,276,276
BEGIN DESCRIPTION:
Henrietta Creek 6 18.0
END DESCRIPTION:
XS GIS Cut Line= 3
      2307428.97      7040410.03      2308329.00      7039560.00
      2308479.00      7038710.01
#Sta/Elev= 30
  3754.6  818.98  3881.9  813.81  4214.4  808.84  4702.7  807.50  4709.6  806.04
  4745.0  806.27  4752.1  808.07  4758.9  806.59  4766.2  809.57  4773.1  807.01
  4780.4  811.59  4787.3  807.95  4801.4  806.49  4815.6  806.53  4822.9  810.92
  4837.0  810.10  4851.2  806.20  4978.6  807.87  4985.5  802.03  5010.9  801.53
  5011.1  801.03  5014.9  801.53  5019.7  806.53  5024.7  807.68  5053.5  806.45
  5165.2  808.68  5246.4  805.16  5656.0  806.84  5723.7  807.98  5855.7  816.02
#Mann=3,-1,0
  3754.6    0.05       0  5010.9   0.033       0  5014.9    0.05       0
Bank Sta=5010.9,5014.9
Exp/Cntr=0.3,0.1

Type RM Length L Ch R = 1,7793,423,423,423
BEGIN DESCRIPTION:
Henrietta Creek 6 17.5
END DESCRIPTION:
XS GIS Cut Line= 5
      2307929.68      7040012.88      2308262.34      7039810.00
      2308547.65      7039653.93      2308683.07      7039463.83
      2308708.97      7039243.70
#Sta/Elev= 30
  4218.6  807.93  4277.2  806.88  4393.5  806.80  4461.1  805.54  4525.0  807.23
  4555.9  805.54  4695.6  804.69  4788.9  804.93  4821.0  803.64  4886.6  805.26
  4908.4  807.09  4932.3  807.83  4973.9  807.60  4980.1  807.00  4994.8  808.26
  5001.0  807.31  5045.2  807.99  5060.0  807.79  5066.1  807.08  5087.0  807.71
  5170.8  805.52  5200.9  803.65  5209.0  802.10  5209.2  801.60  5212.7  801.60
  5213.0  802.10  5221.1  802.15  5241.2  804.57  5263.4  805.76  5388.5  807.03
#Mann=3,-1,0
  4218.6    0.05       0  5209.0    0.05       0  5213.0    0.05       0
Bank Sta=5209,5213
Exp/Cntr=0.3,0.1

Type RM Length L Ch R = 1,7370,63,63,63
BEGIN DESCRIPTION:
Henrietta Creek 6 17.0
END DESCRIPTION:
XS GIS Cut Line= 4
      2308148.93      7039998.62      2308513.14      7039941.35
      2308595.59      7039998.62      2308831.51      7039980.29
#Sta/Elev= 30
  4527.2  805.86  4567.8  805.17  4628.5  805.17  4638.6  804.42  4658.9  803.88
  4851.2  802.56  4867.4  801.37  4867.7  800.87  4871.2  800.87  4871.4  801.37
  4874.5  802.53  4881.6  801.81  4895.9  802.44  4899.6  803.19  4905.7  802.80
  4914.5  804.55  4920.5  803.48  4927.4  805.45  4941.5  805.60  4956.3  805.75
  4963.9  805.27  4971.2  804.20  4977.3  805.53  5000.5  805.39  5038.9  803.44
  5043.9  801.96  5079.9  802.20  5120.1  805.28  5168.6  804.77  5232.9  805.21
#Mann=3,-1,0
  4527.2    0.05       0  4867.4   0.033       0  4871.4    0.05       0
Bank Sta=4867.4,4871.4
Exp/Cntr=0.3,0.1

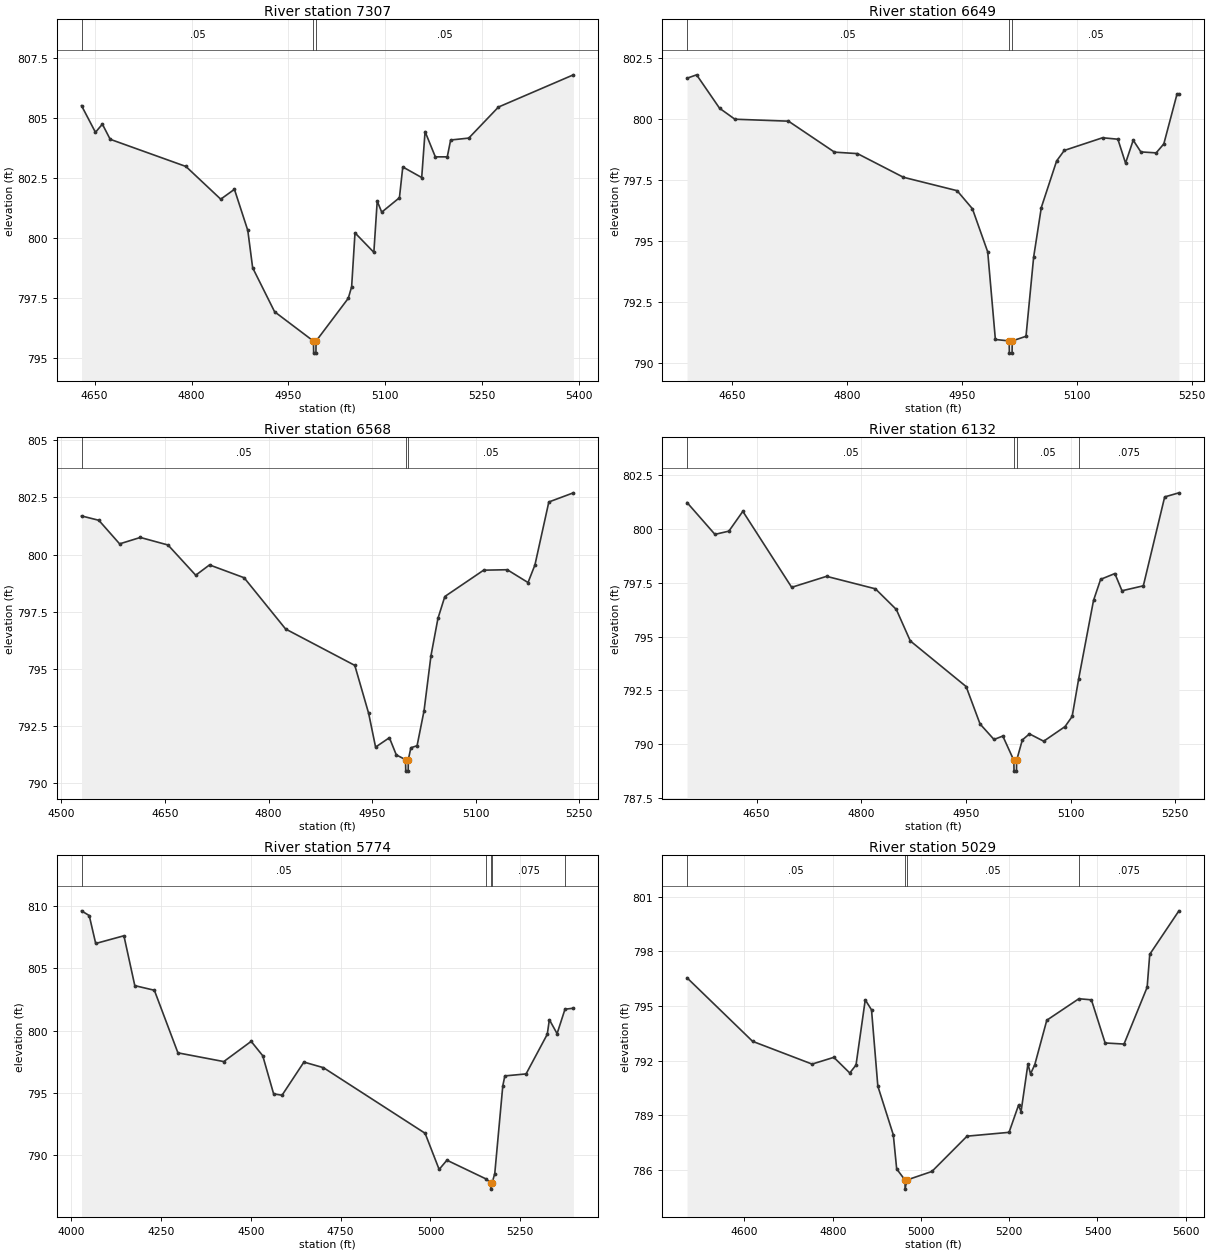
Type RM Length L Ch R = 1,7307,658,658,658
BEGIN DESCRIPTION:
Henrietta Creek 6 16.0
END DESCRIPTION:
XS GIS Cut Line= 3
      2308228.99      7040010.00      2308441.14      7040095.24
      2308955.17      7039954.06
#Sta/Elev= 30
  4629.6  805.50  4651.2  804.39  4661.9  804.73  4674.0  804.10  4791.3  802.97
  4845.2  801.61  4866.4  802.02  4887.1  800.31  4894.6  798.76  4928.6  796.93
  4988.8  795.71  4989.1  795.21  4992.6  795.21  4992.8  795.71  5042.7  797.49
  5047.9  797.97  5053.1  800.21  5082.3  799.40  5087.5  801.53  5094.5  801.07
  5121.9  801.67  5127.1  802.95  5156.4  802.51  5161.6  804.42  5177.5  803.37
  5196.0  803.37  5201.2  804.07  5229.3  804.15  5275.2  805.44  5391.3  806.78
#Mann=3,-1,0
  4629.6    0.05       0  4988.8   0.033       0  4992.8    0.05       0
Bank Sta=4988.8,4992.8
Exp/Cntr=0.3,0.1

Type RM Length L Ch R = 1,6649,81,81,81
BEGIN DESCRIPTION:
Henrietta Creek 6 15.0
END DESCRIPTION:
XS GIS Cut Line= 3
      2308466.54      7040497.89      2308883.70      7040512.40
      2309108.65      7040508.77
#Sta/Elev= 30
  4590.9  801.66  4603.4  801.80  4633.4  800.43  4653.4  799.98  4723.4  799.90
  4783.5  798.63  4813.5  798.57  4873.5  797.60  4943.6  797.05  4963.6  796.31
  4983.6  794.54  4993.6  790.95  5011.6  790.89  5011.9  790.39  5015.4  790.39
  5015.6  790.89  5033.6  791.08  5043.6  794.33  5053.6  796.36  5073.6  798.27
  5083.6  798.70  5133.6  799.22  5153.6  799.16  5163.6  798.18  5173.6  799.12
  5183.6  798.64  5203.6  798.60  5213.6  798.97  5230.9  801.02  5233.3  801.02
#Mann=3,-1,0
  4590.9    0.05       0  5011.6   0.033       0  5015.6    0.05       0
Bank Sta=5011.6,5015.6
Exp/Cntr=0.3,0.1

Type RM Length L Ch R = 1,6568,436,436,436
BEGIN DESCRIPTION:
Henrietta Creek 6 14.0
END DESCRIPTION:
XS GIS Cut Line= 3
      2308433.91      7040613.97      2308905.46      7040584.95
      2309144.43      7040606.68
#Sta/Elev= 30
  4529.0  801.69  4554.1  801.50  4584.2  800.47  4614.2  800.75  4654.3  800.42
  4694.4  799.10  4714.4  799.55  4764.5  798.99  4824.6  796.75  4924.8  795.16
  4944.9  793.06  4954.9  791.59  4974.9  792.00  4984.9  791.25  4998.3  791.04
  4998.6  790.54  5002.1  790.54  5002.3  791.04  5006.0  791.56  5015.0  791.65
  5025.1  793.18  5035.1  795.58  5045.2  797.21  5055.2  798.17  5111.4  799.32
  5145.6  799.34  5175.7  798.78  5185.7  799.55  5205.8  802.30  5241.4  802.70
#Mann=3,-1,0
  4529.0    0.05       0  4998.3    0.05       0  5002.3    0.05       0
Bank Sta=4998.3,5002.3
Exp/Cntr=0.3,0.1

Type RM Length L Ch R = 1,6132,358,358,358
BEGIN DESCRIPTION:
Henrietta Creek 6 13.0
END DESCRIPTION:
XS GIS Cut Line= 3
      2308428.95      7040960.00      2308879.00      7040960.00
      2309129.00      7040910.00
#Sta/Elev= 30
  4550.3  801.23  4590.3  799.75  4610.3  799.90  4630.3  800.82  4700.3  797.29
  4750.3  797.80  4820.3  797.22  4850.3  796.26  4870.3  794.80  4950.3  792.68
  4970.3  790.94  4990.3  790.22  5002.9  790.38  5018.7  789.25  5019.0  788.75
  5022.5  788.75  5022.7  789.25  5030.9  790.20  5041.1  790.48  5061.5  790.14
  5092.1  790.82  5102.3  791.29  5111.7  793.05  5132.9  796.68  5143.1  797.66
  5163.5  797.93  5173.7  797.13  5204.3  797.36  5234.9  801.49  5255.3  801.68
#Mann=4,-1,0
  4550.3    0.05       0  5018.7   0.033       0  5022.7    0.05       0
  5111.7   0.075       0
Bank Sta=5018.7,5022.7
Exp/Cntr=0.3,0.1

Type RM Length L Ch R = 1,5774,745,745,745
BEGIN DESCRIPTION:
Henrietta Creek 6 12.0
END DESCRIPTION:
XS GIS Cut Line= 3
      2308028.98      7040909.99      2308929.00      7041260.00
      2309279.00      7041060.00
#Sta/Elev= 30
  4029.0  809.61  4050.5  809.23  4068.5  806.99  4147.0  807.61  4177.3  803.61
  4231.7  803.24  4297.3  798.22  4424.9  797.52  4501.1  799.14  4533.3  797.99
  4563.6  794.93  4587.0  794.82  4647.9  797.48  4702.3  797.03  4985.1  791.77
  5024.2  788.87  5045.8  789.61  5155.2  788.10  5167.6  787.79  5167.9  787.29
  5171.6  787.79  5179.0  788.54  5201.3  795.57  5207.0  796.37  5266.1  796.53
  5325.1  799.71  5330.9  800.88  5352.4  799.76  5374.4  801.72  5397.8  801.80
#Mann=5,-1,0
  4029.0    0.05       0  5155.2   0.075       0  5167.6   0.033       0
  5171.6   0.075       0  5374.4     0.1       0
Bank Sta=5167.6,5171.6
Exp/Cntr=0.3,0.1

Type RM Length L Ch R = 1,5029,642,642,642
BEGIN DESCRIPTION:
Henrietta Creek 6 11.0
END DESCRIPTION:
XS GIS Cut Line= 3
      2308678.96      7041309.97      2309079.00      7041660.00
      2309579.04      7041359.97
#Sta/Elev= 30
  4469.8  796.55  4618.4  793.06  4753.2  791.81  4802.5  792.18  4838.6  791.32
  4852.8  791.76  4873.7  795.34  4887.9  794.79  4902.2  790.60  4937.3  787.92
  4944.9  786.05  4963.8  785.44  4964.0  784.94  4967.8  785.44  5024.7  785.91
  5104.4  787.85  5199.6  788.06  5221.0  789.55  5226.8  789.20  5242.4  791.82
  5248.2  791.27  5257.9  791.78  5285.1  794.22  5357.8  795.40  5386.2  795.34
  5417.3  792.97  5460.1  792.91  5512.5  796.03  5518.4  797.84  5584.5  800.23
#Mann=4,-1,0
  4469.8    0.05       0  4963.8   0.033       0  4967.8    0.05       0
  5357.8   0.075       0
Bank Sta=4963.8,4967.8
Exp/Cntr=0.3,0.1

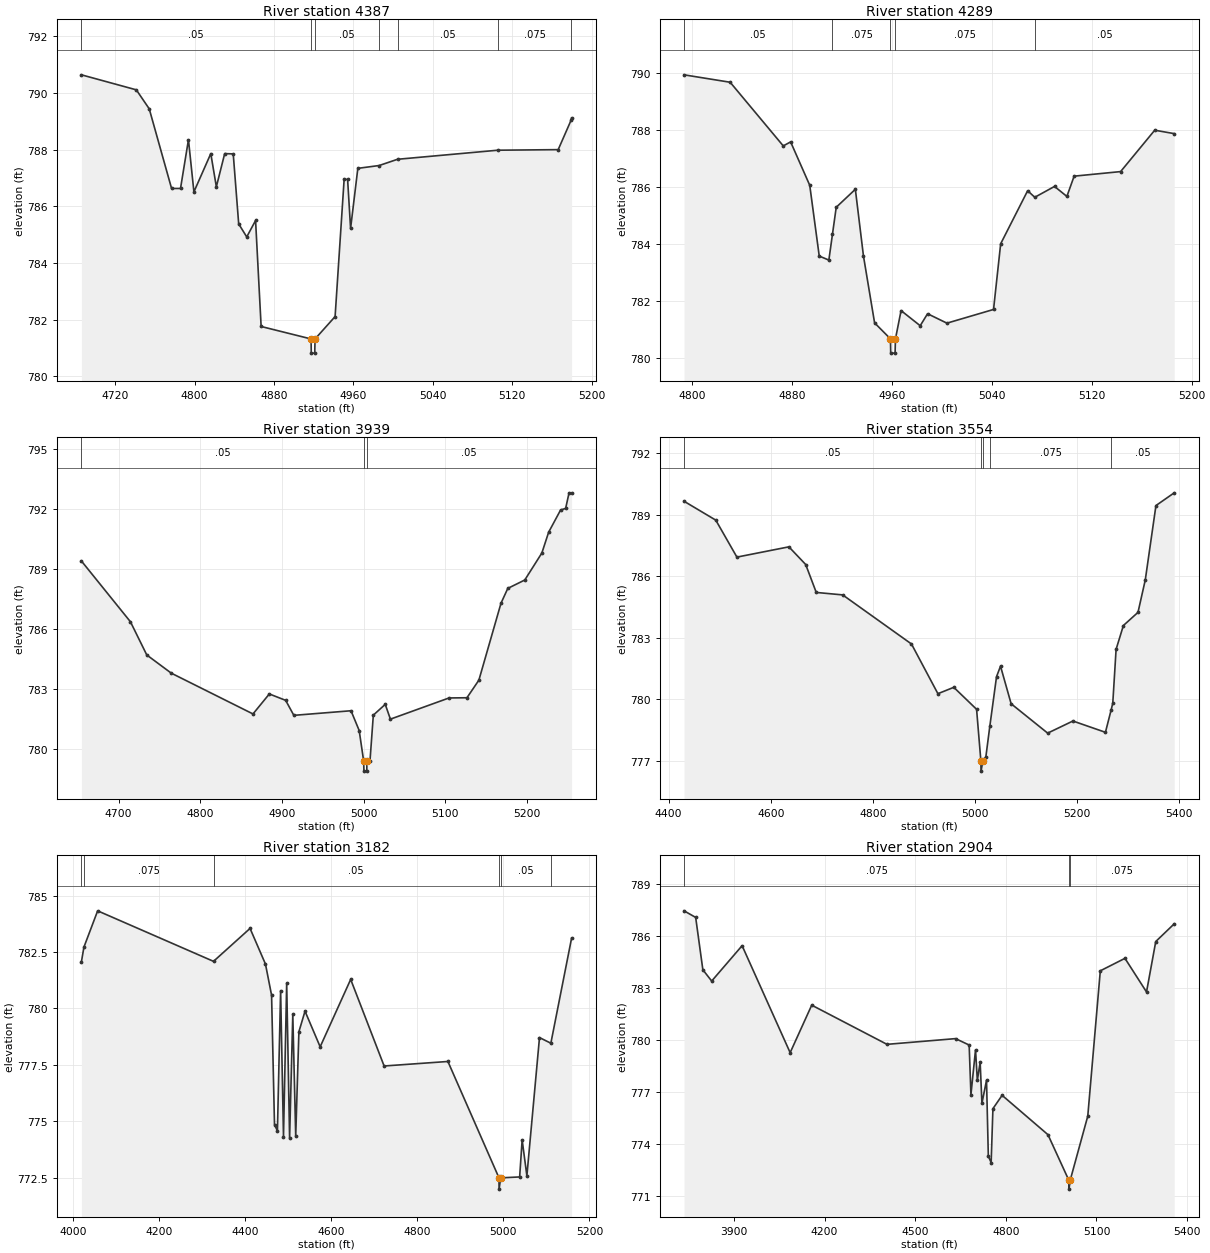
Type RM Length L Ch R = 1,4387,98,98,98
BEGIN DESCRIPTION:
Henrietta Creek 6 10.0
END DESCRIPTION:
XS GIS Cut Line= 3
      2309099.29      7042303.26      2309340.35      7042185.86
      2309530.40      7042064.36
#Sta/Elev= 30
  4686.1  790.64  4741.4  790.11  4754.4  789.44  4776.9  786.63  4785.9  786.63
  4793.9  788.35  4799.4  786.51  4816.4  787.86  4822.0  786.69  4830.4  787.86
  4839.0  787.85  4844.5  785.38  4852.6  784.92  4861.5  785.50  4867.1  781.76
  4917.4  781.32  4917.6  780.82  4921.1  780.82  4921.4  781.32  4941.6  782.11
  4950.7  786.95  4954.2  786.95  4957.2  785.22  4964.5  787.34  4986.0  787.44
  5004.5  787.66  5105.5  787.98  5166.3  788.00  5179.3  789.04  5179.8  789.12
#Mann=7,-1,0
  4686.1    0.05       0  4917.4    0.07       0  4921.4    0.05       0
  4986.0   0.075       0  5004.5    0.05       0  5105.5   0.075       0
  5179.3    0.05       0
Bank Sta=4917.4,4921.4
Exp/Cntr=0.3,0.1

Type RM Length L Ch R = 1,4289,350,350,350
BEGIN DESCRIPTION:
Henrietta Creek 6 9.0
END DESCRIPTION:
XS GIS Cut Line= 3
      2309207.28      7042367.47      2309379.00      7042260.00
      2309542.93      7042164.49
#Sta/Elev= 30
  4793.7  789.93  4830.6  789.67  4873.1  787.44  4879.0  787.58  4894.3  786.06
  4901.9  783.58  4909.6  783.44  4912.5  784.35  4915.5  785.29  4930.8  785.92
  4937.3  783.58  4946.2  781.24  4958.9  780.68  4959.1  780.18  4962.6  780.18
  4962.9  780.68  4967.4  781.67  4982.7  781.14  4988.6  781.56  5004.1  781.23
  5041.4  781.71  5047.1  784.01  5068.7  785.87  5074.4  785.64  5090.2  786.02
  5100.1  785.67  5105.9  786.38  5143.1  786.54  5170.4  787.99  5186.0  787.87
#Mann=5,-1,0
  4793.7    0.05       0  4912.5   0.075       0  4958.9    0.07       0
  4962.9   0.075       0  5074.4    0.05       0
Bank Sta=4958.9,4962.9
Exp/Cntr=0.3,0.1

Type RM Length L Ch R = 1,3939,385,385,385
BEGIN DESCRIPTION:
Henrietta Creek 6 8.0
END DESCRIPTION:
XS GIS Cut Line= 3
      2309278.96      7042460.00      2309629.00      7042460.00
      2309828.97      7042310.02
#Sta/Elev= 30
  4654.5  789.41  4714.5  786.37  4734.5  784.71  4764.5  783.80  4864.5  781.76
  4884.5  782.76  4904.5  782.44  4914.5  781.69  4984.5  781.92  4994.5  780.93
  5000.0  779.40  5000.3  778.90  5003.8  778.90  5004.0  779.40  5007.7  779.40
  5011.8  781.70  5026.4  782.24  5032.7  781.50  5104.5  782.56  5126.4  782.57
  5141.0  783.45  5168.1  787.30  5176.4  788.04  5197.2  788.46  5218.1  789.81
  5226.4  790.85  5241.0  791.96  5247.2  792.04  5251.4  792.82  5254.5  792.82
#Mann=3,-1,0
  4654.5    0.05       0  5000.0    0.05       0  5004.0    0.05       0
Bank Sta=5000,5004
Exp/Cntr=0.3,0.1

Type RM Length L Ch R = 1,3554,372,372,372
BEGIN DESCRIPTION:
Henrietta Creek 6 7.0
END DESCRIPTION:
XS GIS Cut Line= 3
      2309179.03      7042660.01      2309729.00      7042810.00
      2309979.02      7042509.98
#Sta/Elev= 30
  4430.1  789.65  4492.3  788.73  4533.7  786.93  4635.6  787.43  4668.5  786.57
  4689.2  785.21  4741.0  785.09  4875.8  782.70  4927.6  780.28  4958.7  780.59
  5003.4  779.52  5011.8  777.01  5012.1  776.51  5015.8  777.01  5021.6  777.21
  5029.3  778.69  5042.5  781.11  5050.3  781.62  5071.1  779.79  5142.7  778.36
  5192.2  778.95  5255.9  778.40  5267.0  779.48  5270.3  779.82  5276.8  782.44
  5291.1  783.60  5319.7  784.24  5334.0  785.82  5354.9  789.44  5390.7  790.06
#Mann=5,-1,0
  4430.1    0.05       0  5011.8    0.05       0  5015.8    0.05       0
  5029.3   0.075       0  5267.0    0.05       0
Bank Sta=5011.8,5015.8
Exp/Cntr=0.3,0.1

Type RM Length L Ch R = 1,3182,278,278,278
BEGIN DESCRIPTION:
Henrietta Creek 6 6.0
END DESCRIPTION:
XS GIS Cut Line= 3
      2309231.82      7043626.46      2309775.53      7043132.80
      2310143.48      7042964.73
#Sta/Elev= 30
  4019.6  782.07  4025.4  782.72  4057.3  784.33  4326.5  782.09  4411.4  783.55
  4447.2  781.97  4461.4  780.59  4468.2  774.85  4475.0  774.57  4482.4  780.79
  4489.1  774.32  4496.5  781.11  4503.3  774.25  4510.7  779.74  4517.5  774.34
  4524.9  778.97  4539.1  779.88  4574.3  778.30  4645.2  781.29  4722.9  777.45
  4871.1  777.65  4989.8  772.49  4990.0  771.99  4993.8  772.49  5037.8  772.53
  5043.6  774.17  5054.6  772.58  5083.9  778.71  5110.3  778.46  5158.5  783.12
#Mann=6,-1,0
  4019.6     0.1       0  4025.4   0.075       0  4326.5    0.05       0
  4989.8    0.05       0  4993.8    0.05       0  5110.3   0.075       0
Bank Sta=4989.8,4993.8
Exp/Cntr=0.3,0.1

Type RM Length L Ch R = 1,2904,621,621,621
BEGIN DESCRIPTION:
Henrietta Creek 6 5.0
END DESCRIPTION:
XS GIS Cut Line= 4
      2309328.98      7044160.04      2309604.92      7043499.05
      2310005.29      7043244.27      2310428.96      7043160.01
#Sta/Elev= 30
  3734.6  787.47  3773.1  787.09  3796.9  784.07  3826.1  783.42  3926.8  785.46
  4085.9  779.29  4157.3  782.03  4406.5  779.77  4633.5  780.10  4678.5  779.73
  4684.4  776.87  4699.6  779.45  4705.6  777.69  4714.9  778.74  4720.8  776.37
  4736.0  777.70  4742.0  773.32  4751.3  772.95  4757.2  776.06  4787.6  776.83
  4939.4  774.56  5008.8  771.92  5009.0  771.42  5012.8  771.92  5071.2  775.63
  5112.7  784.01  5194.3  784.73  5265.7  782.79  5296.3  785.70  5357.4  786.72
#Mann=3,-1,0
  3734.6   0.075       0  5008.8    0.07       0  5012.8   0.075       0
Bank Sta=5008.8,5012.8
Exp/Cntr=0.3,0.1

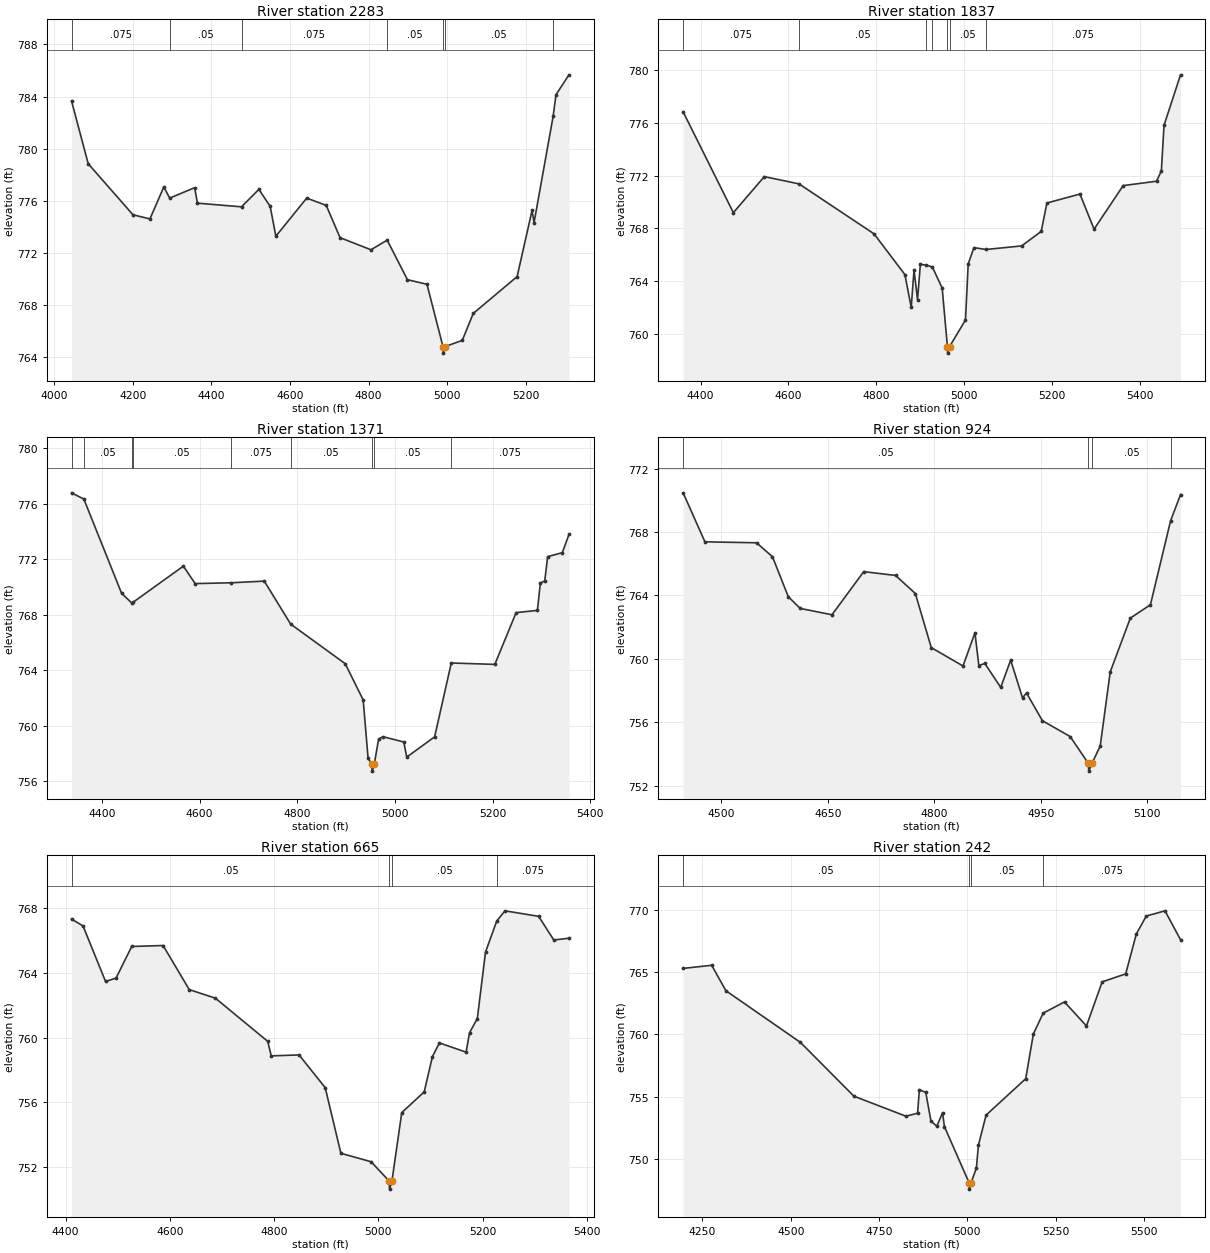
Type RM Length L Ch R = 1,2283,446,446,446
BEGIN DESCRIPTION:
Henrietta Creek 6 4.0
END DESCRIPTION:
XS GIS Cut Line= 3
      2309729.01      7044209.99      2310479.00      7043610.00
      2310429.00      7043309.99
#Sta/Elev= 30
  4044.7  783.66  4087.1  778.84  4200.8  774.92  4244.0  774.60  4279.2  777.05
  4294.3  776.20  4357.6  777.00  4364.8  775.81  4476.8  775.53  4520.9  776.87
  4549.7  775.57  4564.1  773.27  4642.6  776.20  4692.2  775.64  4727.4  773.16
  4805.9  772.23  4847.2  772.97  4898.7  769.93  4948.3  769.58  4989.0  764.79
  4989.7  764.29  4994.0  764.79  5038.1  765.27  5066.0  767.34  5177.5  770.17
  5215.5  775.25  5220.6  774.32  5269.0  782.47  5276.3  784.14  5309.3  785.67
#Mann=7,-1,0
  4044.7   0.075       0  4294.3    0.05       0  4476.8   0.075       0
  4847.2    0.05       0  4989.0    0.05       0  4994.0    0.05       0
  5269.0   0.075       0
Bank Sta=4989,4994
Exp/Cntr=0.3,0.1

Type RM Length L Ch R = 1,1837,466,466,466
BEGIN DESCRIPTION:
Henrietta Creek 6 3.0
END DESCRIPTION:
XS GIS Cut Line= 3
      2310279.02      7044209.99      2310779.00      7043810.00
      2311228.97      7043610.01
#Sta/Elev= 30
  4360.1  776.84  4474.5  769.20  4545.0  771.93  4624.0  771.38  4794.7  767.60
  4865.1  764.51  4879.5  762.03  4885.9  764.86  4893.9  762.61  4900.3  765.28
  4913.2  765.23  4927.7  765.08  4950.0  763.49  4961.9  759.06  4962.5  758.56
  4966.9  759.06  5003.1  761.07  5009.3  765.32  5022.3  766.55  5049.7  766.41
  5131.0  766.68  5175.5  767.78  5188.5  769.93  5263.7  770.61  5295.9  767.95
  5362.2  771.25  5438.1  771.58  5449.1  772.36  5455.2  775.82  5492.8  779.64
#Mann=7,-1,0
  4360.1   0.075       0  4624.0    0.05       0  4913.2   0.075       0
  4927.7    0.05       0  4961.9    0.05       0  4966.9    0.05       0
  5049.7   0.075       0
Bank Sta=4961.9,4966.9
Exp/Cntr=0.3,0.1

Type RM Length L Ch R = 1,1371,447,447,447
BEGIN DESCRIPTION:
Henrietta Creek 6 2.0
END DESCRIPTION:
XS GIS Cut Line= 3
      2310378.95      7044260.01      2311029.00      7044160.00
      2311229.03      7043859.96
#Sta/Elev= 30
  4338.0  776.79  4363.2  776.34  4440.5  769.55  4461.7  768.84  4463.8  768.90
  4567.0  771.51  4591.0  770.25  4665.0  770.31  4732.6  770.43  4786.6  767.33
  4898.3  764.48  4935.0  761.87  4945.1  757.66  4952.7  757.24  4953.4  756.74
  4957.7  757.24  4966.6  759.04  4975.5  759.22  5018.2  758.84  5024.2  757.75
  5081.3  759.21  5115.4  764.53  5204.5  764.43  5248.1  768.16  5291.7  768.32
  5297.7  770.28  5306.7  770.44  5312.7  772.19  5342.7  772.48  5356.3  773.79
#Mann=9,-1,0
  4338.0   0.075       0  4363.2    0.05       0  4461.7   0.075       0
  4463.8    0.05       0  4665.0   0.075       0  4786.6    0.05       0
  4952.7    0.05       0  4957.7    0.05       0  5115.4   0.075       0
Bank Sta=4952.7,4957.7
Exp/Cntr=0.3,0.1

Type RM Length L Ch R = 1,924,259,259,259
BEGIN DESCRIPTION:
Henrietta Creek 6 1.0
END DESCRIPTION:
XS GIS Cut Line= 3
      2310879.02      7044609.99      2311379.00      7044360.00
      2311478.99      7044260.01
#Sta/Elev= 30
  4446.4  770.47  4477.1  767.38  4549.8  767.32  4572.2  766.44  4594.5  763.92
  4611.3  763.18  4656.0  762.78  4700.7  765.50  4745.5  765.26  4773.4  764.12
  4795.8  760.71  4840.5  759.55  4857.3  761.64  4862.8  759.58  4871.2  759.71
  4893.6  758.20  4907.6  759.92  4924.3  757.54  4929.9  757.85  4952.3  756.10
  4991.4  755.10  5016.8  753.42  5017.6  752.92  5022.2  753.42  5033.7  754.50
  5047.8  759.18  5076.1  762.57  5104.4  763.41  5132.8  768.71  5146.8  770.36
#Mann=4,-1,0
  4446.4    0.05       0  5016.8    0.05       0  5022.2    0.05       0
  5132.8   0.075       0
Bank Sta=5016.8,5022.2
Exp/Cntr=0.3,0.1

Type RM Length L Ch R = 1,665,423,423,423
BEGIN DESCRIPTION:
Henrietta Creek 6 0.5
END DESCRIPTION:
XS GIS Cut Line= 3
      2310983.89      7044606.98      2311549.56      7044559.84
      2311743.24      7044224.82
#Sta/Elev= 30
  4411.3  767.31  4433.3  766.89  4476.6  763.46  4496.7  763.67  4526.8  765.62
  4587.0  765.68  4637.2  762.96  4687.4  762.43  4787.7  759.77  4794.6  758.87
  4847.9  758.93  4898.1  756.91  4928.2  752.86  4986.2  752.34  5020.8  751.15
  5021.6  750.65  5026.2  751.15  5045.0  755.37  5088.1  756.65  5103.9  758.83
  5117.4  759.67  5168.5  759.10  5175.1  760.30  5190.0  761.17  5205.8  765.28
  5227.3  767.19  5243.1  767.82  5307.7  767.48  5336.8  766.02  5365.9  766.13
#Mann=4,-1,0
  4411.3    0.05       0  5020.8   0.033       0  5026.2    0.05       0
  5227.3   0.075       0
Bank Sta=5020.8,5026.2
Exp/Cntr=0.3,0.1

Type RM Length L Ch R = 1,242,0,0,0
BEGIN DESCRIPTION:
Henrietta Creek 6 0.2
END DESCRIPTION:
XS GIS Cut Line= 5
      2311088.60      7044638.41      2311711.93      7044706.50
      2311900.49      7044648.88      2312005.25      7044465.56
      2312167.61      7044130.36
#Sta/Elev= 30
  4195.4  765.30  4276.3  765.55  4316.5  763.51  4527.6  759.36  4678.7  755.05
  4826.1  753.44  4858.9  753.68  4864.1  755.57  4882.1  755.35  4896.9  753.04
  4913.5  752.64  4929.7  753.72  4934.9  752.61  5004.9  748.09  5005.7  747.59
  5010.3  748.09  5025.4  749.28  5031.1  751.11  5052.9  753.53  5165.0  756.45
  5186.6  760.03  5214.4  761.71  5274.8  762.61  5336.9  760.68  5381.4  764.22
  5448.0  764.86  5478.0  768.06  5506.2  769.50  5559.2  769.92  5603.2  767.60
#Mann=4,-1,0
  4195.4    0.05       0  5004.9   0.033       0  5010.3    0.05       0
  5214.4   0.075       0
Bank Sta=5004.9,5010.3
Exp/Cntr=0.3,0.1

Chan Stop Cuts=-1