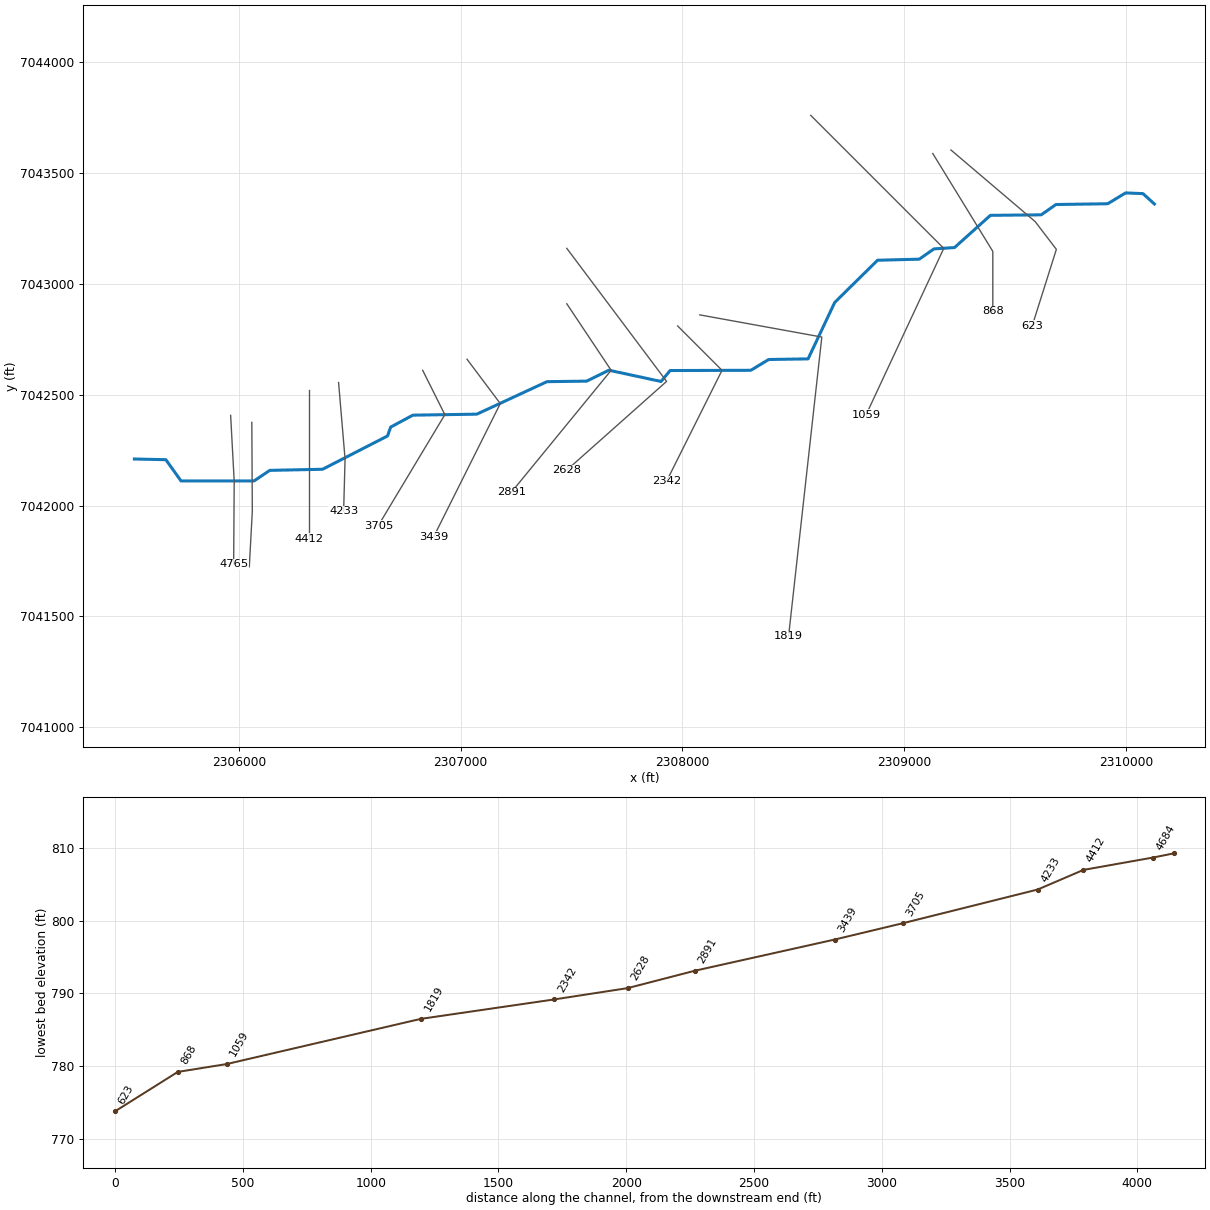
--- Henrietta Creek 6A.prj (project) ---

Proj Title=Henrietta Creek 6A Base Level Engineering
Current Plan=p01
Default Exp/Contr=0.3,0.1
English Units
Geom File=g01
Flow File=f01
Plan File=p01
BEGIN DESCRIPTION:
Henrietta Creek 6A
END DESCRIPTION:

--- Henrietta Creek 6A.p01 (plan) ---

Plan Title=Multiple Run
Short Identifier=Multiple
Geom File=g01
Flow File=f01
Subcritical Flow
K Sum by GR= 0
Std Step Tol= 0.01
Critical Tol= 0.01
Num of Std Step Trials= 20
Max Error Tol= 0.3
Flow Tol Ratio= 0.001
Split Flow NTrial= 30
Split Flow Tol= 0.02
Split Flow Ratio= 0.02
Log Output Level= 0
Friction Slope Method= 1
Unsteady Friction Slope Method= 2
Unsteady Bridges Friction Slope Method= 1
Parabolic Critical Depth
Global Vel Dist=  1 , 1 , 1
Global Log Level= 0
CheckData=True
Encroach Param= -1, 0, 0, 0
BEGIN DESCRIPTION:
Multiple Run
END DESCRIPTION:

--- Henrietta Creek 6A.f01 (steady flow) ---

Flow Title=Multiple
Number of Profiles=7
Profile Names=10-year,25-year,50-year,1pct_min,100-year,1pct_plu,500-year
River Rch & RM= Henrietta Creek ,Reach-1,4765
     422     562     675     402     802    1600    1130
Boundary for River Rch & Prof#=Henrietta Creek ,Reach-1,1
Up Type=0
Dn Type=3
Dn Slope=0.005
Boundary for River Rch & Prof#=Henrietta Creek ,Reach-1,2
Up Type=0
Dn Type=3
Dn Slope=0.005
Boundary for River Rch & Prof#=Henrietta Creek ,Reach-1,3
Up Type=0
Dn Type=3
Dn Slope=0.005
Boundary for River Rch & Prof#=Henrietta Creek ,Reach-1,4
Up Type=0
Dn Type=3
Dn Slope=0.005
Boundary for River Rch & Prof#=Henrietta Creek ,Reach-1,5
Up Type=0
Dn Type=3
Dn Slope=0.005
Boundary for River Rch & Prof#=Henrietta Creek ,Reach-1,6
Up Type=0
Dn Type=3
Dn Slope=0.005
Boundary for River Rch & Prof#=Henrietta Creek ,Reach-1,7
Up Type=0
Dn Type=3
Dn Slope=0.005

--- Henrietta Creek 6A.g01 (geometry) ---

Geom Title=Existing Conditions

River Reach=Henrietta Creek ,Reach-1
Reach XY= 30
      2305529.00      7042210.00      2305670.74      7042206.97
      2305739.29      7042111.01      2306068.50      7042111.22
      2306139.50      7042158.78      2306377.45      7042163.75
      2306670.38      7042313.84      2306684.76      7042354.05
      2306784.90      7042407.77      2307073.06      7042412.26
      2307389.50      7042558.80      2307568.49      7042561.22
      2307668.83      7042610.50      2307904.04      7042559.68
      2307944.96      7042609.04      2308308.97      7042610.07
      2308389.51      7042658.78      2308567.19      7042661.62
      2308687.14      7042916.06      2308880.46      7043106.46
      2309068.50      7043111.22      2309134.98      7043157.64
      2309227.50      7043163.61      2309389.43      7043308.95
      2309618.50      7043311.22      2309684.94      7043357.74
      2309918.50      7043361.22      2309999.08      7043410.11
      2310077.60      7043406.81      2310129.00      7043360.00

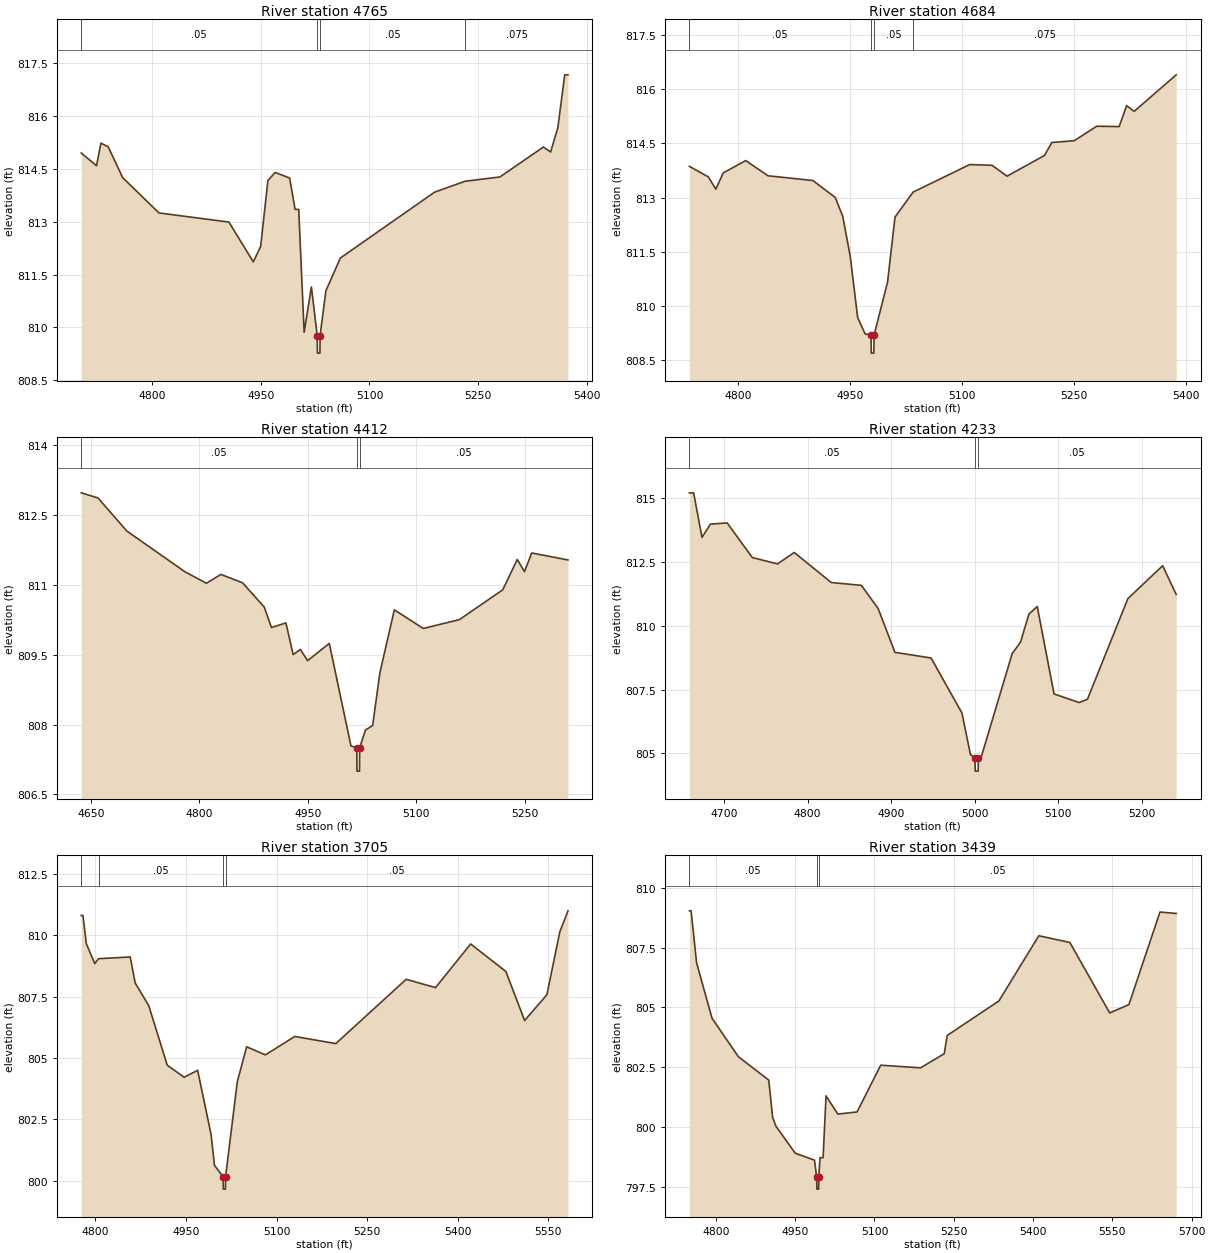
Type RM Length L Ch R = 1,4765,81,81,81
BEGIN DESCRIPTION:
Henrietta Creek 6A 10.0
END DESCRIPTION:
XS GIS Cut Line= 3
      2305962.91      7042407.09      2305979.00      7042110.00
      2305976.56      7041736.03
#Sta/Elev= 30
  4702.4  814.95  4723.5  814.59  4729.5  815.23  4739.5  815.13  4759.6  814.25
  4809.6  813.25  4906.1  812.99  4939.8  811.86  4949.9  812.30  4959.9  814.17
  4969.9  814.40  4989.9  814.24  4997.4  813.35  5002.4  813.35  5009.9  809.86
  5019.9  811.15  5027.9  809.77  5028.2  809.27  5031.7  809.27  5031.9  809.77
  5039.9  811.04  5059.9  811.97  5189.9  813.84  5232.0  814.15  5279.9  814.27
  5339.9  815.12  5349.9  814.98  5359.9  815.67  5369.4  817.17  5373.9  817.17
#Mann=4,-1,0
  4702.4    0.05       0  5027.9    0.05       0  5031.9    0.05       0
  5232.0   0.075       0
Bank Sta=5027.9,5031.9
Exp/Cntr=0.3,0.1

Type RM Length L Ch R = 1,4684,272,272,272
BEGIN DESCRIPTION:
Henrietta Creek 6A 9.0
END DESCRIPTION:
XS GIS Cut Line= 3
      2306058.45      7042375.26      2306060.73      7041974.91
      2306047.15      7041723.73
#Sta/Elev= 30
  4734.9  813.86  4760.2  813.57  4770.2  813.23  4780.2  813.68  4810.2  814.02
  4840.2  813.60  4900.2  813.47  4930.2  813.00  4940.2  812.48  4950.2  811.38
  4960.2  809.68  4970.2  809.23  4978.2  809.20  4978.4  808.70  4981.9  808.70
  4982.2  809.20  5000.2  810.66  5010.2  812.46  5034.5  813.15  5110.2  813.91
  5140.2  813.89  5160.2  813.59  5210.3  814.16  5220.3  814.52  5250.3  814.57
  5280.4  814.97  5310.4  814.96  5320.4  815.54  5330.5  815.38  5386.8  816.39
#Mann=4,-1,0
  4734.9    0.05       0  4978.2    0.05       0  4982.2    0.05       0
  5034.5   0.075       0
Bank Sta=4978.2,4982.2
Exp/Cntr=0.3,0.1

Type RM Length L Ch R = 1,4412,179,179,179
BEGIN DESCRIPTION:
Henrietta Creek 6A 8.2
END DESCRIPTION:
XS GIS Cut Line= 2
      2306315.51      7042523.10      2306315.51      7041849.80
#Sta/Elev= 30
  4636.6  812.97  4659.7  812.86  4699.7  812.15  4779.7  811.28  4809.7  811.03
  4829.7  811.22  4859.7  811.04  4889.7  810.52  4899.7  810.08  4919.7  810.18
  4929.7  809.50  4939.7  809.61  4949.7  809.37  4979.7  809.74  5009.7  807.54
  5017.7  807.50  5018.0  807.00  5021.5  807.00  5021.7  807.50  5029.7  807.88
  5039.7  807.98  5049.7  809.11  5069.7  810.46  5109.7  810.06  5159.7  810.25
  5219.7  810.89  5239.7  811.54  5249.7  811.28  5259.7  811.68  5309.9  811.53
#Mann=3,-1,0
  4636.6    0.05       0  5017.7   0.033       0  5021.7    0.05       0
Bank Sta=5017.7,5021.7
Exp/Cntr=0.3,0.1

Type RM Length L Ch R = 1,4233,528,528,528
BEGIN DESCRIPTION:
Henrietta Creek 6A 8.0
END DESCRIPTION:
XS GIS Cut Line= 3
      2306449.72      7042554.98      2306479.00      7042210.00
      2306472.50      7041973.81
#Sta/Elev= 30
  4658.6  815.22  4663.6  815.22  4673.6  813.47  4683.7  813.99  4703.7  814.04
  4733.8  812.68  4764.0  812.43  4784.0  812.88  4828.3  811.70  4864.3  811.59
  4884.4  810.68  4904.5  808.96  4947.7  808.74  4984.7  806.58  4994.8  804.96
  5000.3  804.80  5000.6  804.30  5004.1  804.30  5004.3  804.80  5007.3  804.80
  5044.8  808.91  5054.8  809.36  5064.8  810.46  5074.8  810.76  5094.9  807.33
  5124.9  806.99  5134.9  807.12  5183.3  811.07  5224.9  812.36  5241.1  811.23
#Mann=3,-1,0
  4658.6    0.05       0  5000.3   0.033       0  5004.3    0.05       0
Bank Sta=5000.3,5004.3
Exp/Cntr=0.3,0.1

Type RM Length L Ch R = 1,3705,266,266,266
BEGIN DESCRIPTION:
Henrietta Creek 6A 7.0
END DESCRIPTION:
XS GIS Cut Line= 3
      2306829.00      7042609.99      2306929.00      7042410.00
      2306629.00      7041910.00
#Sta/Elev= 30
  4776.4  810.81  4779.2  810.81  4784.8  809.66  4798.8  808.85  4805.0  809.05
  4857.5  809.12  4865.8  808.06  4888.2  807.14  4918.9  804.71  4946.9  804.22
  4969.3  804.50  4991.6  801.88  4997.2  800.63  5011.6  800.16  5011.9  799.66
  5015.4  799.66  5015.6  800.16  5035.0  804.03  5050.5  805.46  5081.6  805.13
  5130.2  805.88  5198.3  805.59  5314.9  808.21  5363.5  807.87  5421.8  809.65
  5480.1  808.53  5511.2  806.53  5548.1  807.58  5569.5  810.14  5583.1  811.00
#Mann=4,-1,0
  4776.4   0.075       0  4805.0    0.05       0  5011.6   0.033       0
  5015.6    0.05       0
Bank Sta=5011.6,5015.6
Exp/Cntr=0.3,0.1

Type RM Length L Ch R = 1,3439,548,548,548
BEGIN DESCRIPTION:
Henrietta Creek 6A 6.0
END DESCRIPTION:
XS GIS Cut Line= 3
      2307029.00      7042660.00      2307179.00      7042460.00
      2306879.01      7041860.01
#Sta/Elev= 30
  4750.0  809.03  4753.1  809.03  4763.5  806.86  4792.7  804.55  4842.7  802.94
  4900.0  801.97  4907.3  800.42  4913.5  800.05  4950.0  798.92  4986.5  798.63
  4990.7  797.92  4991.0  797.42  4994.5  797.42  4994.7  797.92  4996.9  798.73
  5002.8  798.73  5008.4  801.31  5030.7  800.55  5067.1  800.64  5111.8  802.59
  5187.3  802.48  5232.0  803.07  5237.6  803.83  5335.4  805.27  5410.9  807.99
  5469.6  807.71  5545.0  804.77  5581.4  805.12  5640.1  808.98  5670.8  808.92
#Mann=3,-1,0
  4750.0    0.05       0  4990.7   0.033       0  4994.7    0.05       0
Bank Sta=4990.7,4994.7
Exp/Cntr=0.3,0.1

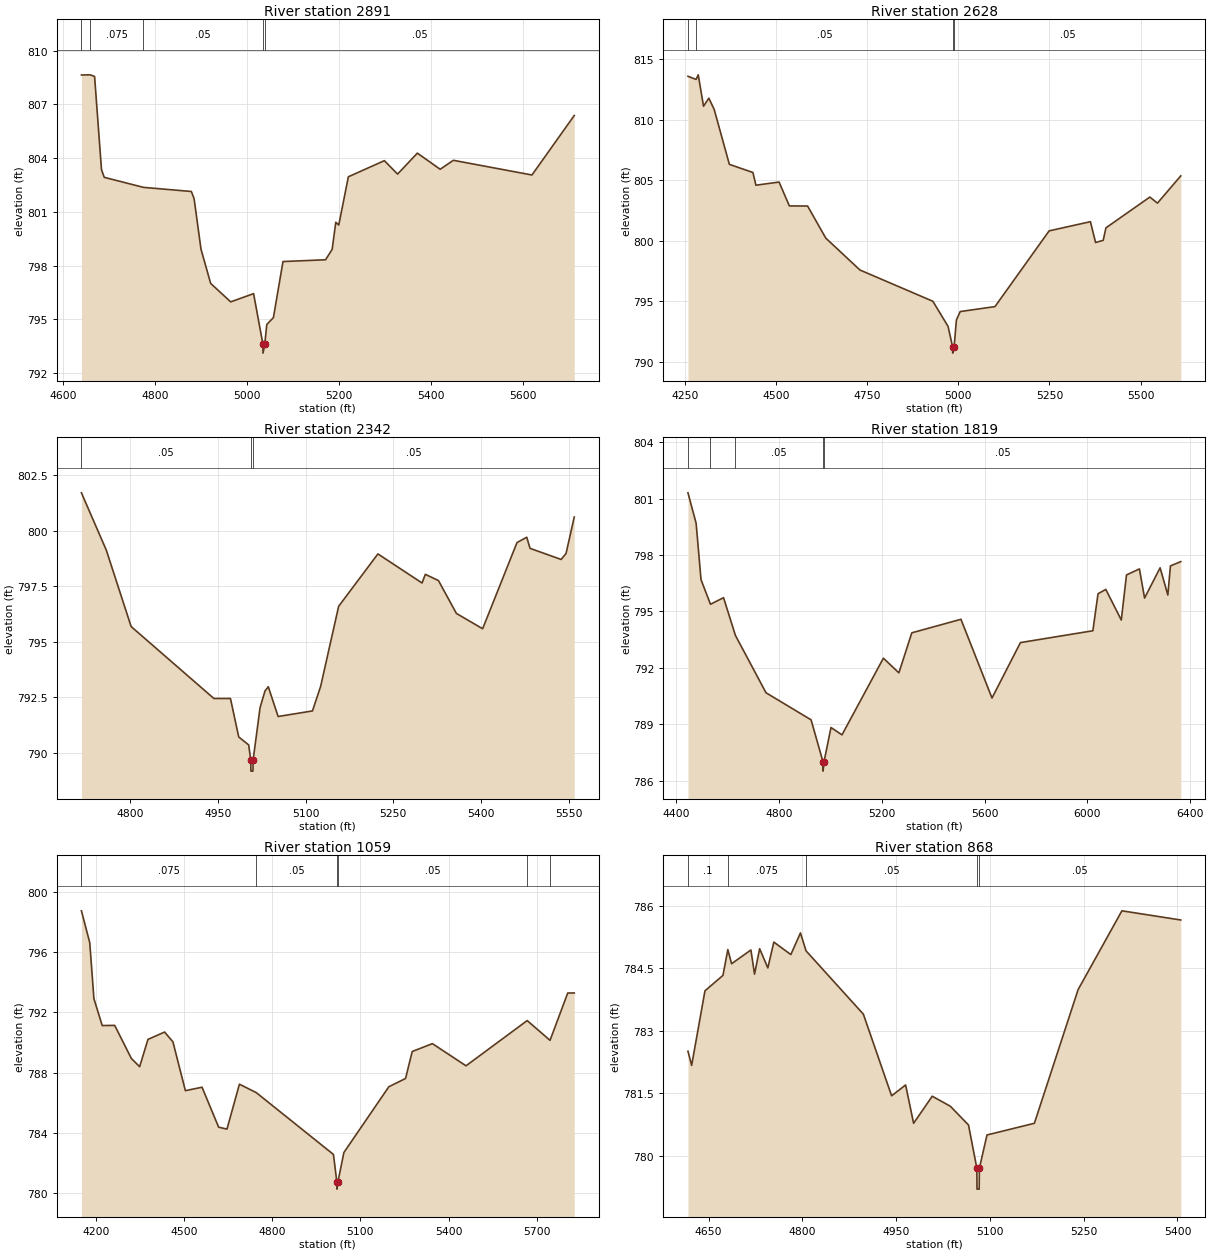
Type RM Length L Ch R = 1,2891,263,263,263
BEGIN DESCRIPTION:
Henrietta Creek 6A 5.0
END DESCRIPTION:
XS GIS Cut Line= 3
      2307478.99      7042910.01      2307679.00      7042610.00
      2307229.00      7042060.00
#Sta/Elev= 30
  4640.0  808.64  4659.1  808.65  4668.6  808.56  4683.6  803.36  4689.6  802.93
  4774.8  802.37  4878.9  802.14  4884.9  801.74  4899.9  798.92  4920.9  797.01
  4964.5  795.98  5014.2  796.44  5034.5  793.62  5034.7  793.12  5038.5  793.62
  5042.9  794.72  5057.3  795.10  5078.1  798.23  5170.7  798.33  5185.0  798.91
  5192.9  800.42  5199.4  800.27  5220.2  802.96  5298.5  803.86  5327.2  803.11
  5370.2  804.28  5419.8  803.38  5448.5  803.88  5619.3  803.06  5711.2  806.38
#Mann=5,-1,0
  4640.0    0.05       0  4659.1   0.075       0  4774.8    0.05       0
  5034.5   0.033       0  5038.5    0.05       0
Bank Sta=5034.5,5038.5
Exp/Cntr=0.3,0.1

Type RM Length L Ch R = 1,2628,286,286,286
BEGIN DESCRIPTION:
Henrietta Creek 6A 4.0
END DESCRIPTION:
XS GIS Cut Line= 3
      2307478.98      7043160.03      2307929.00      7042560.00
      2307479.01      7042160.01
#Sta/Elev= 30
  4258.2  813.58  4280.5  813.32  4286.4  813.70  4300.9  811.11  4315.5  811.77
  4330.1  810.85  4371.8  806.31  4436.4  805.64  4444.7  804.59  4508.2  804.85
  4536.4  802.88  4586.4  802.87  4636.4  800.22  4730.1  797.59  4930.1  795.01
  4971.8  792.94  4984.4  791.23  4984.6  790.73  4988.4  791.23  4994.7  793.46
  5005.1  794.16  5100.6  794.57  5249.1  800.82  5362.4  801.58  5376.6  799.86
  5397.5  800.04  5405.0  801.07  5525.4  803.61  5546.3  803.11  5610.3  805.36
#Mann=4,-1,0
  4258.2   0.075       0  4280.5    0.05       0  4984.4   0.033       0
  4988.4    0.05       0
Bank Sta=4984.4,4988.4
Exp/Cntr=0.3,0.1

Type RM Length L Ch R = 1,2342,523,523,523
BEGIN DESCRIPTION:
Henrietta Creek 6A 3.0
END DESCRIPTION:
XS GIS Cut Line= 3
      2307978.98      7042810.02      2308179.00      7042610.00
      2307929.00      7042109.99
#Sta/Elev= 30
  4717.1  801.71  4759.6  799.13  4802.0  795.69  4943.4  792.45  4971.7  792.45
  4985.8  790.72  5002.8  790.36  5006.4  789.68  5006.6  789.18  5010.1  789.18
  5010.4  789.68  5022.3  792.04  5030.7  792.79  5036.3  792.98  5053.1  791.64
  5111.8  791.89  5125.8  793.00  5156.5  796.60  5223.6  798.96  5299.0  797.65
  5304.6  798.04  5327.0  797.76  5357.7  796.28  5402.5  795.59  5461.2  799.47
  5477.9  799.71  5483.5  799.21  5536.6  798.71  5545.0  798.98  5559.0  800.62
#Mann=3,-1,0
  4717.1    0.05       0  5006.4   0.033       0  5010.4    0.05       0
Bank Sta=5006.4,5010.4
Exp/Cntr=0.3,0.1

Type RM Length L Ch R = 1,1819,760,760,760
BEGIN DESCRIPTION:
Henrietta Creek 6A 2.0
END DESCRIPTION:
XS GIS Cut Line= 3
      2308078.98      7042860.00      2308629.00      7042760.00
      2308479.01      7041410.05
#Sta/Elev= 30
  4445.6  801.31  4477.4  799.69  4496.4  796.69  4533.2  795.38  4584.1  795.73
  4630.3  793.72  4749.3  790.67  4924.6  789.23  4970.9  787.00  4971.1  786.50
  4974.9  787.00  5002.1  788.82  5044.9  788.43  5205.9  792.51  5266.2  791.73
  5316.5  793.86  5507.7  794.58  5628.5  790.39  5739.1  793.34  6020.9  793.97
  6041.0  795.94  6071.2  796.17  6131.5  794.54  6151.7  796.94  6202.0  797.26
  6222.1  795.71  6282.5  797.32  6312.6  795.87  6322.7  797.42  6362.9  797.65
#Mann=5,-1,0
  4445.6    0.05       0  4533.2   0.075       0  4630.3    0.05       0
  4970.9   0.033       0  4974.9    0.05       0
Bank Sta=4970.9,4974.9
Exp/Cntr=0.3,0.1

Type RM Length L Ch R = 1,1059,191,191,191
BEGIN DESCRIPTION:
Henrietta Creek 6A 1.0
END DESCRIPTION:
XS GIS Cut Line= 3
      2308578.98      7043760.02      2309179.00      7043160.00
      2308829.00      7042410.00
#Sta/Elev= 30
  4151.4  798.74  4179.7  796.63  4193.9  792.91  4222.1  791.13  4264.6  791.14
  4321.1  788.95  4349.4  788.40  4377.7  790.21  4434.3  790.70  4462.6  790.05
  4505.0  786.81  4561.6  787.04  4618.1  784.39  4646.4  784.26  4688.8  787.24
  4746.2  786.68  5008.6  782.58  5020.0  780.78  5020.3  780.28  5024.0  780.78
  5044.1  782.71  5197.0  787.07  5253.8  787.62  5276.6  789.41  5345.2  789.93
  5459.5  788.46  5667.6  791.46  5745.3  790.15  5805.5  793.29  5827.6  793.29
#Mann=6,-1,0
  4151.4   0.075       0  4746.2    0.05       0  5020.0   0.033       0
  5024.0    0.05       0  5667.6   0.075       0  5745.3    0.05       0
Bank Sta=5020,5024
Exp/Cntr=0.3,0.1

Type RM Length L Ch R = 1,868,245,245,245
BEGIN DESCRIPTION:
Henrietta Creek 6A 0.2
END DESCRIPTION:
XS GIS Cut Line= 3
      2309129.49      7043587.76      2309400.18      7043146.45
      2309400.18      7042875.76
#Sta/Elev= 30
  4616.9  782.51  4622.8  782.17  4644.1  783.96  4672.9  784.33  4680.7  784.95
  4686.7  784.61  4717.6  784.94  4723.4  784.36  4731.6  784.97  4744.7  784.51
  4754.3  785.13  4781.5  784.83  4796.9  785.35  4805.8  784.92  4897.5  783.40
  4942.7  781.44  4965.1  781.70  4977.9  780.78  5007.7  781.43  5036.6  781.19
  5065.7  780.74  5079.1  779.70  5079.3  779.20  5082.8  779.20  5083.1  779.70
  5095.3  780.50  5171.1  780.78  5241.1  783.99  5311.1  785.88  5405.3  785.66
#Mann=5,-1,0
  4616.9     0.1       0  4680.7   0.075       0  4805.8    0.05       0
  5079.1   0.033       0  5083.1    0.05       0
Bank Sta=5079.1,5083.1
Exp/Cntr=0.3,0.1

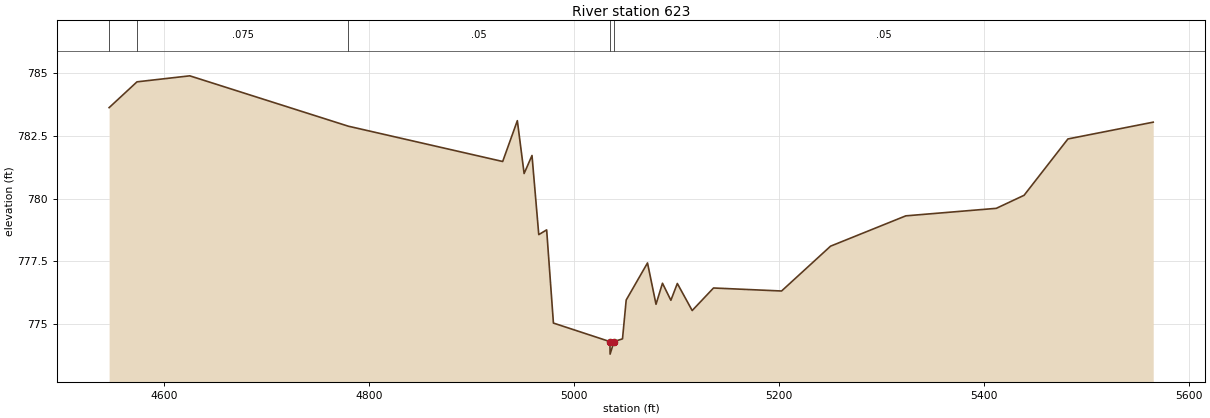
Type RM Length L Ch R = 1,623,0,0,0
BEGIN DESCRIPTION:
Henrietta Creek 6A 0.1
END DESCRIPTION:
XS GIS Cut Line= 4
      2309211.35      7043603.71      2309591.27      7043280.67
      2309686.81      7043155.55      2309577.63      7042809.80
#Sta/Elev= 30
  4546.2  783.63  4573.4  784.66  4624.9  784.90  4779.5  782.89  4930.2  781.48
  4944.5  783.11  4951.1  781.00  4958.8  781.72  4965.4  778.56  4973.1  778.75
  4979.7  775.03  5034.8  774.29  5035.0  773.79  5038.8  774.29  5047.1  774.40
  5050.7  775.95  5071.5  777.43  5079.8  775.78  5086.1  776.62  5094.3  775.94
  5100.6  776.61  5115.1  775.53  5135.9  776.43  5202.3  776.31  5250.1  778.10
  5323.5  779.31  5411.8  779.61  5438.9  780.13  5481.7  782.38  5564.9  783.05
#Mann=5,-1,0
  4546.2     0.1       0  4573.4   0.075       0  4779.5    0.05       0
  5034.8    0.05       0  5038.8    0.05       0
Bank Sta=5034.8,5038.8
Exp/Cntr=0.3,0.1

Chan Stop Cuts=-1