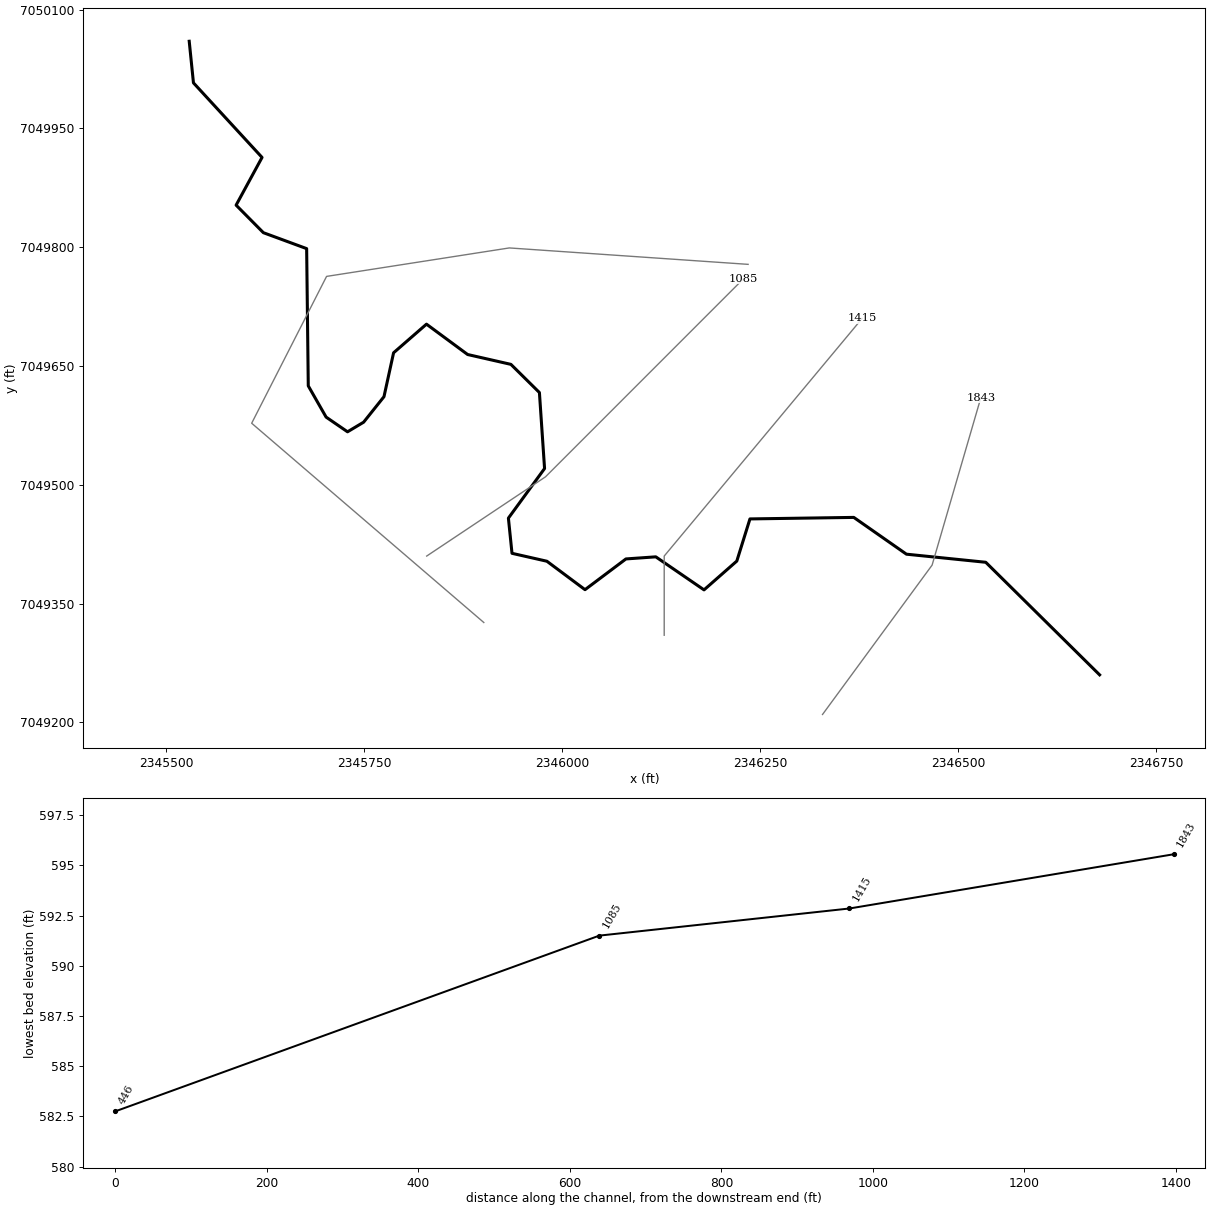
--- Henrietta Creek Tributary 2.prj (project) ---

Proj Title=Henrietta Creek Tributary 2 Base Level Engineering
Current Plan=p01
Default Exp/Contr=0.3,0.1
English Units
Geom File=g01
Flow File=f01
Plan File=p01
BEGIN DESCRIPTION:
Henrietta Creek Tributary 2
END DESCRIPTION:

--- Henrietta Creek Tributary 2.p01 (plan) ---

Plan Title=Multiple Run
Short Identifier=Multiple
Geom File=g01
Flow File=f01
Subcritical Flow
K Sum by GR= 0
Std Step Tol= 0.01
Critical Tol= 0.01
Num of Std Step Trials= 20
Max Error Tol= 0.3
Flow Tol Ratio= 0.001
Split Flow NTrial= 30
Split Flow Tol= 0.02
Split Flow Ratio= 0.02
Log Output Level= 0
Friction Slope Method= 1
Unsteady Friction Slope Method= 2
Unsteady Bridges Friction Slope Method= 1
Parabolic Critical Depth
Global Vel Dist=  1 , 1 , 1
Global Log Level= 0
CheckData=True
Encroach Param= -1, 0, 0, 0
BEGIN DESCRIPTION:
Multiple Run
END DESCRIPTION:

--- Henrietta Creek Tributary 2.f01 (steady flow) ---

Flow Title=Multiple
Number of Profiles=7
Profile Names=10-year,25-year,50-year,1pct_min,100-year,1pct_plu,500-year
River Rch & RM= Henrietta Creek ,Reach-1,1843
     458     620     752     454     906    1810    1320
Boundary for River Rch & Prof#=Henrietta Creek ,Reach-1,1
Up Type=0
Dn Type=3
Dn Slope=0.005
Boundary for River Rch & Prof#=Henrietta Creek ,Reach-1,2
Up Type=0
Dn Type=3
Dn Slope=0.005
Boundary for River Rch & Prof#=Henrietta Creek ,Reach-1,3
Up Type=0
Dn Type=3
Dn Slope=0.005
Boundary for River Rch & Prof#=Henrietta Creek ,Reach-1,4
Up Type=0
Dn Type=3
Dn Slope=0.005
Boundary for River Rch & Prof#=Henrietta Creek ,Reach-1,5
Up Type=0
Dn Type=3
Dn Slope=0.005
Boundary for River Rch & Prof#=Henrietta Creek ,Reach-1,6
Up Type=0
Dn Type=3
Dn Slope=0.005
Boundary for River Rch & Prof#=Henrietta Creek ,Reach-1,7
Up Type=0
Dn Type=3
Dn Slope=0.005

--- Henrietta Creek Tributary 2.g01 (geometry) ---

Geom Title=Existing Conditions

River Reach=Henrietta Creek ,Reach-1
Reach XY= 30
      2346679.00      7049260.00      2346535.17      7049402.14
      2346434.98      7049412.36      2346368.48      7049458.80
      2346237.31      7049456.89      2346220.70      7049403.66
      2346179.29      7049367.29      2346118.37      7049409.01
      2346080.65      7049406.36      2346028.97      7049367.55
      2345980.82      7049403.45      2345936.74      7049413.46
      2345932.19      7049457.89      2345977.87      7049520.53
      2345971.36      7049616.46      2345935.38      7049652.02
      2345880.67      7049664.48      2345828.70      7049702.80
      2345787.15      7049666.65      2345775.01      7049611.21
      2345749.30      7049579.02      2345728.97      7049566.88
      2345701.91      7049585.45      2345679.39      7049624.88
      2345677.34      7049798.17      2345622.68      7049818.30
      2345588.23      7049853.07      2345621.00      7049913.32
      2345534.35      7050007.48      2345529.00      7050060.00

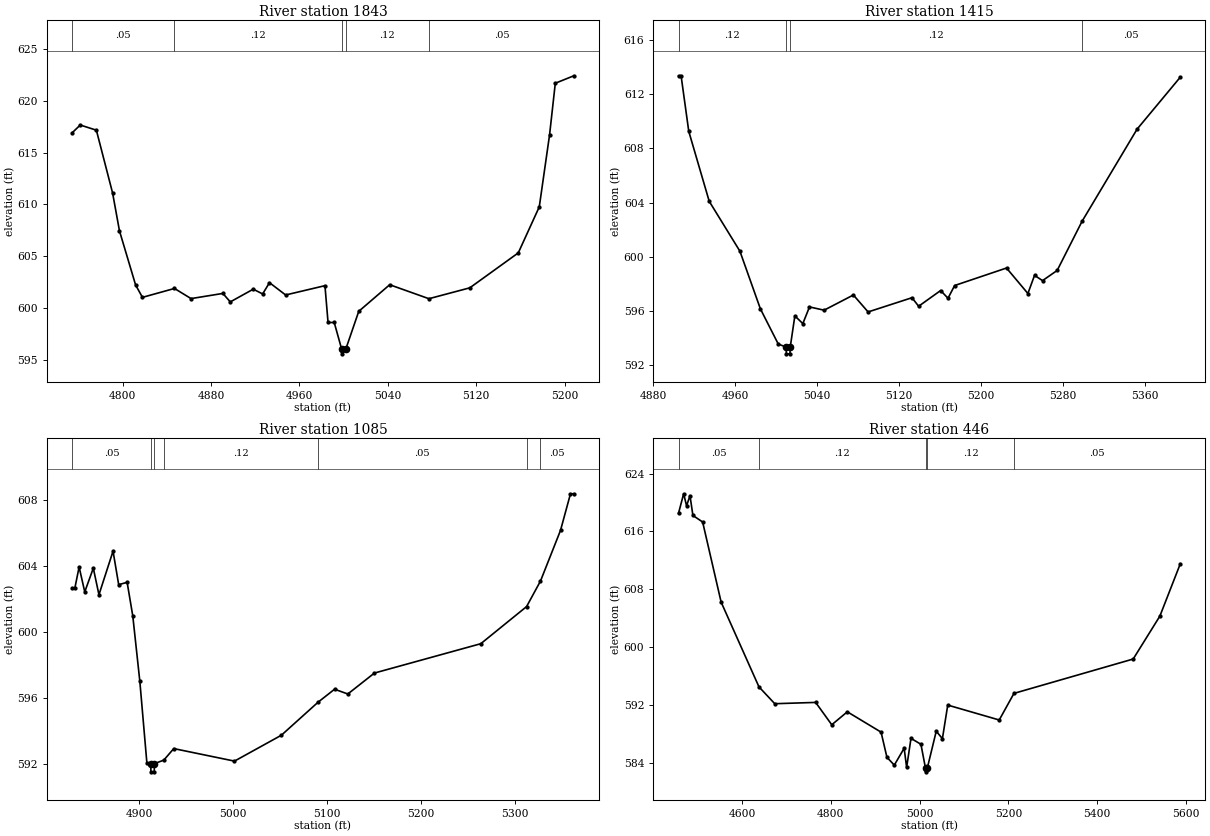
Type RM Length L Ch R = 1,1843,428,428,428
BEGIN DESCRIPTION:
Henrietta Creek Tributary 2 3.0
END DESCRIPTION:
XS GIS Cut Line= 3
      2346328.98      7049209.97      2346467.40      7049398.56
      2346529.01      7049610.03
#Sta/Elev= 30
  4754.2  616.91  4761.6  617.67  4776.2  617.17  4790.9  611.09  4797.1  607.44
  4811.7  602.21  4817.9  601.01  4846.9  601.87  4861.9  600.89  4890.7  601.39
  4897.4  600.57  4918.2  601.80  4926.7  601.34  4932.9  602.43  4947.5  601.24
  4983.1  602.14  4985.9  598.58  4991.5  598.58  4998.1  596.05  4998.3  595.55
  5002.1  596.05  5013.7  599.66  5041.7  602.23  5077.2  600.88  5114.2  601.93
  5158.1  605.31  5177.1  609.76  5186.4  616.71  5191.6  621.71  5208.4  622.43
#Mann=5,-1,0
  4754.2    0.05       0  4846.9    0.12       0  4998.1    0.07       0
  5002.1    0.12       0  5077.2    0.05       0
Bank Sta=4998.1,5002.1
Exp/Cntr=0.3,0.1

Type RM Length L Ch R = 1,1415,330,330,330
BEGIN DESCRIPTION:
Henrietta Creek Tributary 2 2.0
END DESCRIPTION:
XS GIS Cut Line= 3
      2346129.00      7049310.00      2346129.00      7049410.00
      2346378.99      7049709.99
#Sta/Elev= 30
  4904.5  613.36  4907.0  613.36  4914.5  609.26  4934.5  604.10  4964.5  600.42
  4984.5  596.17  5002.0  593.57  5009.7  593.35  5009.9  592.85  5013.4  592.85
  5013.7  593.35  5018.2  595.65  5026.0  595.08  5032.5  596.31  5046.8  596.07
  5075.4  597.19  5089.8  595.94  5132.7  596.99  5139.2  596.36  5160.7  597.52
  5167.9  596.95  5174.4  597.89  5225.1  599.18  5246.0  597.30  5252.5  598.64
  5260.3  598.25  5274.6  599.00  5298.9  602.62  5352.7  609.42  5395.0  613.26
#Mann=4,-1,0
  4904.5    0.12       0  5009.7    0.07       0  5013.7    0.12       0
  5298.9    0.05       0
Bank Sta=5009.7,5013.7
Exp/Cntr=0.3,0.1

Type RM Length L Ch R = 1,1085,639,639,639
BEGIN DESCRIPTION:
Henrietta Creek Tributary 2 1.0
END DESCRIPTION:
XS GIS Cut Line= 3
      2345828.98      7049409.99      2345979.00      7049510.00
      2346229.03      7049760.03
#Sta/Elev= 30
  4828.6  602.65  4831.6  602.65  4836.1  603.92  4842.1  602.41  4851.2  603.85
  4857.2  602.24  4872.2  604.88  4878.2  602.85  4887.2  602.99  4893.2  600.95
  4900.7  596.99  4908.2  592.04  4912.3  592.00  4912.5  591.50  4916.0  591.50
  4916.3  592.00  4926.2  592.21  4936.8  592.91  5001.4  592.15  5051.3  593.72
  5090.3  595.72  5107.9  596.51  5122.0  596.22  5150.3  597.49  5263.5  599.27
  5312.2  601.52  5327.0  603.07  5348.3  606.14  5358.9  608.36  5362.5  608.36
#Mann=7,-1,0
  4828.6    0.05       0  4912.3    0.07       0  4916.3    0.05       0
  4926.2    0.12       0  5090.3    0.05       0  5312.2    0.12       0
  5327.0    0.05       0
Bank Sta=4912.3,4916.3
Exp/Cntr=0.3,0.1

Type RM Length L Ch R = 1,446,0,0,0
BEGIN DESCRIPTION:
Henrietta Creek Tributary 2 0.5
END DESCRIPTION:
XS GIS Cut Line= 5
      2345901.12      7049326.10      2345607.90      7049577.70
      2345702.50      7049763.10      2345933.30      7049799.05
      2346235.00      7049778.31
#Sta/Elev= 30
  4457.0  618.51  4468.5  621.20  4475.1  619.54  4482.8  620.94  4489.4  618.20
  4511.3  617.30  4553.0  606.21  4638.2  594.50  4673.8  592.17  4765.9  592.35
  4802.2  589.26  4837.3  591.05  4913.3  588.24  4926.5  584.76  4943.1  583.68
  4965.3  586.01  4970.9  583.36  4980.7  587.38  5003.1  586.56  5013.4  583.25
  5013.6  582.75  5017.4  583.25  5037.6  588.37  5051.5  587.34  5063.5  591.98
  5179.5  589.92  5212.7  593.60  5481.3  598.35  5541.4  604.28  5587.5  611.53
#Mann=5,-1,0
  4457.0    0.05       0  4638.2    0.12       0  5013.4    0.07       0
  5017.4    0.12       0  5212.7    0.05       0
Bank Sta=5013.4,5017.4
Exp/Cntr=0.3,0.1

Chan Stop Cuts=-1