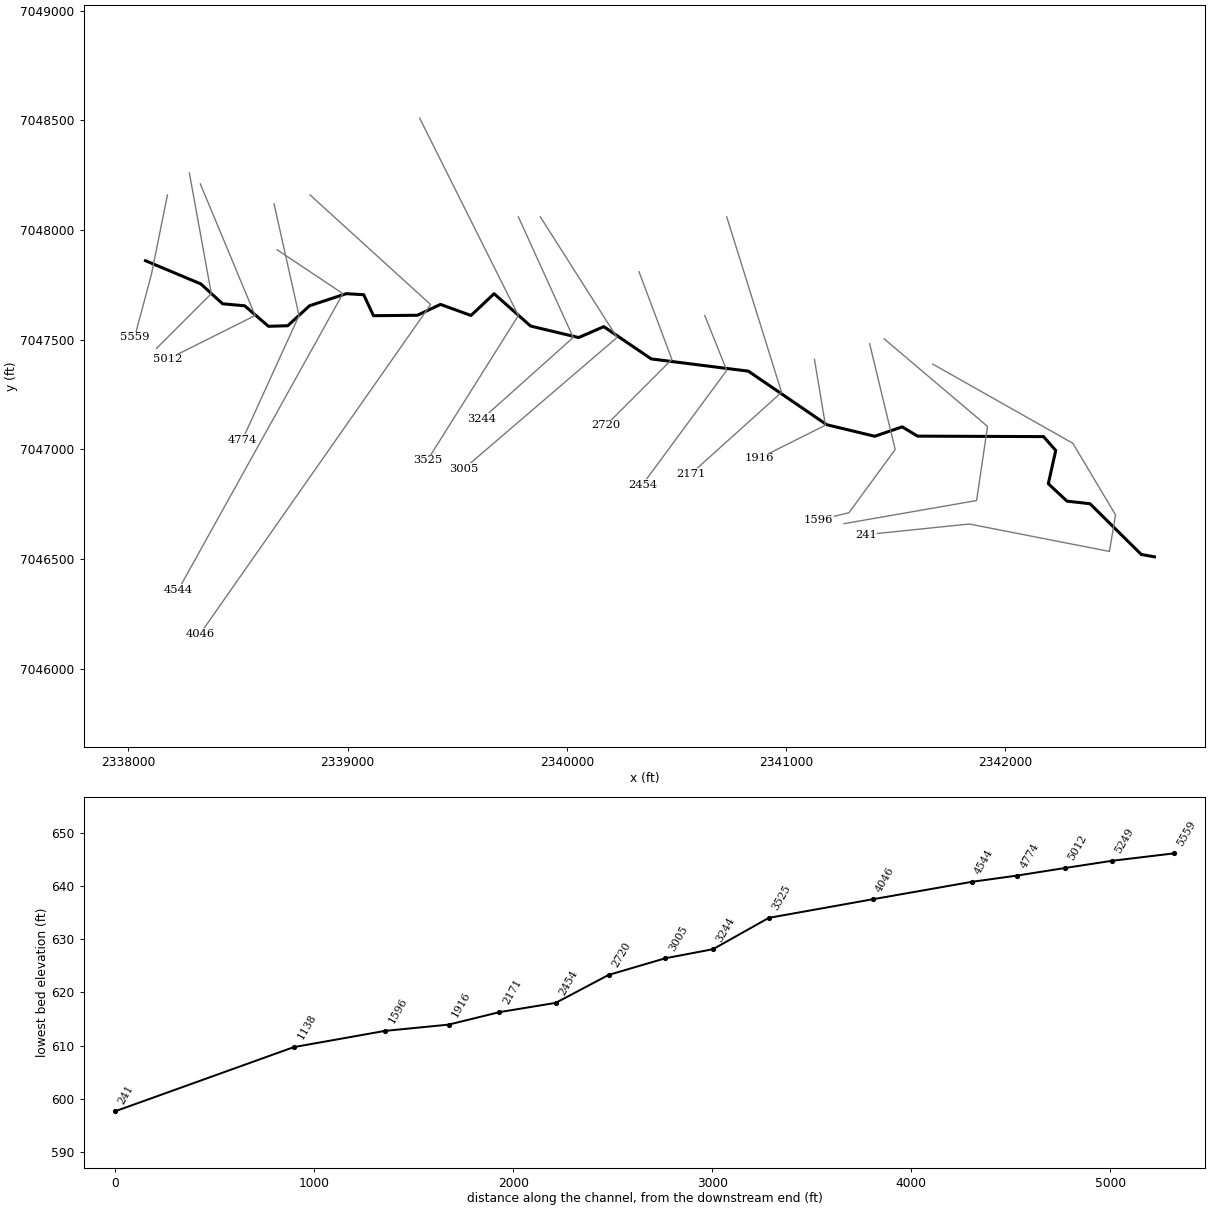
--- Henrietta Creek Tributary 4.prj (project) ---

Proj Title=Henrietta Creek Tributary 4 Base Level Engineering
Current Plan=p01
Default Exp/Contr=0.3,0.1
English Units
Geom File=g01
Flow File=f01
Plan File=p01
BEGIN DESCRIPTION:
Henrietta Creek Tributary 4
END DESCRIPTION:

--- Henrietta Creek Tributary 4.p01 (plan) ---

Plan Title=Multiple Run
Short Identifier=Multiple
Geom File=g01
Flow File=f01
Subcritical Flow
K Sum by GR= 0
Std Step Tol= 0.01
Critical Tol= 0.01
Num of Std Step Trials= 20
Max Error Tol= 0.3
Flow Tol Ratio= 0.001
Split Flow NTrial= 30
Split Flow Tol= 0.02
Split Flow Ratio= 0.02
Log Output Level= 0
Friction Slope Method= 1
Unsteady Friction Slope Method= 2
Unsteady Bridges Friction Slope Method= 1
Parabolic Critical Depth
Global Vel Dist=  1 , 1 , 1
Global Log Level= 0
CheckData=True
Encroach Param= -1, 0, 0, 0
BEGIN DESCRIPTION:
Multiple Run
END DESCRIPTION:

--- Henrietta Creek Tributary 4.f01 (steady flow) ---

Flow Title=Multiple
Number of Profiles=7
Profile Names=10-year,25-year,50-year,1pct_min,100-year,1pct_plu,500-year
River Rch & RM= Henrietta Creek ,Reach-1,5559
     250     321     375     218     435     868     584
Boundary for River Rch & Prof#=Henrietta Creek ,Reach-1,1
Up Type=0
Dn Type=3
Dn Slope=0.005
Boundary for River Rch & Prof#=Henrietta Creek ,Reach-1,2
Up Type=0
Dn Type=3
Dn Slope=0.005
Boundary for River Rch & Prof#=Henrietta Creek ,Reach-1,3
Up Type=0
Dn Type=3
Dn Slope=0.005
Boundary for River Rch & Prof#=Henrietta Creek ,Reach-1,4
Up Type=0
Dn Type=3
Dn Slope=0.005
Boundary for River Rch & Prof#=Henrietta Creek ,Reach-1,5
Up Type=0
Dn Type=3
Dn Slope=0.005
Boundary for River Rch & Prof#=Henrietta Creek ,Reach-1,6
Up Type=0
Dn Type=3
Dn Slope=0.005
Boundary for River Rch & Prof#=Henrietta Creek ,Reach-1,7
Up Type=0
Dn Type=3
Dn Slope=0.005

--- Henrietta Creek Tributary 4.g01 (geometry) ---

Geom Title=Existing Conditions

River Reach=Henrietta Creek ,Reach-1
Reach XY= 30
      2338079.00      7047860.00      2338331.29      7047754.15
      2338430.50      7047663.63      2338531.42      7047654.46
      2338639.49      7047560.94      2338727.50      7047563.47
      2338826.58      7047654.46      2338994.42      7047709.68
      2339073.86      7047704.96      2339118.31      7047609.31
      2339318.50      7047611.22      2339423.97      7047660.80
      2339562.98      7047610.25      2339668.32      7047709.47
      2339834.86      7047562.07      2340054.00      7047509.61
      2340168.37      7047559.39      2340384.93      7047412.24
      2340827.53      7047356.45      2341184.93      7047112.25
      2341404.00      7047059.61      2341529.00      7047102.44
      2341598.98      7047060.18      2342173.38      7047058.02
      2342229.10      7046994.80      2342195.20      7046843.29
      2342280.48      7046763.61      2342385.17      7046752.14
      2342619.21      7046520.51      2342679.00      7046510.00

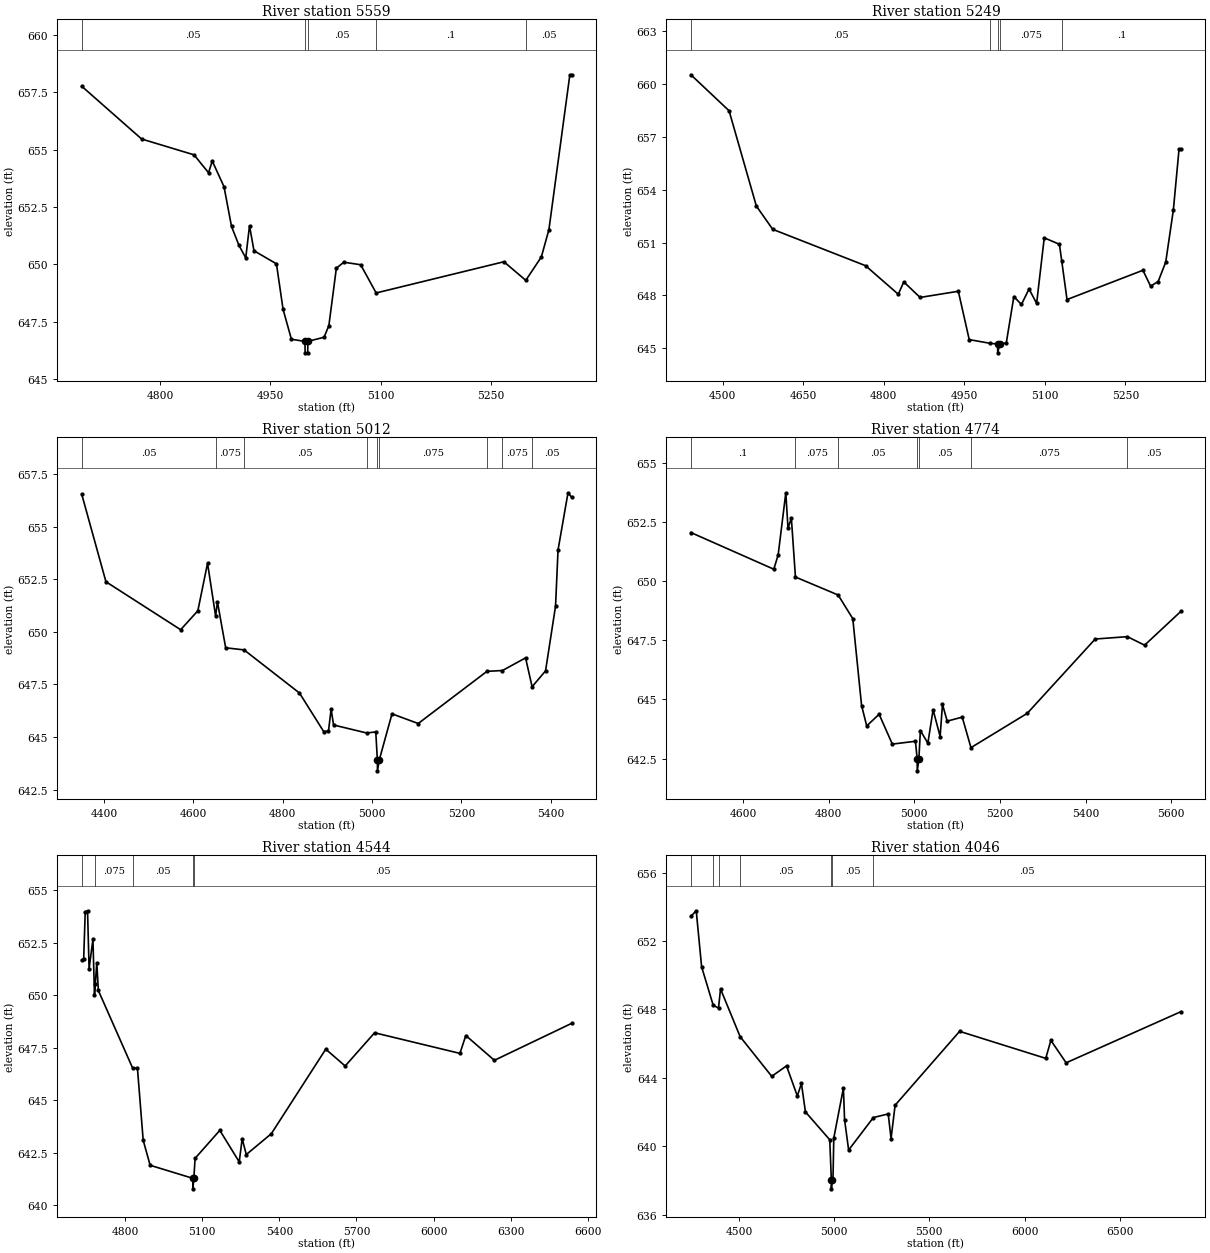
Type RM Length L Ch R = 1,5559,310,310,310
BEGIN DESCRIPTION:
Henrietta Creek Tributary 4 13.0
END DESCRIPTION:
XS GIS Cut Line= 3
      2338179.00      7048159.98      2338105.82      7047797.17
      2338029.00      7047509.98
#Sta/Elev= 30
  4692.9  657.76  4774.5  655.46  4845.9  654.77  4865.6  653.99  4870.7  654.50
  4886.7  653.38  4896.9  651.65  4907.1  650.82  4916.3  650.28  4921.4  651.68
  4927.5  650.59  4958.1  650.02  4967.1  648.04  4978.5  646.73  4996.9  646.64
  4997.2  646.14  5000.7  646.14  5000.9  646.64  5023.0  646.82  5029.5  647.33
  5039.7  649.83  5049.9  650.09  5072.8  649.98  5093.9  648.75  5267.9  650.11
  5297.7  649.30  5318.9  650.32  5329.2  651.51  5357.7  658.26  5360.3  658.26
#Mann=5,-1,0
  4692.9    0.05       0  4996.9   0.033       0  5000.9    0.05       0
  5093.9     0.1       0  5297.7    0.05       0
Bank Sta=4996.9,5000.9
Exp/Cntr=0.3,0.1

Type RM Length L Ch R = 1,5249,237,237,237
BEGIN DESCRIPTION:
Henrietta Creek Tributary 4 12.0
END DESCRIPTION:
XS GIS Cut Line= 3
      2338279.01      7048259.96      2338379.00      7047710.00
      2338129.02      7047460.02
#Sta/Elev= 30
  4441.0  660.51  4512.1  658.47  4562.9  653.07  4593.4  651.75  4766.2  649.69
  4827.2  648.07  4837.4  648.77  4867.8  647.89  4939.0  648.24  4959.3  645.50
  4998.2  645.29  5012.1  645.25  5012.4  644.75  5016.1  645.25  5028.3  645.31
  5042.4  647.94  5056.5  647.49  5070.7  648.37  5084.8  647.55  5099.0  651.27
  5127.3  650.90  5131.6  649.95  5141.4  647.77  5282.8  649.43  5297.0  648.53
  5311.1  648.79  5325.2  649.89  5339.4  652.84  5350.0  656.29  5353.5  656.29
#Mann=5,-1,0
  4441.0    0.05       0  4998.2   0.075       0  5012.1    0.07       0
  5016.1   0.075       0  5131.6     0.1       0
Bank Sta=5012.1,5016.1
Exp/Cntr=0.3,0.1

Type RM Length L Ch R = 1,5012,238,238,238
BEGIN DESCRIPTION:
Henrietta Creek Tributary 4 11.0
END DESCRIPTION:
XS GIS Cut Line= 3
      2338329.01      7048209.99      2338579.00      7047610.00
      2338179.00      7047410.00
#Sta/Elev= 30
  4350.0  656.54  4404.2  652.38  4571.5  650.10  4610.0  651.00  4631.7  653.26
  4649.8  650.75  4653.9  651.42  4672.3  649.24  4713.5  649.14  4837.5  647.09
  4891.7  645.26  4902.5  645.28  4908.4  646.32  4913.9  645.57  4987.9  645.19
  5008.4  645.24  5012.0  643.89  5012.2  643.39  5016.0  643.89  5044.7  646.10
  5103.4  645.64  5257.3  648.12  5292.1  648.16  5343.8  648.76  5358.4  647.39
  5388.5  648.14  5410.9  651.22  5416.5  653.89  5438.8  656.61  5447.2  656.39
#Mann=9,-1,0
  4350.0    0.05       0  4649.8   0.075       0  4713.5    0.05       0
  4987.9   0.075       0  5012.0    0.07       0  5016.0   0.075       0
  5257.3     0.1       0  5292.1   0.075       0  5358.4    0.05       0
Bank Sta=5012,5016
Exp/Cntr=0.3,0.1

Type RM Length L Ch R = 1,4774,230,230,230
BEGIN DESCRIPTION:
Henrietta Creek Tributary 4 10.0
END DESCRIPTION:
XS GIS Cut Line= 3
      2338665.10      7048118.91      2338779.00      7047610.00
      2338520.80      7047043.47
#Sta/Elev= 30
  4478.5  652.05  4672.1  650.50  4682.3  651.11  4700.1  653.73  4705.2  652.24
  4713.1  652.65  4722.6  650.17  4822.3  649.41  4856.5  648.41  4877.0  644.74
  4889.0  643.88  4918.0  644.37  4948.8  643.11  5002.8  643.23  5006.8  642.48
  5007.0  641.98  5010.8  642.48  5014.3  643.68  5031.8  643.15  5044.0  644.56
  5060.4  643.43  5065.9  644.79  5076.9  644.08  5112.0  644.25  5132.4  642.96
  5263.8  644.41  5422.5  647.55  5497.6  647.65  5537.8  647.29  5622.6  648.72
#Mann=7,-1,0
  4478.5     0.1       0  4722.6   0.075       0  4822.3    0.05       0
  5006.8   0.033       0  5010.8    0.05       0  5132.4   0.075       0
  5497.6    0.05       0
Bank Sta=5006.8,5010.8
Exp/Cntr=0.3,0.1

Type RM Length L Ch R = 1,4544,498,498,498
BEGIN DESCRIPTION:
Henrietta Creek Tributary 4 9.0
END DESCRIPTION:
XS GIS Cut Line= 3
      2338678.96      7047910.03      2338979.00      7047710.00
      2338229.02      7046360.04
#Sta/Elev= 30
  4631.9  651.66  4639.5  651.73  4645.5  653.96  4654.5  654.01  4660.5  651.26
  4675.5  652.65  4681.5  649.99  4684.6  650.52  4690.5  651.54  4696.5  650.22
  4830.2  646.52  4848.3  646.55  4870.8  643.10  4897.9  641.91  5063.7  641.29
  5064.0  640.79  5067.7  641.29  5072.6  642.24  5168.7  643.57  5244.2  642.07
  5255.6  643.17  5271.6  642.42  5368.9  643.41  5580.5  647.43  5656.0  646.63
  5770.4  648.21  6102.1  647.23  6125.0  648.08  6236.0  646.90  6536.8  648.66
#Mann=5,-1,0
  4631.9     0.1       0  4684.6   0.075       0  4830.2    0.05       0
  5063.7   0.033       0  5067.7    0.05       0
Bank Sta=5063.7,5067.7
Exp/Cntr=0.3,0.1

Type RM Length L Ch R = 1,4046,521,521,521
BEGIN DESCRIPTION:
Henrietta Creek Tributary 4 8.0
END DESCRIPTION:
XS GIS Cut Line= 3
      2338829.03      7048159.97      2339379.00      7047660.00
      2338329.02      7046160.03
#Sta/Elev= 30
  4247.4  653.45  4275.4  653.77  4303.8  650.49  4364.4  648.25  4392.5  648.08
  4403.1  649.20  4506.0  646.41  4672.0  644.09  4749.8  644.70  4806.5  642.94
  4828.1  643.67  4849.1  642.01  4976.8  640.38  4985.3  638.01  4985.5  637.51
  4989.3  638.01  4993.7  638.01  4998.1  640.48  5048.6  643.40  5054.7  641.55
  5076.1  639.78  5206.0  641.68  5284.0  641.89  5298.9  640.45  5320.2  642.40
  5659.0  646.72  6111.5  645.14  6138.5  646.19  6218.7  644.88  6821.6  647.87
#Mann=7,-1,0
  4247.4   0.075       0  4364.4     0.1       0  4392.5   0.075       0
  4506.0    0.05       0  4985.3    0.07       0  4989.3    0.05       0
  5206.0    0.05       0
Bank Sta=4985.3,4989.3
Exp/Cntr=0.3,0.1

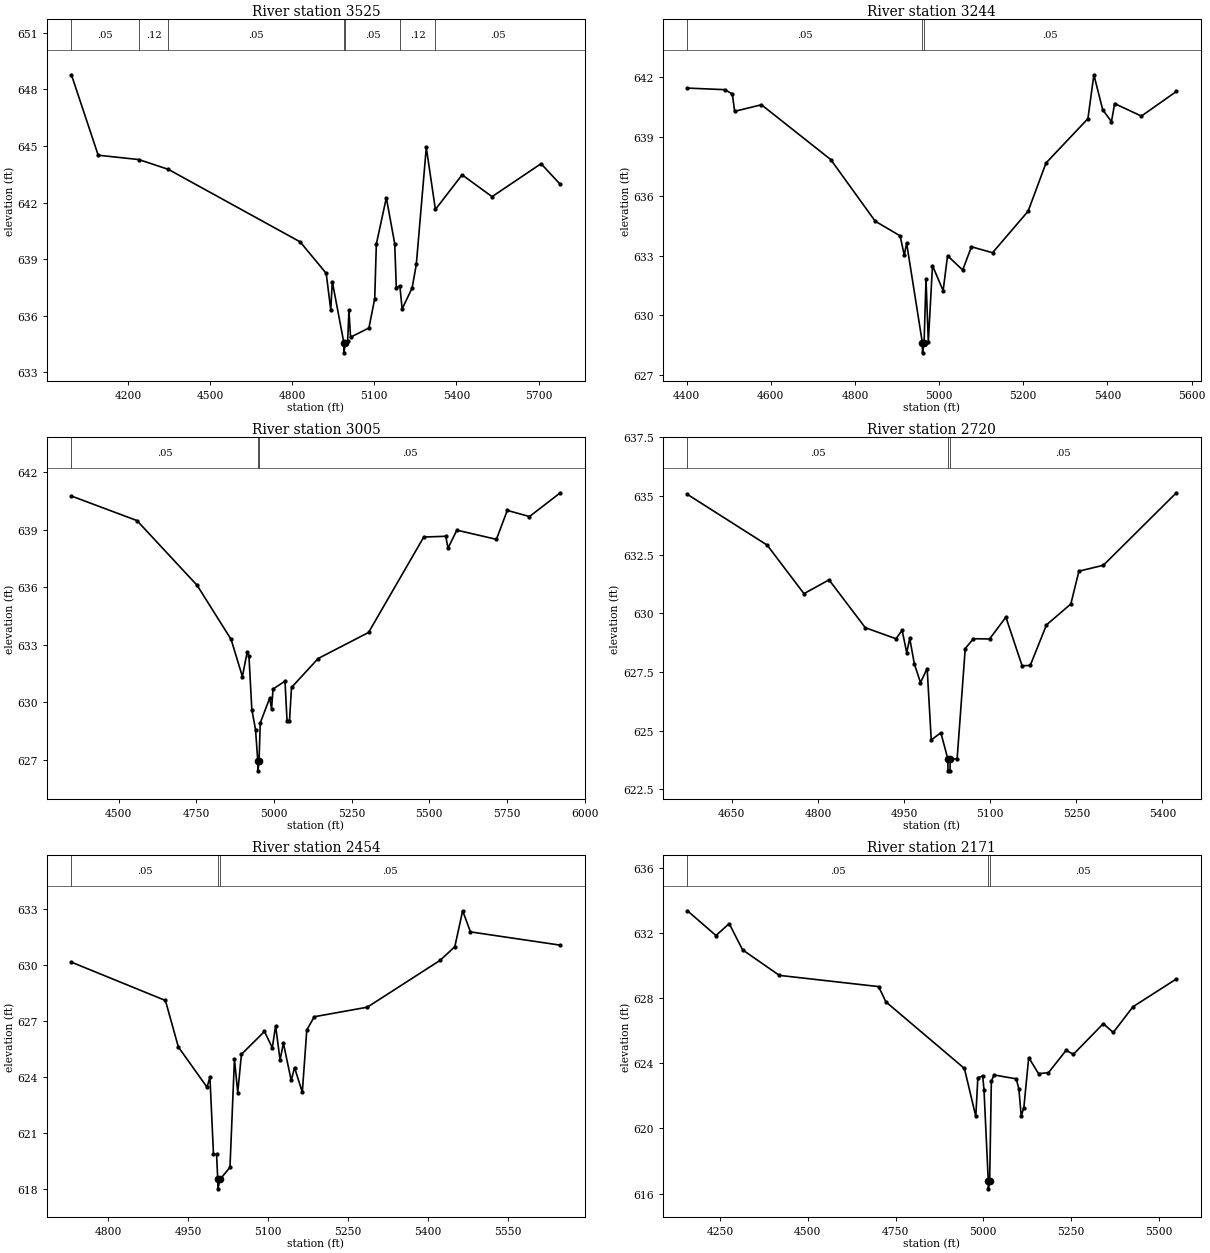
Type RM Length L Ch R = 1,3525,281,281,281
BEGIN DESCRIPTION:
Henrietta Creek Tributary 4 7.0
END DESCRIPTION:
XS GIS Cut Line= 3
      2339329.00      7048509.99      2339779.00      7047610.00
      2339363.85      7046949.68
#Sta/Elev= 30
  3993.5  648.78  4091.3  644.51  4239.5  644.28  4347.5  643.76  4829.2  639.91
  4924.3  638.24  4941.0  636.30  4946.6  637.80  4989.3  634.52  4989.6  634.02
  4993.3  634.52  5002.7  634.63  5007.4  636.28  5013.3  634.85  5080.4  635.34
  5101.6  636.90  5107.5  639.79  5144.0  642.25  5174.6  639.82  5180.5  637.48
  5193.5  637.57  5201.7  636.35  5238.2  637.46  5253.5  638.71  5290.0  644.92
  5323.3  641.63  5420.8  643.47  5530.3  642.31  5709.3  644.06  5779.7  642.96
#Mann=7,-1,0
  3993.5    0.05       0  4239.5    0.12       0  4347.5    0.05       0
  4989.3   0.033       0  4993.3    0.05       0  5193.5    0.12       0
  5323.3    0.05       0
Bank Sta=4989.3,4993.3
Exp/Cntr=0.3,0.1

Type RM Length L Ch R = 1,3244,239,239,239
BEGIN DESCRIPTION:
Henrietta Creek Tributary 4 6.0
END DESCRIPTION:
XS GIS Cut Line= 3
      2339778.99      7048060.02      2340029.00      7047510.00
      2339613.52      7047138.23
#Sta/Elev= 30
  4402.0  641.45  4491.0  641.37  4508.6  641.15  4514.1  640.28  4577.8  640.61
  4742.5  637.85  4848.0  634.75  4907.3  634.01  4917.2  633.03  4922.7  633.65
  4960.2  628.62  4960.5  628.12  4964.2  628.62  4968.8  631.83  4974.3  628.66
  4984.2  632.51  5009.5  631.25  5020.0  633.01  5055.9  632.29  5076.8  633.46
  5126.9  633.16  5211.4  635.25  5254.0  637.68  5353.5  639.91  5367.7  642.12
  5388.6  640.36  5409.5  639.76  5417.0  640.67  5480.6  640.04  5563.7  641.28
#Mann=3,-1,0
  4402.0    0.05       0  4960.2   0.033       0  4964.2    0.05       0
Bank Sta=4960.2,4964.2
Exp/Cntr=0.3,0.1

Type RM Length L Ch R = 1,3005,285,285,285
BEGIN DESCRIPTION:
Henrietta Creek Tributary 4 5.0
END DESCRIPTION:
XS GIS Cut Line= 3
      2339878.98      7048060.04      2340229.00      7047510.00
      2339529.02      7046910.01
#Sta/Elev= 30
  4348.2  640.76  4559.1  639.48  4752.9  636.10  4862.2  633.28  4898.6  631.34
  4913.8  632.60  4919.7  632.42  4929.0  629.62  4940.9  628.57  4948.2  626.92
  4948.5  626.42  4952.2  626.92  4956.1  628.92  4986.6  630.22  4992.5  629.65
  4997.2  630.69  5035.8  631.10  5042.4  629.00  5050.1  629.00  5056.7  630.77
  5142.3  632.28  5304.7  633.64  5482.5  638.62  5553.3  638.66  5560.5  638.04
  5589.0  638.98  5716.3  638.50  5751.4  640.01  5822.8  639.69  5922.1  640.93
#Mann=3,-1,0
  4348.2    0.05       0  4948.2   0.033       0  4952.2    0.05       0
Bank Sta=4948.2,4952.2
Exp/Cntr=0.3,0.1

Type RM Length L Ch R = 1,2720,266,266,266
BEGIN DESCRIPTION:
Henrietta Creek Tributary 4 4.0
END DESCRIPTION:
XS GIS Cut Line= 3
      2340329.01      7047809.98      2340479.00      7047410.00
      2340179.03      7047110.03
#Sta/Elev= 30
  4572.8  635.07  4711.6  632.91  4775.7  630.84  4819.3  631.43  4882.5  629.39
  4935.9  628.92  4946.6  629.28  4954.6  628.33  4959.9  628.93  4967.9  627.85
  4978.6  627.05  4990.2  627.65  4997.3  624.61  5014.1  624.91  5026.3  623.79
  5026.5  623.29  5030.0  623.29  5030.3  623.79  5042.4  623.80  5056.5  628.50
  5070.7  628.92  5099.0  628.91  5127.3  629.84  5155.5  627.77  5169.7  627.78
  5198.0  629.51  5240.4  630.40  5254.5  631.80  5297.0  632.05  5424.2  635.14
#Mann=3,-1,0
  4572.8    0.05       0  5026.3   0.033       0  5030.3    0.05       0
Bank Sta=5026.3,5030.3
Exp/Cntr=0.3,0.1

Type RM Length L Ch R = 1,2454,283,283,283
BEGIN DESCRIPTION:
Henrietta Creek Tributary 4 3.0
END DESCRIPTION:
XS GIS Cut Line= 3
      2340629.02      7047609.96      2340729.00      7047360.00
      2340344.46      7046838.58
#Sta/Elev= 30
  4730.8  630.16  4907.1  628.11  4931.4  625.62  4985.2  623.47  4990.6  624.01
  4997.3  619.87  5003.1  619.87  5005.3  618.53  5005.6  618.03  5009.3  618.53
  5028.2  619.18  5036.6  624.96  5042.8  623.18  5049.7  625.23  5092.9  626.45
  5107.6  625.58  5113.8  626.75  5122.2  624.92  5128.4  625.83  5143.1  623.83
  5149.3  624.52  5163.9  623.20  5172.3  626.53  5186.4  627.24  5285.8  627.75
  5422.5  630.26  5450.0  630.99  5464.7  632.91  5479.3  631.78  5647.9  631.07
#Mann=3,-1,0
  4730.8    0.05       0  5005.3   0.035       0  5009.3    0.05       0
Bank Sta=5005.3,5009.3
Exp/Cntr=0.3,0.1

Type RM Length L Ch R = 1,2171,255,255,255
BEGIN DESCRIPTION:
Henrietta Creek Tributary 4 2.0
END DESCRIPTION:
XS GIS Cut Line= 3
      2340729.00      7048059.99      2340979.00      7047260.00
      2340566.11      7046888.44
#Sta/Elev= 30
  4156.9  633.38  4238.1  631.86  4275.8  632.59  4314.0  630.98  4418.8  629.41
  4701.7  628.72  4722.6  627.78  4946.3  623.69  4978.8  620.74  4984.6  623.12
  4998.4  623.23  5002.1  622.39  5014.3  616.79  5014.6  616.29  5018.3  616.79
  5023.1  622.89  5030.5  623.29  5094.1  623.05  5101.5  622.43  5108.3  620.76
  5115.7  621.28  5129.6  624.36  5157.6  623.37  5186.0  623.43  5236.1  624.80
  5257.0  624.56  5342.2  626.44  5370.6  625.90  5426.7  627.48  5550.5  629.19
#Mann=3,-1,0
  4156.9    0.05       0  5014.3   0.033       0  5018.3    0.05       0
Bank Sta=5014.3,5018.3
Exp/Cntr=0.3,0.1

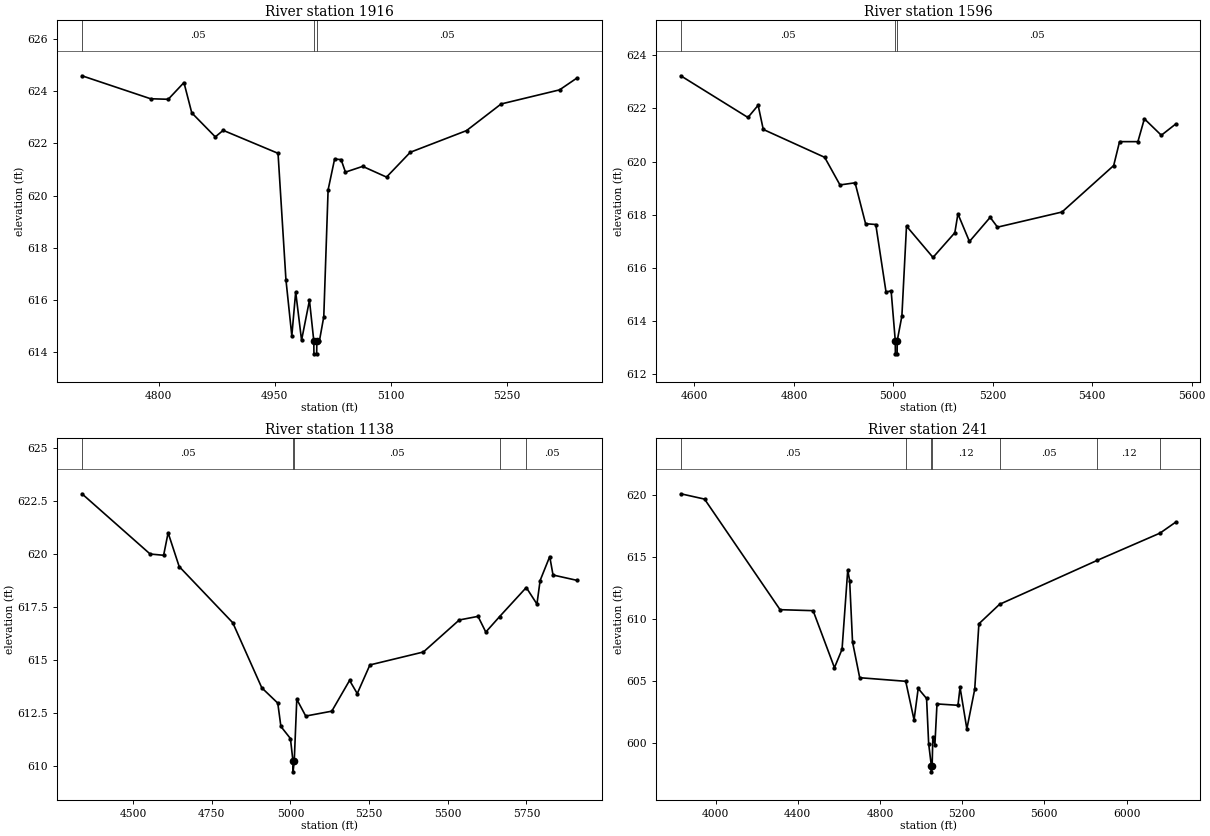
Type RM Length L Ch R = 1,1916,320,320,320
BEGIN DESCRIPTION:
Henrietta Creek Tributary 4 1.0
END DESCRIPTION:
XS GIS Cut Line= 3
      2341129.00      7047409.98      2341179.00      7047110.00
      2340879.03      7046960.01
#Sta/Elev= 30
  4700.9  624.59  4789.6  623.71  4812.4  623.69  4832.7  624.33  4842.8  623.17
  4873.2  622.25  4883.4  622.50  4954.3  621.62  4964.5  616.78  4972.1  614.63
  4977.1  616.31  4984.7  614.46  4994.9  615.99  5000.5  614.44  5000.7  613.94
  5004.2  613.94  5004.5  614.44  5007.8  614.44  5013.4  615.36  5019.0  620.22
  5027.4  621.40  5035.8  621.38  5041.4  620.90  5063.7  621.12  5094.5  620.71
  5125.2  621.66  5197.9  622.49  5242.6  623.51  5318.1  624.05  5340.4  624.50
#Mann=3,-1,0
  4700.9    0.05       0  5000.5   0.033       0  5004.5    0.05       0
Bank Sta=5000.5,5004.5
Exp/Cntr=0.3,0.1

Type RM Length L Ch R = 1,1596,458,458,458
BEGIN DESCRIPTION:
Henrietta Creek Tributary 4 0.5
END DESCRIPTION:
XS GIS Cut Line= 4
      2341380.64      7047481.28      2341497.00      7046999.24
      2341286.43      7046711.10      2341147.93      7046677.86
#Sta/Elev= 30
  4572.5  623.23  4707.6  621.66  4728.1  622.12  4738.4  621.21  4861.9  620.16
  4892.7  619.12  4923.1  619.20  4944.2  617.66  4964.7  617.63  4985.3  615.09
  4995.6  615.13  5003.9  613.26  5004.1  612.76  5007.6  612.76  5007.9  613.26
  5017.2  614.18  5026.5  617.57  5079.8  616.39  5123.7  617.32  5129.9  618.03
  5153.1  616.99  5194.8  617.90  5209.5  617.53  5339.2  618.10  5443.2  619.85
  5455.0  620.75  5491.9  620.75  5504.9  621.61  5539.0  620.99  5567.7  621.41
#Mann=3,-1,0
  4572.5    0.05       0  5003.9   0.033       0  5007.9    0.05       0
Bank Sta=5003.9,5007.9
Exp/Cntr=0.3,0.1

Type RM Length L Ch R = 1,1138,897,897,897
BEGIN DESCRIPTION:
Henrietta Creek Tributary 4 0.3
END DESCRIPTION:
XS GIS Cut Line= 4
      2341447.09      7047503.52      2341918.12      7047104.52
      2341868.25      7046766.51      2341264.24      7046661.23
#Sta/Elev= 30
  4337.7  622.82  4554.2  619.98  4597.1  619.92  4611.4  620.98  4646.5  619.39
  4816.8  616.74  4909.1  613.67  4959.8  612.95  4969.7  611.85  5000.0  611.28
  5008.1  610.21  5008.4  609.71  5012.1  610.21  5020.2  613.13  5048.6  612.34
  5131.4  612.57  5187.9  614.02  5212.3  613.40  5252.5  614.75  5422.4  615.36
  5536.4  616.87  5596.0  617.04  5620.7  616.30  5664.6  617.03  5749.3  618.40
  5783.2  617.62  5793.3  618.73  5823.8  619.86  5834.3  618.99  5909.8  618.74
#Mann=5,-1,0
  4337.7    0.05       0  5008.1   0.033       0  5012.1    0.05       0
  5664.6    0.12       0  5749.3    0.05       0
Bank Sta=5008.1,5012.1
Exp/Cntr=0.3,0.1

Type RM Length L Ch R = 1,241,0,0,0
BEGIN DESCRIPTION:
Henrietta Creek Tributary 4 0.2
END DESCRIPTION:
XS GIS Cut Line= 6
      2341668.32      7047388.66      2342307.19      7047027.56
      2342501.64      7046701.17      2342473.86      7046534.50
      2341834.97      7046659.50      2341363.41      7046610.96
#Sta/Elev= 30
  3830.8  620.13  3946.5  619.70  4314.0  610.76  4474.8  610.68  4578.6  606.07
  4615.6  607.56  4643.3  613.96  4652.6  613.10  4666.6  608.15  4701.5  605.26
  4925.4  604.97  4966.0  601.85  4986.1  604.39  5026.9  603.58  5037.0  599.93
  5050.0  598.15  5050.3  597.65  5054.0  598.15  5057.3  600.43  5067.4  599.86
  5077.6  603.14  5179.6  603.03  5189.8  604.48  5222.9  601.12  5261.2  604.33
  5281.5  609.62  5381.8  611.19  5857.7  614.75  6162.9  616.95  6238.6  617.83
#Mann=7,-1,0
  3830.8    0.05       0  4925.4    0.12       0  5050.0    0.07       0
  5054.0    0.12       0  5381.8    0.05       0  5857.7    0.12       0
  6162.9    0.05       0
Bank Sta=5050,5054
Exp/Cntr=0.3,0.1

Chan Stop Cuts=-1