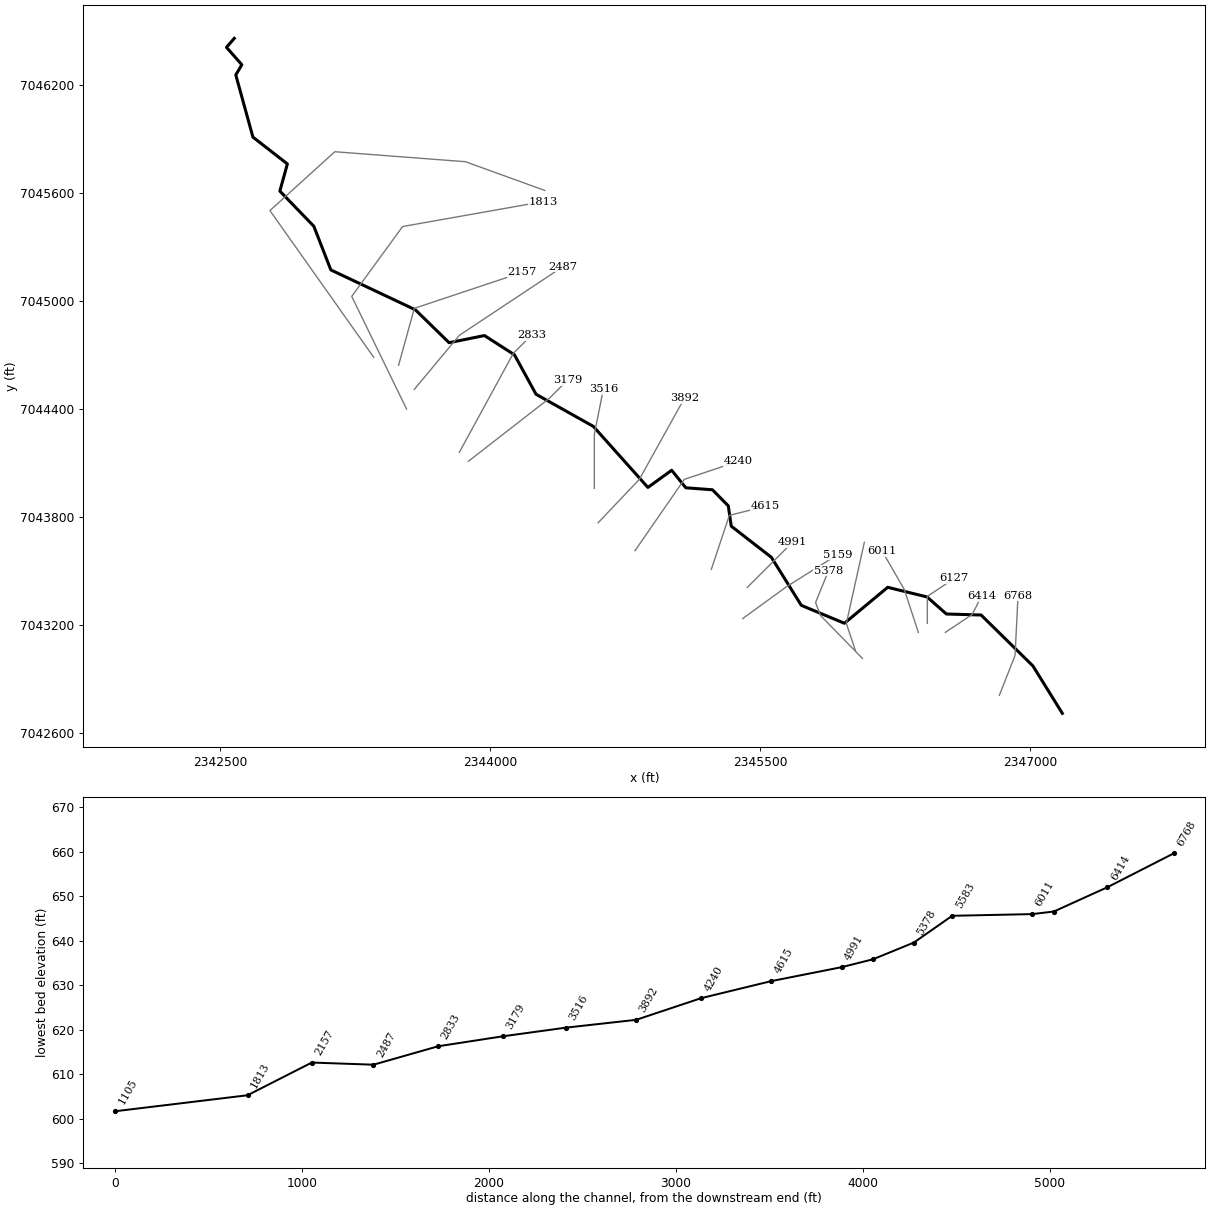
--- Henrietta Creek Tributary 5.prj (project) ---

Proj Title=Henrietta Creek Tributary 5 Base Level Engineering
Current Plan=p01
Default Exp/Contr=0.3,0.1
English Units
Geom File=g01
Flow File=f01
Plan File=p01
Y Axis Title=Elevation
X Axis Title(PF)=Main Channel Distance
X Axis Title(XS)=Station
BEGIN DESCRIPTION:
Henrietta Creek Tributary 5
END DESCRIPTION:
DSS Export Rating Curves= 0
DSS Export Rating Curve Sorted= 0
DSS Export Volume Flow Curves= 0
DXF OffsetX= 0
DXF OffsetY= 0
DXF ScaleX= 1
DXF ScaleY= 10

--- Henrietta Creek Tributary 5.p01 (plan) ---

Plan Title=Multiple Run
Program Version=4.10
Short Identifier=Multiple
Geom File=g01
Flow File=f01
Subcritical Flow
K Sum by GR= 0
Std Step Tol= 0.01
Critical Tol= 0.01
Num of Std Step Trials= 20
Max Error Tol= 0.3
Flow Tol Ratio= 0.001
Split Flow NTrial= 30
Split Flow Tol= 0.02
Split Flow Ratio= 0.02
Log Output Level= 0
Friction Slope Method= 0
Unsteady Friction Slope Method= 2
Unsteady Bridges Friction Slope Method= 1
Parabolic Critical Depth
Global Vel Dist= 1 , 1 , 1
Global Log Level= 0
CheckData=True
Encroach Param=-1 ,0,0, 0
BEGIN DESCRIPTION:
Multiple Run
END DESCRIPTION:
Computation Interval=1HOUR
Output Interval=1HOUR
Run HTab= 0
Run UNet= 0
Run PostProcess= 0
Run WQNet= 0
UNET Theta= 1
UNET Theta Warmup= 1
UNET ZTol= 0.02
UNET ZSATol= 0.05
UNET MxIter= 20
UNET MaxInSteps= 0
UNET DtIC= 0
UNET DtMin= 0
UNET MaxCRTS= 20
UNET WFStab= 2
UNET SFStab= 1
UNET WFX= 1
UNET SFX= 1
UNET DSS MLevel= 4
UNET DZMax Abort= 100
UNET Convert EG Bridges= 0
UNET Use Existing IB Tables=-1
UNET Froude Reduction=False
UNET Froude Limit= 1
UNET Froude Power= 10
UNET Time Slicing=0,0, 5
UNET Junction Losses=0
Instantaneous Interval=1HOUR
Write IC File= 0
Write IC File at Sim End=0
Echo Input=False
Echo Parameters=False
Echo Output=False
Write Detailed= 0
WQ AD Non Conservative
WQ ULTIMATE=-1
WQ Max Comp Step=1HOUR
WQ Output Interval=15MIN
WQ Output Selected Increments= 0
WQ Output face flow=0
WQ Output face velocity=0
WQ Output face area=0
WQ Output face dispersion=0
WQ Output cell volume=0
WQ Output cell surface area=0
WQ Output cell continuity=0
WQ Output cumulative cell continuity=0
WQ Output face conc=0
WQ Output face dconc_dx=0
WQ Output face courant=0
WQ Output face peclet=0
WQ Output face adv mass=0
WQ Output face disp mass=0
WQ Output cell mass=0
WQ Output cell source sink temp=0
WQ Output cell source sink nsm=0
WQ Output MaxMinRange=-1
WQ Daily Max Min Mean=-1
WQ Daily Range=0
WQ Daily Time=0
WQ Create Restart=0
WQ Fixed Restart=0
WQ System Summary=0
WQ Use Fixed Temperature=0
Sorting and Armoring Iterations= 10
XS Update Threshold= 0.02
Hydraulics Update Threshold= 0.02
Energy Slope Method= 1
Volume Change Method= 0
XS Weighting Method= 0
Number of US Weighted Cross Sections= 1
Number of DS Weighted Cross Sections= 1
Upstream XS Weight=0.25
Main XS Weight=0.5
Downstream XS Weight=0.25
Number of DS XS's Weighted with US Boundary= 1
Upstream Boundary Weight= 1
Weight of XSs Associated with US Boundary= 0
Number of US XS's Weighted with DS Boundary= 1
Downstream Boundary Weight= 0.5
Weight of XSs Associated with DS Boundary= 0.5
Sediment Output Level= 4
Mass or Volume Output= 0
Output Increment Type= 1
Profile and TS Output Increment= 10
XS Output Flag= 0
XS Output Increment= 10
Disregard all LS=0
Disregard all Conn=0
Disregard all Breaches=0
Disregard all Pumps=0

--- Henrietta Creek Tributary 5.f01 (steady flow) ---

Flow Title=Multiple
Number of Profiles=7
Profile Names=10-year,25-year,50-year,1pct_min,100-year,1pct_plu,500-year
River Rch & RM= Henrietta Creek ,Reach-1,6768
     281     363     428     251     501     999     683
River Rch & RM= Henrietta Creek ,Reach-1,6011
     488     658     796     479     956    1910    1370
River Rch & RM= Henrietta Creek ,Reach-1,5159
     774    1070    1320     805    1610    3210    2380
Boundary for River Rch & Prof#=Henrietta Creek ,Reach-1,1
Up Type=0
Dn Type=3
Dn Slope=0.005
Boundary for River Rch & Prof#=Henrietta Creek ,Reach-1,2
Up Type=0
Dn Type=3
Dn Slope=0.005
Boundary for River Rch & Prof#=Henrietta Creek ,Reach-1,3
Up Type=0
Dn Type=3
Dn Slope=0.005
Boundary for River Rch & Prof#=Henrietta Creek ,Reach-1,4
Up Type=0
Dn Type=3
Dn Slope=0.005
Boundary for River Rch & Prof#=Henrietta Creek ,Reach-1,5
Up Type=0
Dn Type=3
Dn Slope=0.005
Boundary for River Rch & Prof#=Henrietta Creek ,Reach-1,6
Up Type=0
Dn Type=3
Dn Slope=0.005
Boundary for River Rch & Prof#=Henrietta Creek ,Reach-1,7
Up Type=0
Dn Type=3
Dn Slope=0.005

--- Henrietta Creek Tributary 5.g01 (geometry) ---

Geom Title=Existing Conditions

River Reach=Henrietta Creek ,Reach-1
Reach XY= 30
      2347179.00      7042710.00      2347015.51      7042973.56
      2346727.54      7043256.46      2346534.85      7043262.06
      2346427.64      7043356.71      2346208.79      7043410.38
      2345968.36      7043210.55      2345729.00      7043310.00
      2345562.51      7043577.05      2345339.52      7043750.21
      2345323.48      7043862.44      2345235.20      7043952.19
      2345087.31      7043963.11      2345008.68      7044060.60
      2344876.72      7043965.05      2344573.38      7044304.38
      2344255.16      7044482.85      2344135.33      7044701.96
      2343968.56      7044808.96      2343772.26      7044769.13
      2343585.06      7044951.86      2343115.37      7045173.45
      2343020.84      7045416.05      2342832.07      7045611.43
      2342873.91      7045762.31      2342682.45      7045911.25
      2342587.28      7046256.78      2342620.99      7046313.34
      2342535.61      7046410.00      2342579.00      7046460.00

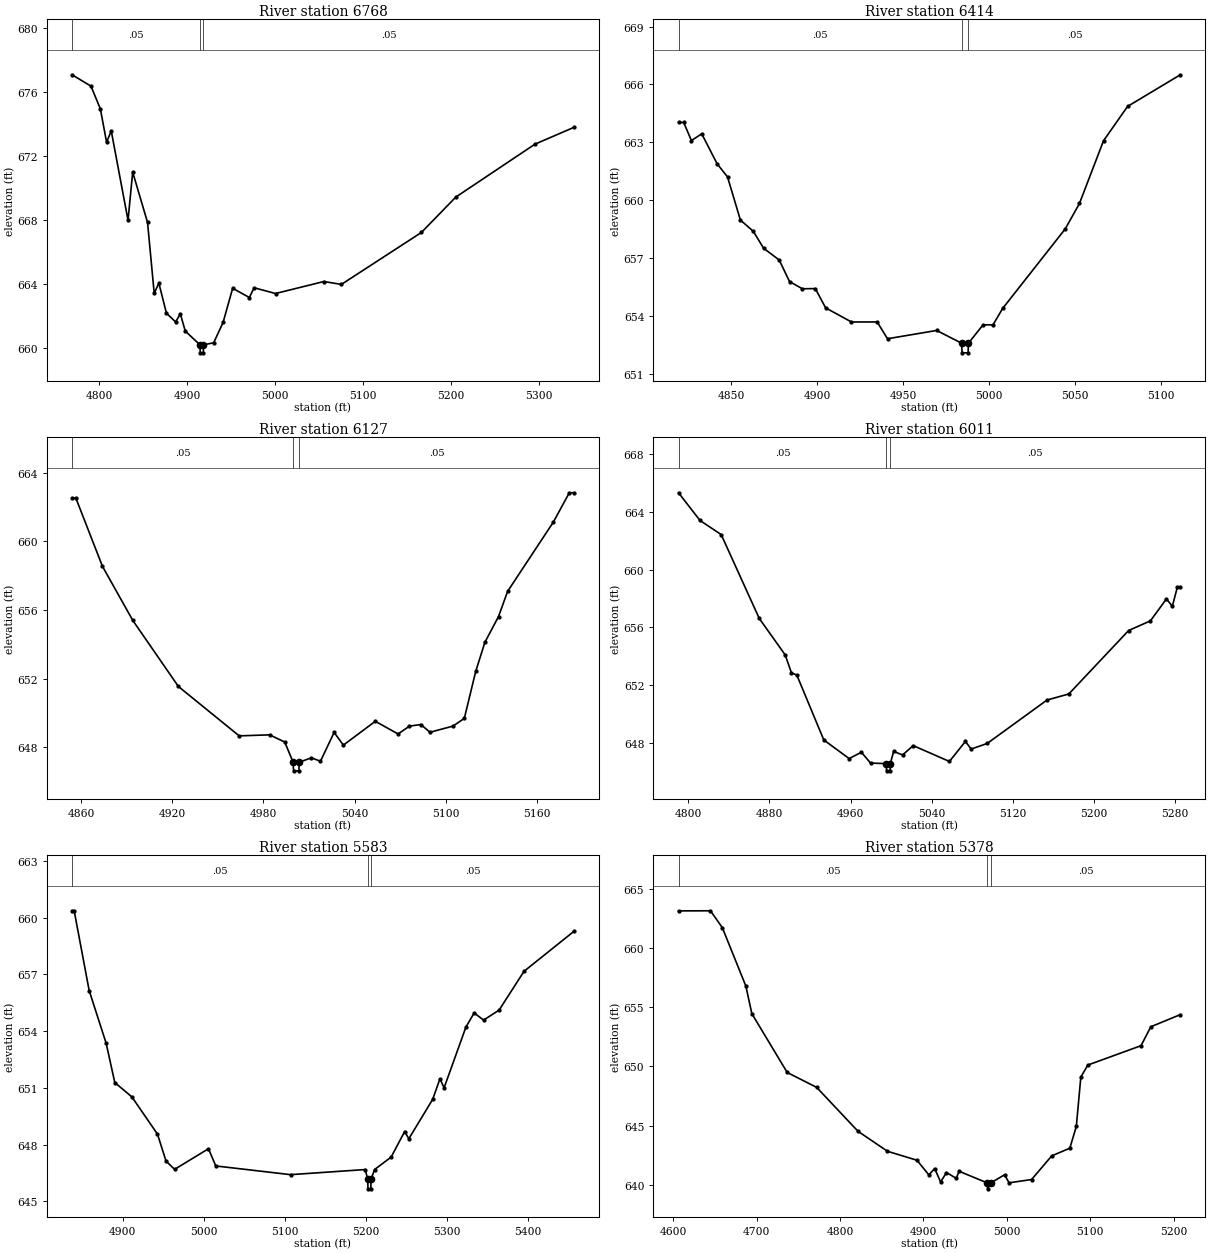
Type RM Length L Ch R = 1,6768,354,354,354
BEGIN DESCRIPTION:
Henrietta Creek Tributary 5 15.0
END DESCRIPTION:
XS GIS Cut Line= 3
      2346829.01      7042810.03      2346916.24      7043031.78
      2346932.86      7043364.27
#Sta/Elev= 30
  4768.9  677.07  4790.4  676.36  4801.1  674.94  4808.2  672.85  4813.5  673.56
  4832.6  667.97  4837.9  670.98  4854.8  667.84  4862.4  663.40  4867.7  664.04
  4876.3  662.16  4886.8  661.61  4892.1  662.12  4897.8  661.04  4914.5  660.18
  4914.8  659.68  4918.3  659.68  4918.5  660.18  4930.1  660.31  4940.8  661.58
  4951.7  663.72  4970.7  663.14  4976.1  663.75  5000.5  663.39  5055.5  664.14
  5075.5  663.96  5166.6  667.21  5205.7  669.42  5295.8  672.73  5340.1  673.78
#Mann=3,-1,0
  4768.9    0.05       0  4914.5   0.033       0  4918.5    0.05       0
Bank Sta=4914.5,4918.5
Exp/Cntr=0.3,0.1

Type RM Length L Ch R = 1,6414,287,287,287
BEGIN DESCRIPTION:
Henrietta Creek Tributary 5 14.0
END DESCRIPTION:
XS GIS Cut Line= 3
      2346529.03      7043160.02      2346679.00      7043260.00
      2346728.98      7043359.96
#Sta/Elev= 30
  4819.3  664.03  4822.3  664.03  4826.8  663.09  4832.8  663.44  4841.8  661.88
  4847.8  661.21  4855.3  658.97  4862.8  658.39  4868.8  657.51  4877.9  656.90
  4883.9  655.78  4891.4  655.41  4898.9  655.42  4904.9  654.42  4919.9  653.69
  4934.9  653.69  4940.9  652.82  4969.5  653.25  4984.0  652.59  4984.3  652.09
  4987.8  652.09  4988.0  652.59  4996.5  653.54  5002.3  653.54  5007.9  654.39
  5044.3  658.51  5052.6  659.83  5066.6  663.08  5080.6  664.86  5111.3  666.50
#Mann=3,-1,0
  4819.3    0.05       0  4984.0   0.033       0  4988.0    0.05       0
Bank Sta=4984,4988
Exp/Cntr=0.3,0.1

Type RM Length L Ch R = 1,6127,116,116,116
BEGIN DESCRIPTION:
Henrietta Creek Tributary 5 13.0
END DESCRIPTION:
XS GIS Cut Line= 3
      2346429.00      7043209.99      2346429.00      7043360.00
      2346579.01      7043460.01
#Sta/Elev= 30
  4854.0  662.53  4856.5  662.53  4874.0  658.55  4894.0  655.39  4924.0  651.54
  4964.0  648.66  4984.0  648.72  4994.0  648.30  4999.5  647.12  4999.8  646.62
  5003.3  646.62  5003.5  647.12  5011.5  647.38  5017.5  647.18  5026.5  648.86
  5032.6  648.12  5053.6  649.51  5068.6  648.77  5076.1  649.23  5083.6  649.32
  5089.6  648.87  5104.7  649.23  5112.2  649.68  5119.7  652.42  5125.7  654.11
  5134.7  655.62  5140.7  657.09  5170.8  661.13  5181.3  662.84  5184.3  662.84
#Mann=3,-1,0
  4854.0    0.05       0  4999.5   0.033       0  5003.5    0.05       0
Bank Sta=4999.5,5003.5
Exp/Cntr=0.3,0.1

Type RM Length L Ch R = 1,6011,428,428,428
BEGIN DESCRIPTION:
Henrietta Creek Tributary 5 12.0
END DESCRIPTION:
XS GIS Cut Line= 3
      2346378.99      7043160.03      2346301.17      7043397.50
      2346179.01      7043609.99
#Sta/Elev= 30
  4790.3  665.32  4811.5  663.40  4832.4  662.42  4869.9  656.61  4895.5  654.08
  4901.7  652.83  4907.0  652.68  4933.6  648.18  4958.6  646.89  4970.7  647.33
  4979.7  646.58  4995.2  646.54  4995.5  646.04  4999.0  646.04  4999.2  646.54
  5002.5  647.39  5011.3  647.14  5021.8  647.79  5057.5  646.69  5073.3  648.08
  5079.0  647.55  5094.8  647.94  5153.8  650.95  5175.3  651.37  5234.3  655.77
  5255.8  656.44  5271.6  657.96  5277.4  657.45  5282.4  658.78  5285.3  658.78
#Mann=3,-1,0
  4790.3    0.05       0  4995.2   0.033       0  4999.2    0.05       0
Bank Sta=4995.2,4999.2
Exp/Cntr=0.3,0.1

Type RM Length L Ch R = 1,5583,205,205,205
BEGIN DESCRIPTION:
Henrietta Creek Tributary 5 11.0
END DESCRIPTION:
XS GIS Cut Line= 3
      2346028.99      7043060.03      2345979.00      7043210.00
      2346079.01      7043660.04
#Sta/Elev= 30
  4837.4  660.36  4840.0  660.36  4858.5  656.14  4879.5  653.35  4890.1  651.28
  4911.2  650.52  4942.8  648.55  4953.3  647.13  4963.9  646.69  5005.7  647.78
  5014.7  646.87  5106.9  646.41  5199.1  646.68  5202.2  646.16  5202.5  645.66
  5206.0  645.66  5206.2  646.16  5210.6  646.68  5231.1  647.34  5247.7  648.69
  5252.9  648.31  5282.3  650.39  5291.3  651.48  5296.4  651.00  5323.3  654.21
  5333.5  654.96  5345.1  654.58  5364.3  655.11  5395.0  657.16  5456.5  659.27
#Mann=3,-1,0
  4837.4    0.05       0  5202.2   0.033       0  5206.2    0.05       0
Bank Sta=5202.2,5206.2
Exp/Cntr=0.3,0.1

Type RM Length L Ch R = 1,5378,219,219,219
BEGIN DESCRIPTION:
Henrietta Creek Tributary 5 10.5
END DESCRIPTION:
XS GIS Cut Line= 4
      2346068.42      7043015.19      2345835.71      7043253.43
      2345808.01      7043325.46      2345880.04      7043502.78
#Sta/Elev= 30
  4606.5  663.17  4644.8  663.18  4659.0  661.75  4687.2  656.81  4694.4  654.47
  4736.8  649.49  4772.1  648.23  4821.7  644.51  4857.0  642.82  4892.4  642.06
  4906.6  640.82  4913.6  641.36  4920.7  640.22  4927.7  641.02  4939.5  640.53
  4942.8  641.13  4976.7  640.14  4977.0  639.64  4980.7  640.14  4997.4  640.83
  5002.8  640.15  5029.8  640.43  5053.9  642.43  5075.6  643.08  5083.4  644.92
  5088.8  649.10  5097.2  650.12  5161.0  651.76  5172.7  653.36  5208.1  654.39
#Mann=3,-1,0
  4606.5    0.05       0  4976.7   0.033       0  4980.7    0.05       0
Bank Sta=4976.7,4980.7
Exp/Cntr=0.3,0.1

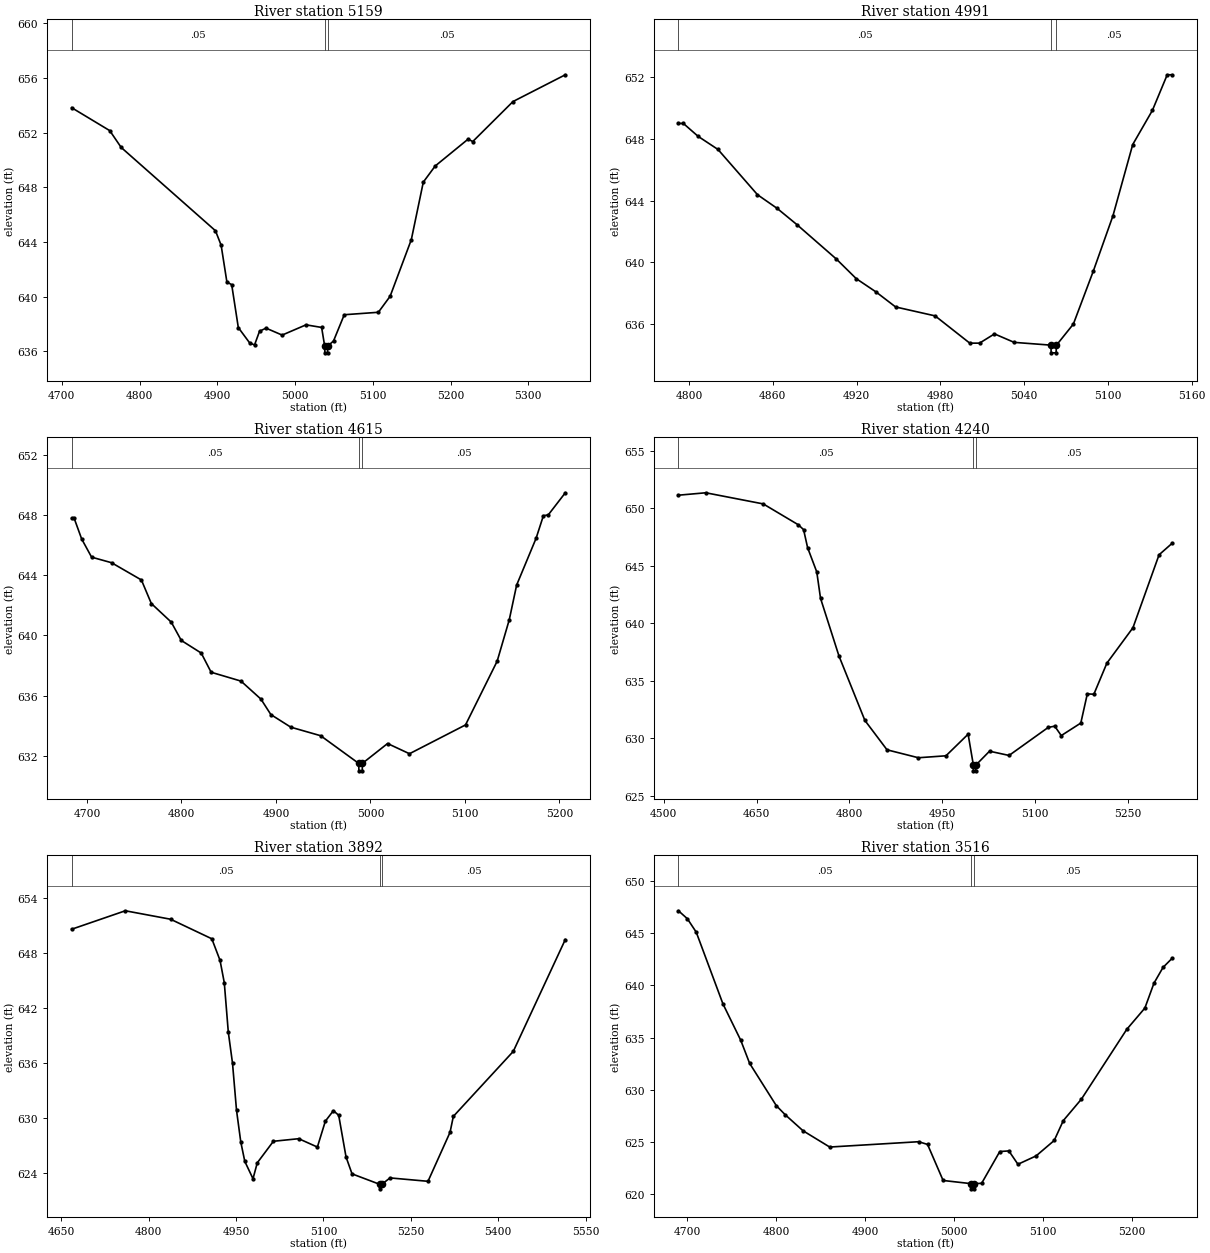
Type RM Length L Ch R = 1,5159,168,168,168
BEGIN DESCRIPTION:
Henrietta Creek Tributary 5 10.0
END DESCRIPTION:
XS GIS Cut Line= 3
      2345403.49      7043236.80      2345647.31      7043414.12
      2345929.90      7043591.43
#Sta/Elev= 30
  4712.6  653.83  4761.6  652.15  4776.3  650.92  4897.6  644.82  4904.9  643.76
  4912.3  641.07  4918.5  640.87  4927.0  637.73  4941.7  636.60  4947.9  636.46
  4954.3  637.46  4962.6  637.69  4983.4  637.18  5014.1  637.93  5034.2  637.74
  5038.1  636.38  5038.3  635.88  5041.8  635.88  5042.1  636.38  5049.5  636.75
  5063.3  638.67  5107.2  638.85  5122.3  640.02  5149.6  644.17  5165.0  648.38
  5180.3  649.56  5222.7  651.53  5228.6  651.35  5280.4  654.28  5347.7  656.24
#Mann=3,-1,0
  4712.6    0.05       0  5038.1   0.033       0  5042.1    0.05       0
Bank Sta=5038.1,5042.1
Exp/Cntr=0.3,0.1

Type RM Length L Ch R = 1,4991,376,376,376
BEGIN DESCRIPTION:
Henrietta Creek Tributary 5 9.0
END DESCRIPTION:
XS GIS Cut Line= 3
      2345429.01      7043410.01      2345579.00      7043560.00
      2345678.98      7043659.98
#Sta/Elev= 27
  4792.5  649.01  4796.0  649.01  4806.6  648.17  4820.8  647.32  4849.1  644.38
  4863.2  643.49  4877.3  642.44  4905.6  640.20  4919.8  638.93  4933.9  638.07
  4948.0  637.09  4976.3  636.51  5001.1  634.74  5008.1  634.74  5018.8  635.34
  5032.9  634.79  5059.2  634.61  5059.4  634.11  5062.9  634.11  5063.2  634.61
  5075.3  635.98  5089.5  639.40  5103.6  643.00  5117.8  647.64  5131.9  649.86
  5142.5  652.17  5146.0  652.17
#Mann=3,-1,0
  4792.5    0.05       0  5059.2   0.033       0  5063.2    0.05       0
Bank Sta=5059.2,5063.2
Exp/Cntr=0.3,0.1

Type RM Length L Ch R = 1,4615,375,375,375
BEGIN DESCRIPTION:
Henrietta Creek Tributary 5 8.0
END DESCRIPTION:
XS GIS Cut Line= 3
      2345228.99      7043509.98      2345329.00      7043810.00
      2345529.00      7043860.00
#Sta/Elev= 30
  4683.8  647.80  4686.5  647.80  4694.4  646.43  4704.9  645.22  4726.0  644.85
  4757.6  643.70  4768.1  642.13  4789.2  640.89  4799.8  639.67  4820.9  638.83
  4831.4  637.55  4863.0  636.96  4884.1  635.76  4894.6  634.73  4915.7  633.89
  4947.3  633.32  4987.5  631.48  4987.8  630.98  4991.3  630.98  4991.5  631.48
  5018.1  632.80  5041.3  632.12  5100.6  634.04  5134.1  638.29  5146.9  641.05
  5154.7  643.36  5175.3  646.48  5183.0  647.98  5188.2  648.04  5206.2  649.51
#Mann=3,-1,0
  4683.8    0.05       0  4987.5   0.033       0  4991.5    0.05       0
Bank Sta=4987.5,4991.5
Exp/Cntr=0.3,0.1

Type RM Length L Ch R = 1,4240,348,348,348
BEGIN DESCRIPTION:
Henrietta Creek Tributary 5 7.0
END DESCRIPTION:
XS GIS Cut Line= 3
      2344805.07      7043613.61      2345079.00      7044010.00
      2345379.04      7044110.01
#Sta/Elev= 30
  4523.8  651.15  4568.0  651.36  4660.9  650.39  4717.7  648.57  4726.1  648.15
  4732.6  646.58  4747.4  644.47  4753.5  642.17  4783.3  637.15  4825.2  631.54
  4861.0  628.98  4911.7  628.29  4956.3  628.46  4992.1  630.34  5000.6  627.65
  5000.8  627.15  5004.3  627.15  5004.6  627.65  5026.7  628.86  5058.3  628.49
  5121.6  630.93  5132.1  631.04  5142.7  630.22  5174.3  631.31  5184.8  633.85
  5195.4  633.82  5216.5  636.53  5258.6  639.61  5300.8  645.96  5321.9  646.96
#Mann=3,-1,0
  4523.8    0.05       0  5000.6   0.033       0  5004.6    0.05       0
Bank Sta=5000.6,5004.6
Exp/Cntr=0.3,0.1

Type RM Length L Ch R = 1,3892,376,376,376
BEGIN DESCRIPTION:
Henrietta Creek Tributary 5 6.0
END DESCRIPTION:
XS GIS Cut Line= 3
      2344600.06      7043768.77      2344829.00      7044010.00
      2345079.02      7044460.04
#Sta/Elev= 30
  4667.9  650.55  4760.0  652.56  4837.7  651.64  4908.5  649.51  4922.6  647.16
  4929.9  644.73  4936.8  639.34  4944.0  635.97  4950.9  630.83  4958.2  627.39
  4965.1  625.27  4979.2  623.38  4986.5  625.11  5014.2  627.46  5057.7  627.74
  5089.7  626.83  5103.4  629.65  5117.2  630.79  5126.3  630.29  5138.9  625.75
  5149.2  623.91  5196.4  622.78  5196.6  622.28  5200.4  622.78  5214.4  623.47
  5279.6  623.10  5317.4  628.43  5323.1  630.17  5426.0  637.25  5515.3  649.43
#Mann=3,-1,0
  4667.9    0.05       0  5196.4   0.033       0  5200.4    0.05       0
Bank Sta=5196.4,5200.4
Exp/Cntr=0.3,0.1

Type RM Length L Ch R = 1,3516,337,337,337
BEGIN DESCRIPTION:
Henrietta Creek Tributary 5 5.0
END DESCRIPTION:
XS GIS Cut Line= 3
      2344579.00      7043960.02      2344579.00      7044260.00
      2344628.99      7044509.97
#Sta/Elev= 30
  4690.0  647.13  4700.0  646.37  4710.0  645.08  4740.0  638.22  4760.0  634.74
  4770.0  632.53  4800.0  628.48  4810.0  627.61  4830.0  626.08  4860.0  624.52
  4960.0  625.03  4970.0  624.77  4987.5  621.32  5018.6  621.02  5018.8  620.52
  5022.3  620.52  5022.6  621.02  5030.8  621.05  5051.2  624.09  5061.4  624.15
  5071.6  622.87  5092.0  623.67  5112.4  625.15  5122.6  627.05  5143.0  629.11
  5193.9  635.78  5214.3  637.82  5224.5  640.20  5234.7  641.71  5244.9  642.58
#Mann=3,-1,0
  4690.0    0.05       0  5018.6   0.033       0  5022.6    0.05       0
Bank Sta=5018.6,5022.6
Exp/Cntr=0.3,0.1

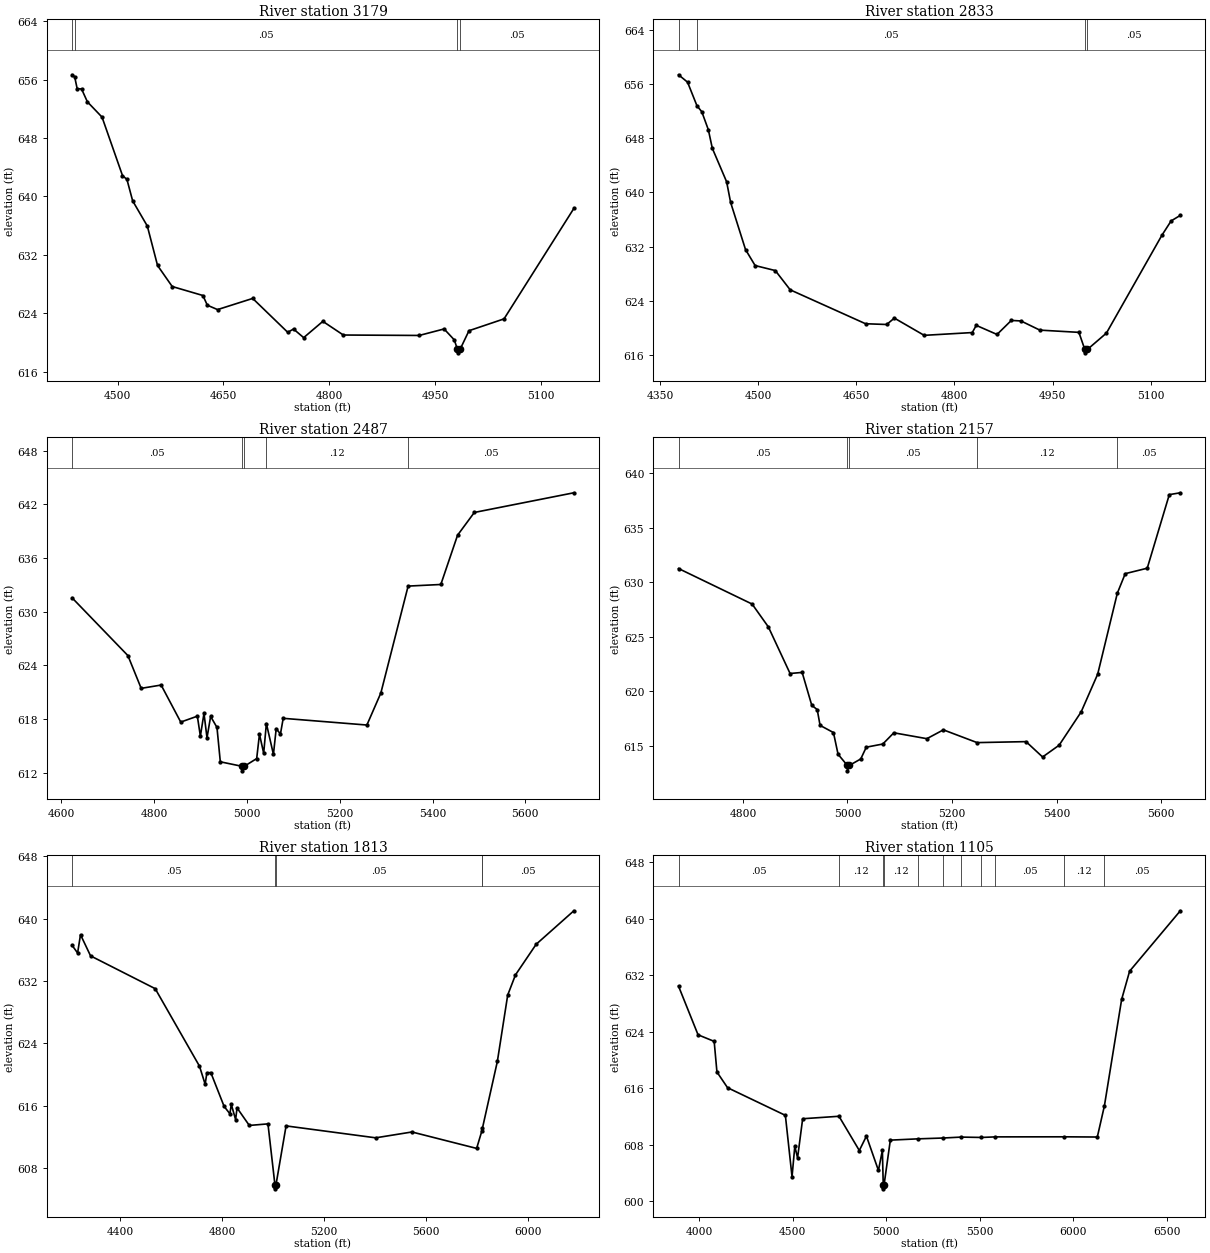
Type RM Length L Ch R = 1,3179,346,346,346
BEGIN DESCRIPTION:
Henrietta Creek Tributary 5 4.0
END DESCRIPTION:
XS GIS Cut Line= 3
      2343879.02      7044110.02      2344329.00      7044460.00
      2344429.02      7044560.02
#Sta/Elev= 30
  4435.4  656.65  4439.1  656.37  4442.6  654.76  4448.9  654.70  4457.1  652.95
  4477.9  650.85  4506.9  642.85  4513.2  642.32  4521.3  639.39  4542.1  635.94
  4556.6  630.54  4577.4  627.66  4620.9  626.43  4627.2  625.10  4641.7  624.50
  4691.5  626.03  4741.2  621.39  4749.4  621.84  4763.8  620.66  4791.0  622.89
  4820.0  621.02  4927.6  620.96  4962.9  621.85  4977.4  620.35  4981.7  619.08
  4982.0  618.58  4985.7  619.08  4998.2  621.61  5047.9  623.23  5146.9  638.35
#Mann=4,-1,0
  4435.4   0.075       0  4439.1    0.05       0  4981.7   0.033       0
  4985.7    0.05       0
Bank Sta=4981.7,4985.7
Exp/Cntr=0.3,0.1

Type RM Length L Ch R = 1,2833,346,346,346
BEGIN DESCRIPTION:
Henrietta Creek Tributary 5 3.0
END DESCRIPTION:
XS GIS Cut Line= 3
      2343828.99      7044159.99      2344129.00      7044710.00
      2344228.98      7044809.98
#Sta/Elev= 30
  4377.7  657.34  4391.5  656.25  4405.9  652.77  4413.3  651.89  4423.3  649.24
  4429.4  646.50  4451.3  641.56  4457.4  638.52  4480.2  631.57  4494.9  629.21
  4525.8  628.47  4548.6  625.63  4663.9  620.63  4696.2  620.52  4708.0  621.46
  4753.6  618.92  4827.2  619.33  4833.3  620.39  4865.1  619.05  4887.0  621.12
  4901.7  621.04  4930.6  619.69  4990.4  619.36  4999.4  616.84  4999.6  616.34
  5003.4  616.84  5032.5  619.25  5117.3  633.66  5131.5  635.79  5145.6  636.61
#Mann=4,-1,0
  4377.7   0.075       0  4405.9    0.05       0  4999.4   0.033       0
  5003.4    0.05       0
Bank Sta=4999.4,5003.4
Exp/Cntr=0.3,0.1

Type RM Length L Ch R = 1,2487,330,330,330
BEGIN DESCRIPTION:
Henrietta Creek Tributary 5 2.0
END DESCRIPTION:
XS GIS Cut Line= 3
      2343579.01      7044510.01      2343829.00      7044810.00
      2344405.08      7045192.15
#Sta/Elev= 30
  4622.9  631.54  4743.3  625.08  4771.9  621.42  4814.9  621.79  4857.2  617.65
  4893.0  618.31  4899.5  616.08  4907.3  618.62  4913.8  615.89  4921.6  618.28
  4935.3  617.05  4942.5  613.21  4989.9  612.70  4990.2  612.20  4993.9  612.70
  5020.9  613.57  5026.9  616.29  5036.0  614.17  5041.8  617.49  5057.0  614.04
  5063.0  616.92  5072.1  616.31  5078.1  618.07  5258.5  617.32  5288.6  620.90
  5347.4  632.85  5417.9  633.03  5454.0  638.54  5490.1  641.08  5704.7  643.28
#Mann=5,-1,0
  4622.9    0.05       0  4989.9   0.033       0  4993.9    0.05       0
  5041.8    0.12       0  5347.4    0.05       0
Bank Sta=4989.9,4993.9
Exp/Cntr=0.3,0.1

Type RM Length L Ch R = 1,2157,344,344,344
BEGIN DESCRIPTION:
Henrietta Creek Tributary 5 1.0
END DESCRIPTION:
XS GIS Cut Line= 3
      2343491.82      7044644.29      2343579.00      7044960.00
      2344179.01      7045160.00
#Sta/Elev= 30
  4676.8  631.24  4817.6  627.98  4848.7  625.88  4890.2  621.61  4913.3  621.71
  4931.7  618.69  4942.1  618.30  4947.6  616.85  4973.2  616.19  4982.0  614.20
  4999.7  613.18  5000.0  612.68  5003.7  613.18  5025.4  613.77  5036.0  614.85
  5067.6  615.14  5088.7  616.17  5151.9  615.63  5183.5  616.44  5248.0  615.27
  5341.6  615.36  5373.3  613.95  5404.9  615.03  5447.0  618.08  5478.7  621.55
  5516.3  628.98  5531.4  630.77  5573.5  631.27  5615.7  638.02  5636.8  638.19
#Mann=5,-1,0
  4676.8    0.05       0  4999.7   0.033       0  5003.7    0.05       0
  5248.0    0.12       0  5516.3    0.05       0
Bank Sta=4999.7,5003.7
Exp/Cntr=0.3,0.1

Type RM Length L Ch R = 1,1813,708,708,708
BEGIN DESCRIPTION:
Henrietta Creek Tributary 5 0.5
END DESCRIPTION:
XS GIS Cut Line= 4
      2343536.14      7044400.45      2343231.38      7045026.60
      2343513.97      7045414.48      2344294.61      7045552.89
#Sta/Elev= 30
  4211.2  636.60  4232.9  635.61  4244.3  637.96  4283.8  635.24  4537.4  631.03
  4711.2  621.08  4733.4  618.76  4740.3  620.23  4755.7  620.25  4807.9  615.91
  4830.5  614.97  4836.1  616.16  4853.0  614.22  4858.6  615.72  4906.7  613.47
  4979.9  613.67  5007.3  605.83  5007.5  605.33  5011.3  605.83  5051.0  613.41
  5402.7  611.88  5544.9  612.63  5798.8  610.52  5819.6  612.80  5821.3  613.08
  5880.1  621.69  5920.7  630.21  5951.2  632.80  6032.4  636.73  6180.3  641.03
#Mann=5,-1,0
  4211.2    0.05       0  5007.3   0.033       0  5011.3    0.05       0
  5819.6    0.12       0  5821.3    0.05       0
Bank Sta=5007.3,5011.3
Exp/Cntr=0.3,0.1

Type RM Length L Ch R = 1,1105,0,0,0
BEGIN DESCRIPTION:
Henrietta Creek Tributary 5 0.3
END DESCRIPTION:
XS GIS Cut Line= 5
      2343353.29      7044688.57      2342777.00      7045503.13
      2343137.18      7045830.06      2343863.07      7045774.65
      2344303.77      7045614.89
#Sta/Elev= 30
  3890.2  630.45  3994.5  623.56  4080.6  622.63  4095.4  618.29  4152.0  616.07
  4461.0  612.15  4496.6  603.45  4511.4  607.77  4526.2  606.13  4553.4  611.67
  4747.4  612.02  4856.1  607.17  4894.1  609.21  4958.2  604.35  4979.3  607.18
  4984.0  602.24  4984.3  601.74  4988.0  602.24  5021.8  608.64  5168.0  608.82
  5304.2  608.94  5399.7  609.07  5508.8  609.02  5583.3  609.10  5951.7  609.11
  6127.7  609.08  6165.6  613.50  6257.7  628.58  6300.2  632.57  6571.2  641.13
#Mann=11,-1,0
  3890.2    0.05       0  4747.4    0.12       0  4984.0    0.07       0
  4988.0    0.12       0  5168.0    0.05       0  5304.2    0.12       0
  5399.7    0.05       0  5508.8    0.12       0  5583.3    0.05       0
  5951.7    0.12       0  6165.6    0.05       0
Bank Sta=4984,4988
Exp/Cntr=0.3,0.1

Chan Stop Cuts=-1