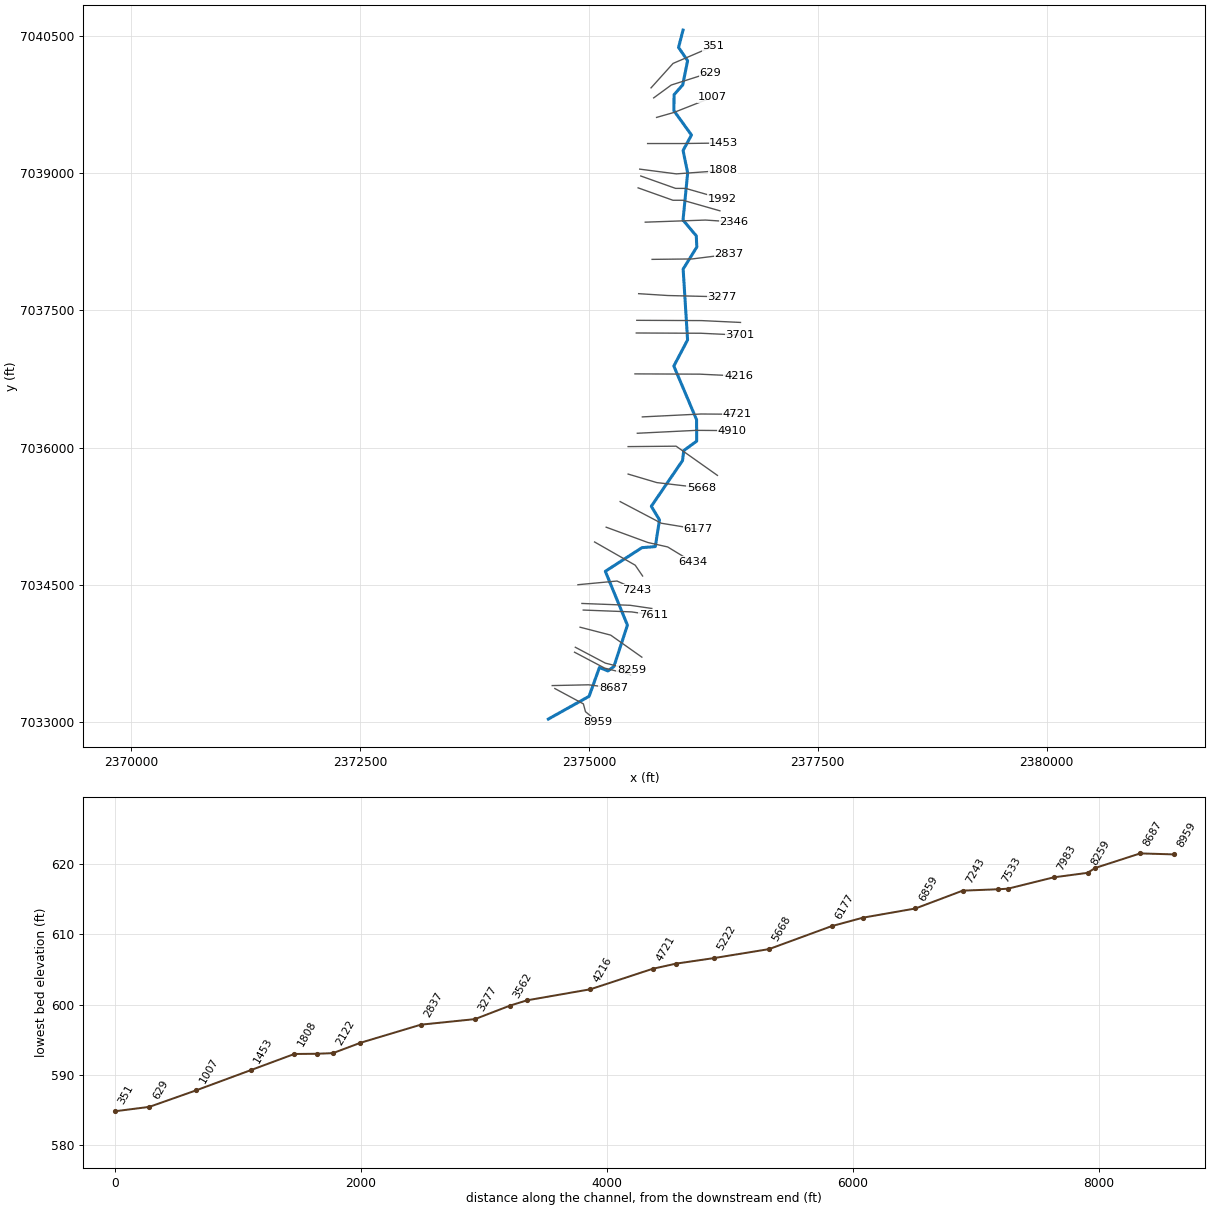
--- Higgins Branch.prj (project) ---

Proj Title=Higgins Branch Base Level Engineering
Current Plan=p01
Default Exp/Contr=0.3,0.1
English Units
Geom File=g01
Flow File=f01
Plan File=p01
BEGIN DESCRIPTION:
Higgins Branch
END DESCRIPTION:

--- Higgins Branch.p01 (plan) ---

Plan Title=Multiple Run
Short Identifier=Multiple
Geom File=g01
Flow File=f01
Subcritical Flow
K Sum by GR= 0
Std Step Tol= 0.01
Critical Tol= 0.01
Num of Std Step Trials= 20
Max Error Tol= 0.3
Flow Tol Ratio= 0.001
Split Flow NTrial= 30
Split Flow Tol= 0.02
Split Flow Ratio= 0.02
Log Output Level= 0
Friction Slope Method= 1
Unsteady Friction Slope Method= 2
Unsteady Bridges Friction Slope Method= 1
Parabolic Critical Depth
Global Vel Dist=  1 , 1 , 1
Global Log Level= 0
CheckData=True
Encroach Param= -1, 0, 0, 0
BEGIN DESCRIPTION:
Multiple Run
END DESCRIPTION:

--- Higgins Branch.f01 (steady flow) ---

Flow Title=Multiple
Number of Profiles=7
Profile Names=10-year,25-year,50-year,1pct_min,100-year,1pct_plu,500-year
River Rch & RM= Higgins Branch,Reach-1,8959
     711     977    1198     728    1452    2898    2134
River Rch & RM= Higgins Branch,Reach-1,6434
     870    1212    1499     918    1832    3656    2738
River Rch & RM= Higgins Branch,Reach-1,4910
    1105    1552    1928    1186    2366    4720    3562
River Rch & RM= Higgins Branch,Reach-1,1007
    1116    1567    1947    1197    2388    4765    3594
Boundary for River Rch & Prof#=Higgins Branch,Reach-1,1
Up Type=0
Dn Type=3
Dn Slope=0.005
Boundary for River Rch & Prof#=Higgins Branch,Reach-1,2
Up Type=0
Dn Type=3
Dn Slope=0.005
Boundary for River Rch & Prof#=Higgins Branch,Reach-1,3
Up Type=0
Dn Type=3
Dn Slope=0.005
Boundary for River Rch & Prof#=Higgins Branch,Reach-1,4
Up Type=0
Dn Type=3
Dn Slope=0.005
Boundary for River Rch & Prof#=Higgins Branch,Reach-1,5
Up Type=0
Dn Type=3
Dn Slope=0.005
Boundary for River Rch & Prof#=Higgins Branch,Reach-1,6
Up Type=0
Dn Type=3
Dn Slope=0.005
Boundary for River Rch & Prof#=Higgins Branch,Reach-1,7
Up Type=0
Dn Type=3
Dn Slope=0.005

--- Higgins Branch.g01 (geometry) ---

Geom Title=Existing Conditions

River Reach=Higgins Branch,Reach-1
Reach XY= 30
      2374557.44      7033033.74      2375003.15      7033282.76
      2375115.27      7033596.60      2375208.95      7033559.63
      2375273.58      7033607.25      2375421.44      7034060.00
      2375180.13      7034647.97      2375580.56      7034906.24
      2375726.09      7034917.91      2375771.67      7035210.10
      2375682.31      7035358.26      2376023.46      7035857.58
      2376036.75      7035966.45      2376178.01      7036070.28
      2376176.76      7036304.07      2375928.38      7036889.95
      2376078.49      7037175.21      2376030.05      7037949.56
      2376179.40      7038189.86      2376173.55      7038312.45
      2376028.70      7038484.88      2376079.50      7038999.83
      2376029.37      7039244.73      2376121.22      7039413.40
      2375928.93      7039679.89      2375931.06      7039854.14
      2376025.45      7039961.47      2376078.97      7040225.42
      2375979.94      7040370.48      2376029.00      7040560.00

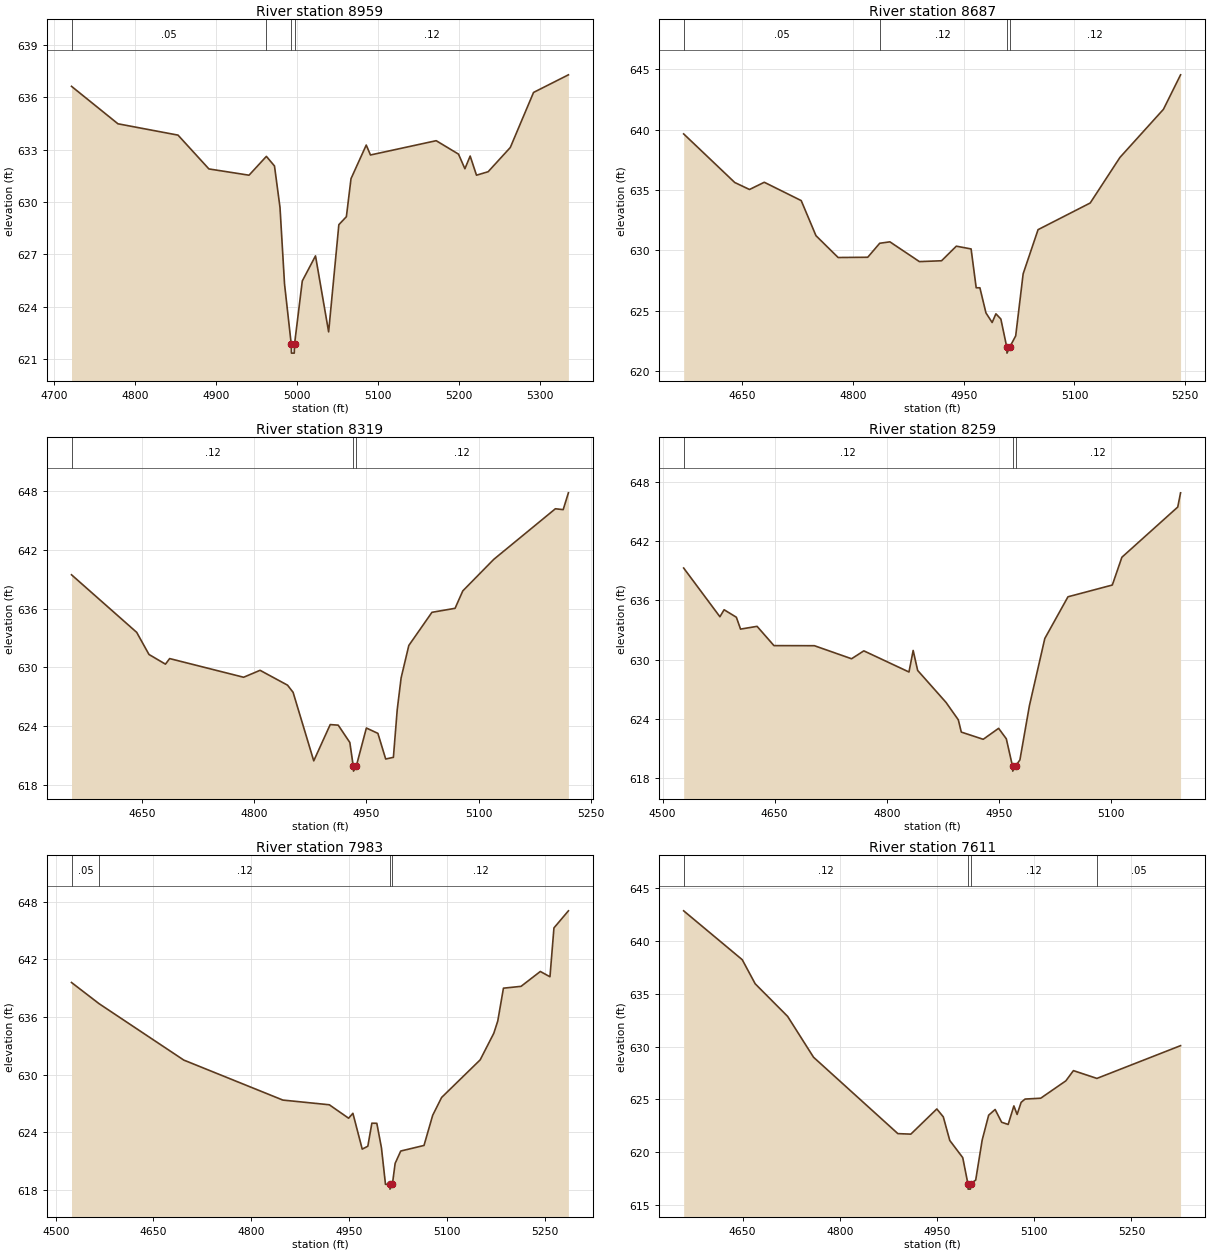
Type RM Length L Ch R = 1,8959,272,272,272
BEGIN DESCRIPTION:
Higgins Branch 19.0
END DESCRIPTION:
XS GIS Cut Line= 4
      2374628.53      7033367.38      2374940.16      7033199.70
      2374963.45      7033113.99      2375094.96      7033005.78
#Sta/Elev= 30
  4721.7  636.64  4779.0  634.49  4853.1  633.84  4891.2  631.90  4940.7  631.54
  4962.1  632.62  4972.1  632.07  4978.9  629.69  4984.5  625.29  4992.8  621.83
  4993.0  621.33  4996.5  621.33  4996.8  621.83  5006.4  625.47  5022.7  626.91
  5038.9  622.55  5051.5  628.70  5060.8  629.16  5066.5  631.34  5085.3  633.27
  5090.5  632.70  5171.6  633.52  5199.1  632.75  5207.0  631.91  5213.5  632.64
  5221.3  631.54  5235.7  631.74  5263.0  633.13  5291.7  636.29  5334.7  637.30
#Mann=4,-1,0
  4721.7    0.05       0  4962.1    0.12       0  4992.8    0.07       0
  4996.8    0.12       0
Bank Sta=4992.8,4996.8
Exp/Cntr=0.3,0.1

Type RM Length L Ch R = 1,8687,368,368,368
BEGIN DESCRIPTION:
Higgins Branch 18.0
END DESCRIPTION:
XS GIS Cut Line= 3
      2374599.80      7033399.53      2374997.74      7033408.00
      2375270.40      7033372.44
#Sta/Elev= 30
  4570.7  639.65  4639.9  635.62  4659.9  635.04  4679.9  635.64  4729.9  634.12
  4749.9  631.21  4779.9  629.40  4820.0  629.42  4836.2  630.58  4850.0  630.70
  4890.0  629.06  4920.0  629.13  4940.0  630.34  4960.0  630.11  4966.9  626.89
  4971.9  626.89  4980.1  624.81  4988.5  624.01  4993.6  624.73  5000.3  624.30
  5008.3  621.97  5008.6  621.47  5012.3  621.97  5020.4  622.90  5030.5  628.05
  5050.7  631.71  5121.3  633.92  5161.6  637.70  5220.5  641.69  5243.7  644.55
#Mann=4,-1,0
  4570.7    0.05       0  4836.2    0.12       0  5008.3    0.07       0
  5012.3    0.12       0
Bank Sta=5008.3,5012.3
Exp/Cntr=0.3,0.1

Type RM Length L Ch R = 1,8319,60,60,60
BEGIN DESCRIPTION:
Higgins Branch 17.2
END DESCRIPTION:
XS GIS Cut Line= 3
      2374843.80      7033763.99      2375172.53      7033590.40
      2375455.84      7033519.47
#Sta/Elev= 30
  4556.1  639.47  4643.2  633.58  4659.6  631.32  4681.6  630.33  4687.2  630.90
  4786.0  628.99  4808.0  629.70  4844.7  628.18  4852.1  627.45  4879.7  620.44
  4901.7  624.15  4912.4  624.09  4927.9  622.32  4932.5  619.89  4932.8  619.39
  4936.5  619.89  4950.0  623.80  4965.4  623.25  4975.8  620.63  4986.1  620.80
  4991.2  625.66  4996.4  628.92  5006.7  632.24  5037.6  635.63  5068.5  636.04
  5078.8  637.82  5120.1  641.04  5202.5  646.22  5212.9  646.13  5219.9  647.85
#Mann=3,-1,0
  4556.1    0.12       0  4932.5    0.07       0  4936.5    0.12       0
Bank Sta=4932.5,4936.5
Exp/Cntr=0.3,0.1

Type RM Length L Ch R = 1,8259,276,276,276
BEGIN DESCRIPTION:
Higgins Branch 17.0
END DESCRIPTION:
XS GIS Cut Line= 3
      2374852.22      7033818.20      2375181.00      7033644.59
      2375465.13      7033573.46
#Sta/Elev= 30
  4528.3  639.26  4576.8  634.33  4582.4  635.04  4598.8  634.28  4604.4  633.08
  4626.5  633.36  4649.1  631.41  4703.2  631.40  4752.9  630.08  4769.3  630.88
  4829.7  628.74  4835.3  630.92  4841.3  628.90  4879.3  625.66  4895.7  623.90
  4899.7  622.66  4929.0  621.93  4949.6  623.04  4959.9  621.98  4968.2  619.21
  4968.5  618.71  4972.2  619.21  4978.1  619.85  4990.8  625.33  5011.4  632.13
  5042.4  636.35  5101.7  637.54  5114.5  640.35  5189.2  645.43  5193.0  646.87
#Mann=3,-1,0
  4528.3    0.12       0  4968.2    0.07       0  4972.2    0.12       0
Bank Sta=4968.2,4972.2
Exp/Cntr=0.3,0.1

Type RM Length L Ch R = 1,7983,372,372,372
BEGIN DESCRIPTION:
Higgins Branch 16.0
END DESCRIPTION:
XS GIS Cut Line= 3
      2374904.08      7034037.27      2375238.46      7033950.79
      2375579.04      7033709.97
#Sta/Elev= 30
  4524.2  639.60  4566.6  637.39  4696.4  631.52  4848.5  627.35  4919.8  626.86
  4949.4  625.46  4956.0  625.97  4970.3  622.24  4978.9  622.54  4985.1  624.94
  4992.7  624.93  4999.8  622.38  5006.0  618.57  5012.6  618.57  5012.9  618.07
  5016.6  618.57  5020.8  620.75  5029.4  622.04  5065.1  622.62  5078.4  625.76
  5092.1  627.62  5151.3  631.54  5172.2  634.31  5178.3  635.59  5187.0  639.01
  5214.0  639.20  5243.6  640.75  5258.4  640.20  5264.5  645.29  5286.7  647.07
#Mann=4,-1,0
  4524.2    0.05       0  4566.6    0.12       0  5012.6    0.07       0
  5016.6    0.12       0
Bank Sta=5012.6,5016.6
Exp/Cntr=0.3,0.1

Type RM Length L Ch R = 1,7611,78,78,78
BEGIN DESCRIPTION:
Higgins Branch 15.2
END DESCRIPTION:
XS GIS Cut Line= 3
      2374938.71      7034224.62      2375466.17      7034204.44
      2375702.51      7034169.86
#Sta/Elev= 30
  4559.1  642.88  4649.5  638.24  4669.5  635.95  4719.5  632.86  4759.5  628.98
  4889.6  621.73  4909.6  621.68  4949.7  624.07  4959.7  623.32  4969.7  621.08
  4989.7  619.45  4997.7  616.96  4998.0  616.46  5001.5  616.46  5001.7  616.96
  5009.7  617.32  5019.7  621.12  5029.7  623.48  5039.7  624.02  5049.7  622.81
  5059.8  622.60  5068.6  624.36  5073.6  623.55  5079.8  624.70  5085.9  625.01
  5110.0  625.09  5148.8  626.74  5160.5  627.71  5196.7  626.97  5325.8  630.08
#Mann=4,-1,0
  4559.1    0.12       0  4997.7    0.07       0  5001.7    0.12       0
  5196.7    0.05       0
Bank Sta=4997.7,5001.7
Exp/Cntr=0.3,0.1

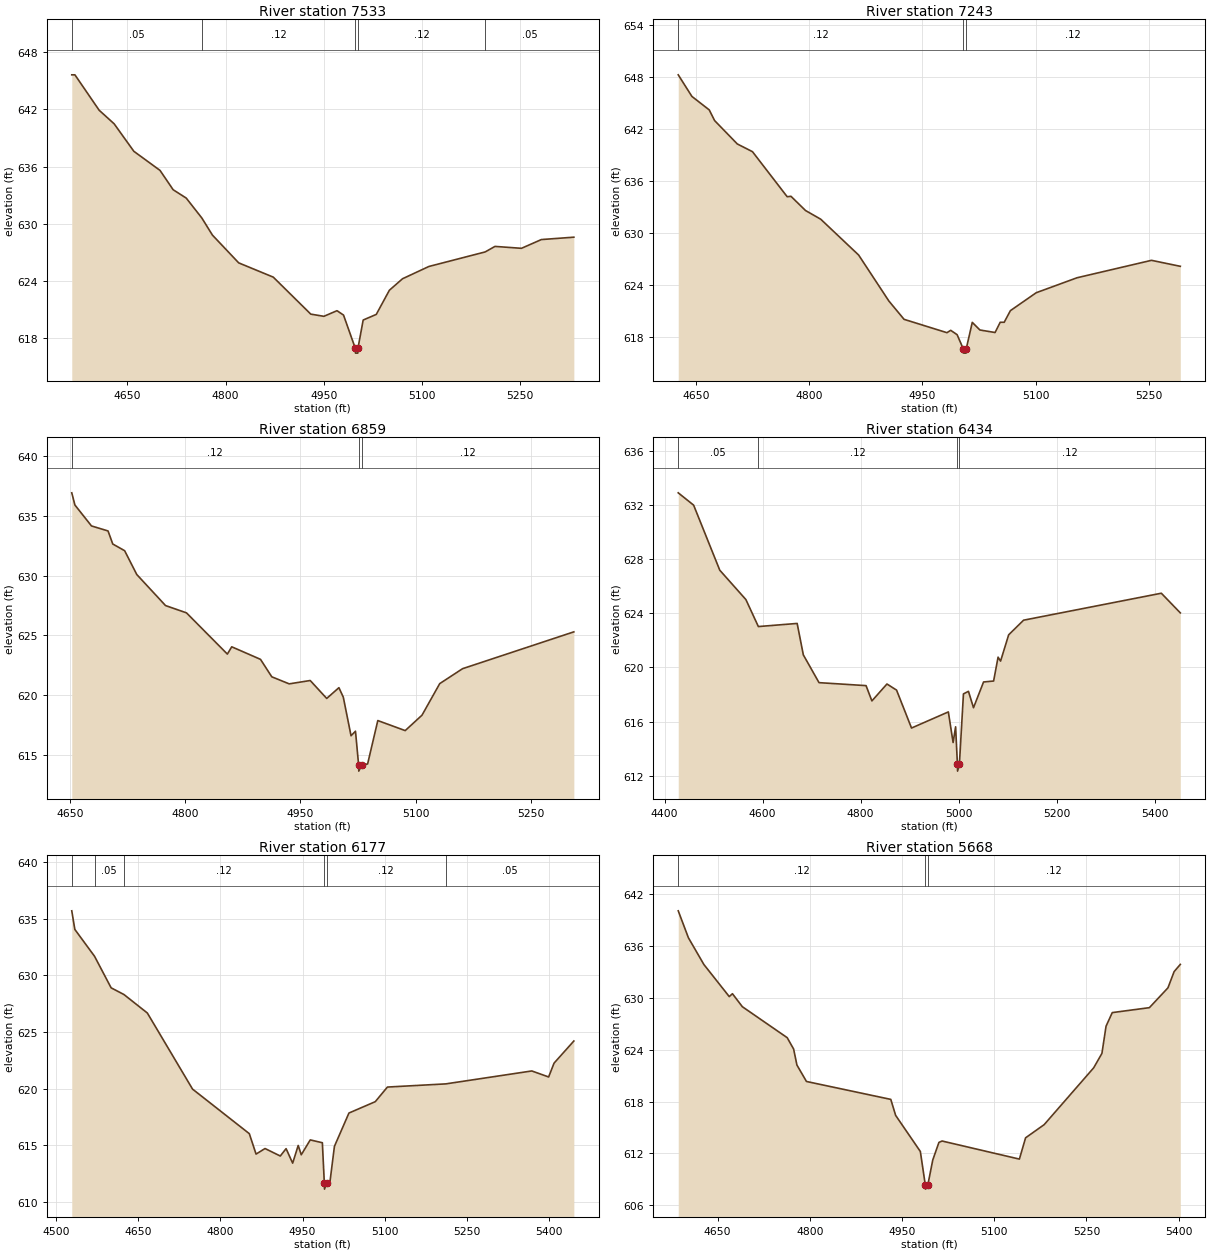
Type RM Length L Ch R = 1,7533,290,290,290
BEGIN DESCRIPTION:
Higgins Branch 15.0
END DESCRIPTION:
XS GIS Cut Line= 3
      2374924.31      7034296.68      2375451.76      7034276.50
      2375688.11      7034241.92
#Sta/Elev= 30
  4565.1  645.64  4569.9  645.64  4606.9  641.92  4629.8  640.49  4659.9  637.60
  4699.9  635.59  4719.9  633.56  4739.9  632.68  4763.8  630.58  4779.9  628.79
  4820.0  625.87  4872.8  624.37  4930.1  620.48  4950.1  620.25  4970.1  620.84
  4980.1  620.38  4998.1  616.88  4998.4  616.38  5001.9  616.38  5002.1  616.88
  5010.1  619.86  5030.1  620.45  5050.1  622.99  5070.2  624.20  5110.4  625.49
  5196.4  627.02  5211.4  627.60  5251.8  627.40  5282.2  628.32  5331.8  628.57
#Mann=5,-1,0
  4565.1    0.05       0  4763.8    0.12       0  4998.1    0.07       0
  5002.1    0.12       0  5196.4    0.05       0
Bank Sta=4998.1,5002.1
Exp/Cntr=0.3,0.1

Type RM Length L Ch R = 1,7243,384,384,384
BEGIN DESCRIPTION:
Higgins Branch 14.0
END DESCRIPTION:
XS GIS Cut Line= 3
      2374881.01      7034501.33      2375307.64      7034541.68
      2375523.85      7034444.96
#Sta/Elev= 30
  4626.3  648.30  4644.4  645.81  4667.4  644.25  4674.5  643.02  4704.6  640.32
  4724.7  639.43  4770.7  634.23  4775.7  634.28  4795.0  632.64  4815.1  631.64
  4865.4  627.50  4905.5  622.19  4925.6  620.08  4982.4  618.54  4987.4  618.81
  4995.9  618.31  5004.0  616.68  5004.2  616.18  5007.7  616.18  5008.0  616.68
  5016.0  619.73  5026.1  618.85  5046.2  618.56  5053.0  619.74  5058.3  619.74
  5066.5  621.08  5100.7  623.15  5154.9  624.88  5253.5  626.89  5291.7  626.20
#Mann=3,-1,0
  4626.3    0.12       0  5004.0    0.07       0  5008.0    0.12       0
Bank Sta=5004,5008
Exp/Cntr=0.3,0.1

Type RM Length L Ch R = 1,6859,425,425,425
BEGIN DESCRIPTION:
Higgins Branch 13.0
END DESCRIPTION:
XS GIS Cut Line= 3
      2375062.63      7034968.28      2375506.52      7034714.63
      2375587.25      7034596.42
#Sta/Elev= 30
  4651.9  636.93  4656.0  635.91  4677.6  634.16  4699.2  633.74  4705.3  632.65
  4720.8  632.09  4736.6  630.10  4774.1  627.50  4801.4  626.89  4854.7  623.44
  4860.4  624.05  4897.9  623.00  4912.6  621.54  4935.3  620.95  4962.7  621.23
  4984.2  619.73  5000.1  620.63  5005.8  619.84  5015.9  616.61  5021.7  616.99
  5025.8  614.15  5026.0  613.65  5029.8  614.15  5037.5  614.25  5050.8  617.88
  5086.5  617.04  5108.4  618.33  5131.5  620.97  5161.3  622.22  5306.3  625.30
#Mann=3,-1,0
  4651.9    0.12       0  5025.8    0.07       0  5029.8    0.12       0
Bank Sta=5025.8,5029.8
Exp/Cntr=0.3,0.1

Type RM Length L Ch R = 1,6434,257,257,257
BEGIN DESCRIPTION:
Higgins Branch 12.0
END DESCRIPTION:
XS GIS Cut Line= 4
      2375189.48      7035129.68      2375644.88      7034962.51
      2375861.14      7034913.89      2376132.03      7034749.20
#Sta/Elev= 30
  4428.0  632.89  4459.4  631.98  4512.7  627.18  4566.0  625.01  4591.4  623.02
  4670.5  623.25  4683.1  620.93  4715.1  618.88  4811.0  618.66  4822.9  617.53
  4853.6  618.78  4873.2  618.33  4903.7  615.53  4978.8  616.72  4988.5  614.46
  4993.6  615.62  4997.3  612.85  4997.6  612.35  5001.3  612.85  5009.6  618.05
  5019.8  618.24  5030.1  617.03  5050.6  618.93  5071.1  619.00  5080.2  620.76
  5085.3  620.47  5101.8  622.41  5132.2  623.49  5413.1  625.48  5451.8  624.03
#Mann=4,-1,0
  4428.0    0.05       0  4591.4    0.12       0  4997.3    0.07       0
  5001.3    0.12       0
Bank Sta=4997.3,5001.3
Exp/Cntr=0.3,0.1

Type RM Length L Ch R = 1,6177,509,509,509
BEGIN DESCRIPTION:
Higgins Branch 11.0
END DESCRIPTION:
XS GIS Cut Line= 3
      2375342.20      7035409.30      2375791.88      7035172.93
      2376194.66      7035106.76
#Sta/Elev= 30
  4528.9  635.68  4534.5  634.04  4570.5  631.67  4600.7  628.89  4624.1  628.30
  4666.8  626.67  4749.3  619.96  4852.9  616.03  4865.2  614.23  4881.6  614.72
  4909.4  614.06  4920.0  614.71  4932.0  613.43  4942.1  614.99  4947.7  614.17
  4964.1  615.48  4986.2  615.23  4989.8  611.64  4990.1  611.14  4993.8  611.64
  4999.8  611.68  5008.2  614.91  5034.7  617.85  5082.7  618.85  5104.9  620.14
  5211.4  620.42  5368.4  621.56  5399.1  621.03  5409.0  622.25  5445.1  624.20
#Mann=6,-1,0
  4528.9    0.12       0  4570.5    0.05       0  4624.1    0.12       0
  4989.8    0.07       0  4993.8    0.12       0  5211.4    0.05       0
Bank Sta=4989.8,4993.8
Exp/Cntr=0.3,0.1

Type RM Length L Ch R = 1,5668,446,446,446
BEGIN DESCRIPTION:
Higgins Branch 10.0
END DESCRIPTION:
XS GIS Cut Line= 3
      2375429.04      7035709.99      2375742.88      7035616.82
      2376228.99      7035560.00
#Sta/Elev= 30
  4586.0  640.04  4602.6  636.92  4627.7  633.84  4669.0  630.13  4674.2  630.46
  4690.3  628.96  4763.3  625.38  4773.7  624.07  4779.1  622.22  4794.6  620.32
  4931.8  618.25  4939.7  616.40  4979.9  612.23  4987.9  608.38  4988.3  607.88
  4992.1  608.38  5000.1  611.25  5010.1  613.28  5015.2  613.44  5141.0  611.35
  5151.1  613.81  5181.3  615.33  5261.9  621.90  5275.3  623.57  5282.0  626.71
  5292.1  628.28  5352.5  628.85  5382.7  631.14  5392.7  633.01  5402.8  633.85
#Mann=3,-1,0
  4586.0    0.12       0  4987.9    0.07       0  4992.1    0.12       0
Bank Sta=4987.9,4992.1
Exp/Cntr=0.3,0.1

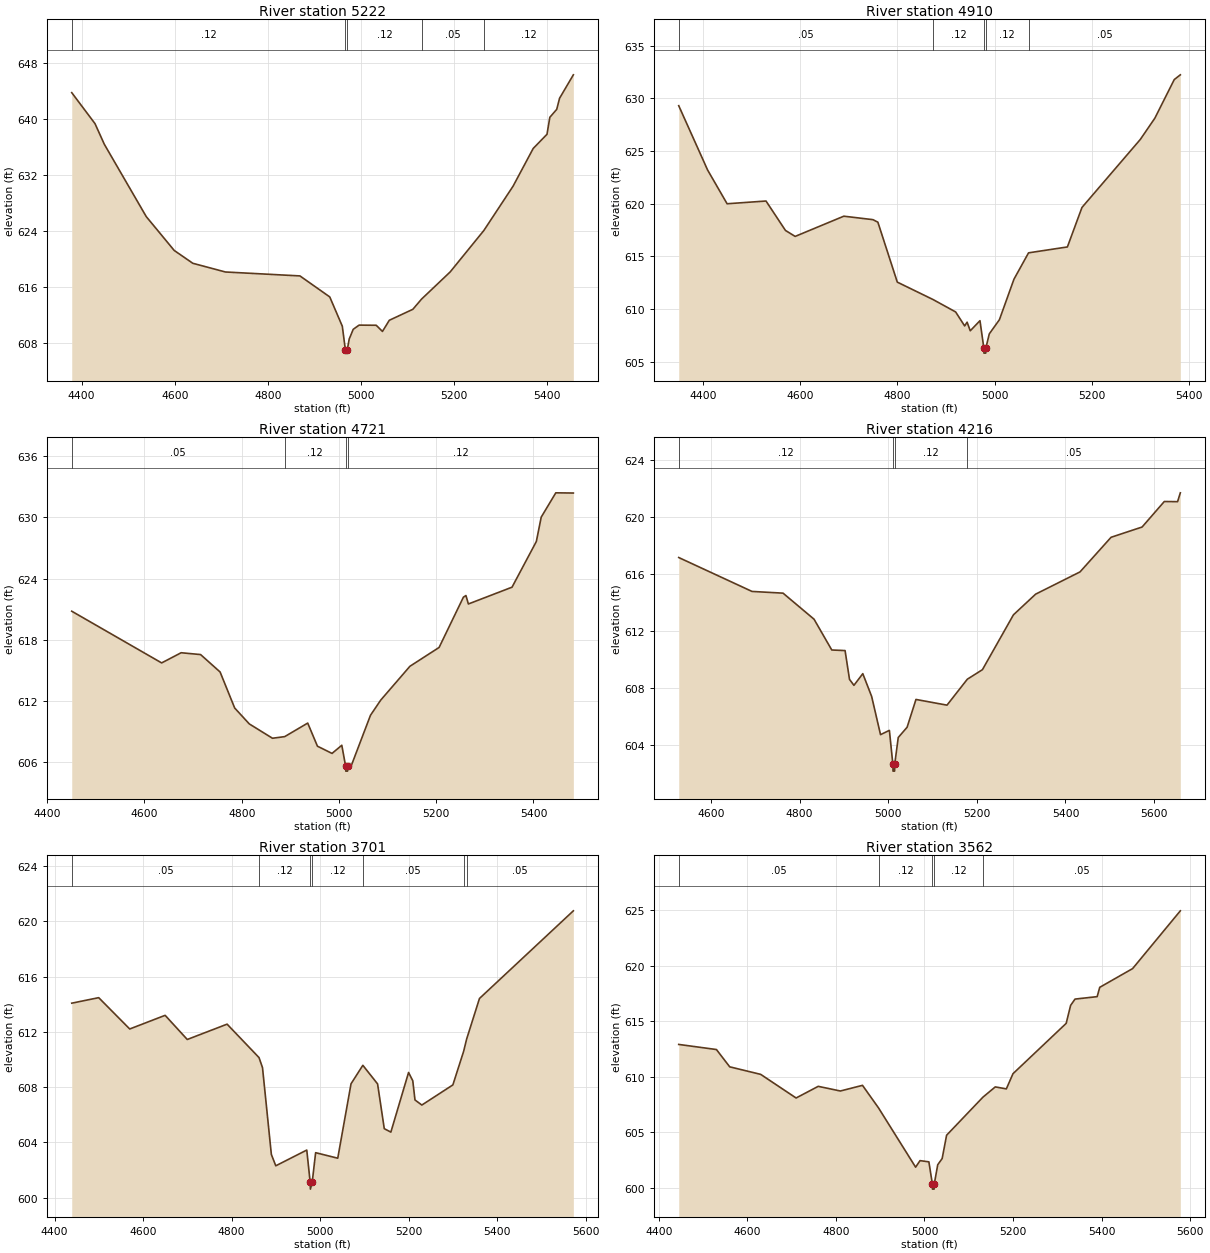
Type RM Length L Ch R = 1,5222,312,312,312
BEGIN DESCRIPTION:
Higgins Branch 9.0
END DESCRIPTION:
XS GIS Cut Line= 3
      2375429.00      7036010.00      2375953.29      7036014.59
      2376404.66      7035695.47
#Sta/Elev= 30
  4378.7  643.72  4428.7  639.30  4448.7  636.36  4538.7  626.06  4598.7  621.24
  4638.7  619.41  4708.7  618.17  4868.7  617.61  4932.7  614.62  4959.7  610.44
  4966.2  607.11  4966.5  606.61  4970.4  607.11  4974.5  608.62  4983.1  610.00
  4995.7  610.60  5032.5  610.58  5045.9  609.70  5060.6  611.29  5111.1  612.85
  5129.9  614.31  5191.2  618.17  5263.6  624.08  5326.4  630.40  5369.6  635.77
  5399.2  637.79  5405.3  640.21  5420.1  641.34  5426.2  642.92  5455.8  646.26
#Mann=5,-1,0
  4378.7    0.12       0  4966.2    0.07       0  4970.4    0.12       0
  5129.9    0.05       0  5263.6    0.12       0
Bank Sta=4966.2,4970.4
Exp/Cntr=0.3,0.1

Type RM Length L Ch R = 1,4910,189,189,189
BEGIN DESCRIPTION:
Higgins Branch 8.2
END DESCRIPTION:
XS GIS Cut Line= 3
      2375529.55      7036155.82      2376172.36      7036187.53
      2376561.46      7036184.65
#Sta/Elev= 30
  4349.7  629.30  4409.2  623.19  4449.3  619.99  4529.4  620.25  4569.4  617.46
  4589.4  616.89  4689.6  618.81  4749.6  618.48  4759.7  618.24  4799.7  612.55
  4873.2  610.90  4919.8  609.72  4938.4  608.39  4943.4  608.75  4949.9  607.93
  4969.9  608.89  4977.8  606.31  4978.1  605.81  4981.7  605.81  4982.1  606.31
  4989.1  607.64  5009.9  608.98  5039.9  612.83  5069.9  615.33  5149.9  615.89
  5179.9  619.64  5299.9  626.09  5329.9  628.11  5369.9  631.78  5382.4  632.23
#Mann=5,-1,0
  4349.7    0.05       0  4873.2    0.12       0  4977.8    0.07       0
  4982.1    0.12       0  5069.9    0.05       0
Bank Sta=4977.8,4982.1
Exp/Cntr=0.3,0.1

Type RM Length L Ch R = 1,4721,505,505,505
BEGIN DESCRIPTION:
Higgins Branch 8.0
END DESCRIPTION:
XS GIS Cut Line= 3
      2375584.32      7036334.53      2376227.12      7036366.24
      2376615.13      7036363.37
#Sta/Elev= 30
  4450.4  620.79  4635.3  615.71  4675.4  616.71  4715.4  616.53  4755.5  614.82
  4785.5  611.28  4815.5  609.72  4863.2  608.31  4888.4  608.47  4935.7  609.80
  4955.7  607.53  4985.7  606.82  5005.8  607.62  5013.6  605.58  5014.0  605.08
  5017.6  605.08  5017.9  605.58  5025.8  605.68  5064.8  610.57  5085.9  612.06
  5145.9  615.38  5205.9  617.23  5255.9  622.17  5261.1  622.33  5266.1  621.50
  5355.9  623.15  5405.9  627.64  5415.9  630.03  5445.9  632.42  5482.0  632.40
#Mann=4,-1,0
  4450.4    0.05       0  4888.4    0.12       0  5013.6    0.07       0
  5017.9    0.12       0
Bank Sta=5013.6,5017.9
Exp/Cntr=0.3,0.1

Type RM Length L Ch R = 1,4216,515,515,515
BEGIN DESCRIPTION:
Higgins Branch 7.6
END DESCRIPTION:
XS GIS Cut Line= 3
      2375503.65      7036804.36      2376209.83      7036801.48
      2376635.17      7036781.36
#Sta/Elev= 30
  4527.2  617.17  4692.6  614.79  4762.6  614.67  4832.6  612.84  4872.6  610.68
  4902.6  610.64  4912.6  608.62  4922.6  608.20  4942.6  609.02  4962.6  607.42
  4982.6  604.74  5002.6  605.04  5010.4  602.68  5010.8  602.18  5014.4  602.18
  5014.7  602.68  5022.6  604.54  5042.6  605.26  5062.6  607.21  5132.6  606.81
  5178.5  608.63  5212.6  609.30  5282.6  613.15  5332.7  614.60  5432.8  616.16
  5502.9  618.59  5572.9  619.31  5623.0  621.10  5653.0  621.09  5659.2  621.71
#Mann=4,-1,0
  4527.2    0.12       0  5010.4    0.07       0  5014.7    0.12       0
  5178.5    0.05       0
Bank Sta=5010.4,5014.7
Exp/Cntr=0.3,0.1

Type RM Length L Ch R = 1,3701,139,139,139
BEGIN DESCRIPTION:
Higgins Branch 7.2
END DESCRIPTION:
XS GIS Cut Line= 3
      2375518.05      7037251.13      2376224.24      7037248.25
      2376650.87      7037228.07
#Sta/Elev= 30
  4438.9  614.08  4499.8  614.48  4569.9  612.21  4649.9  613.20  4699.9  611.45
  4789.9  612.56  4862.0  610.14  4869.9  609.41  4889.9  603.12  4899.9  602.30
  4969.9  603.44  4977.6  601.11  4978.1  600.61  4982.2  601.11  4989.9  603.25
  5039.9  602.85  5069.9  608.24  5096.6  609.58  5129.9  608.23  5145.0  604.99
  5159.9  604.74  5199.9  609.06  5209.4  608.46  5214.4  607.07  5229.9  606.70
  5300.0  608.16  5324.4  610.60  5331.0  611.47  5360.1  614.42  5572.2  620.77
#Mann=7,-1,0
  4438.9    0.05       0  4862.0    0.12       0  4977.6    0.07       0
  4982.2    0.12       0  5096.6    0.05       0  5324.4    0.12       0
  5331.0    0.05       0
Bank Sta=4977.6,4982.2
Exp/Cntr=0.3,0.1

Type RM Length L Ch R = 1,3562,285,285,285
BEGIN DESCRIPTION:
Higgins Branch 7.0
END DESCRIPTION:
XS GIS Cut Line= 3
      2375523.83      7037389.49      2376230.00      7037386.61
      2376656.64      7037366.43
#Sta/Elev= 30
  4444.8  612.91  4530.0  612.45  4560.0  610.89  4630.0  610.21  4710.0  608.08
  4760.0  609.13  4810.0  608.71  4860.0  609.22  4896.3  607.18  4980.0  601.84
  4990.0  602.43  5010.0  602.32  5017.7  600.36  5018.2  599.86  5021.8  599.86
  5022.3  600.36  5030.0  602.06  5040.0  602.62  5050.0  604.72  5132.0  608.15
  5160.0  609.08  5185.0  608.90  5200.0  610.27  5320.2  614.81  5330.2  616.43
  5340.2  617.00  5390.2  617.22  5396.0  618.06  5470.3  619.75  5578.1  624.96
#Mann=5,-1,0
  4444.8    0.05       0  4896.3    0.12       0  5017.7    0.07       0
  5022.3    0.12       0  5132.0    0.05       0
Bank Sta=5017.7,5022.3
Exp/Cntr=0.3,0.1

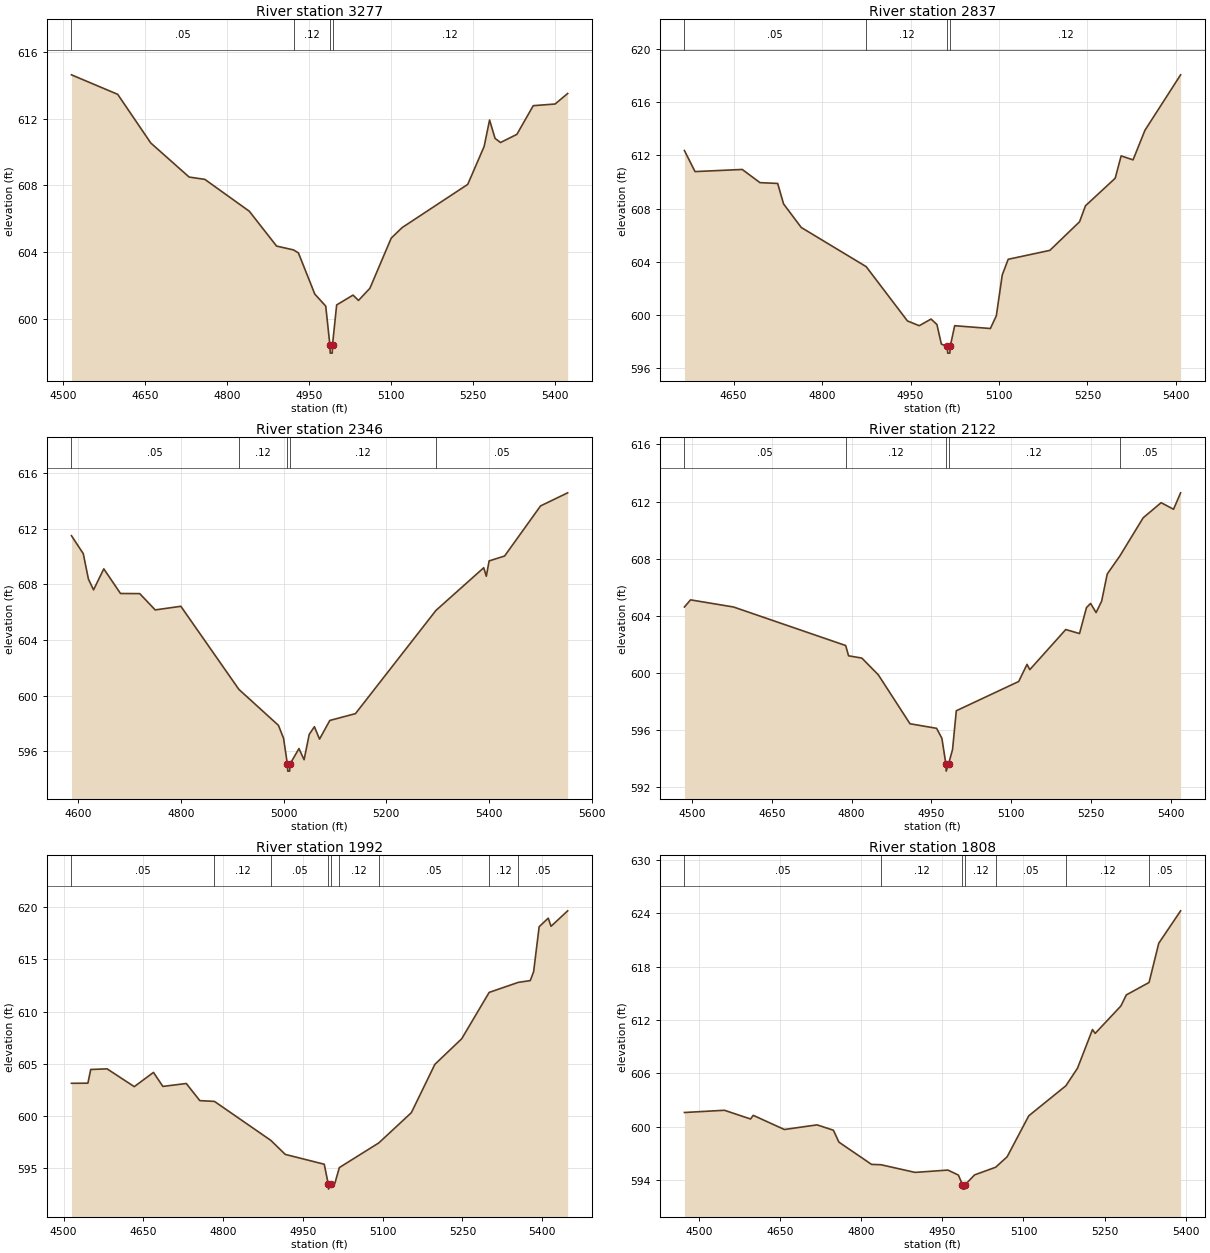
Type RM Length L Ch R = 1,3277,440,440,440
BEGIN DESCRIPTION:
Higgins Branch 6.0
END DESCRIPTION:
XS GIS Cut Line= 3
      2375543.98      7037680.61      2375863.94      7037660.43
      2376451.96      7037646.02
#Sta/Elev= 30
  4514.7  614.63  4599.4  613.46  4660.0  610.54  4730.2  608.50  4759.0  608.36
  4840.4  606.45  4890.4  604.36  4921.4  604.13  4930.4  603.95  4960.4  601.48
  4980.4  600.76  4988.0  598.44  4988.6  597.94  4992.3  597.94  4992.8  598.44
  5000.4  600.83  5030.4  601.42  5040.4  601.10  5061.3  601.83  5100.4  604.84
  5120.4  605.47  5240.5  608.06  5270.5  610.33  5280.5  611.92  5290.5  610.82
  5300.5  610.57  5330.5  611.06  5360.5  612.78  5400.5  612.88  5423.5  613.51
#Mann=4,-1,0
  4514.7    0.05       0  4921.4    0.12       0  4988.0    0.07       0
  4992.8    0.12       0
Bank Sta=4988,4992.8
Exp/Cntr=0.3,0.1

Type RM Length L Ch R = 1,2837,491,491,491
BEGIN DESCRIPTION:
Higgins Branch 5.0
END DESCRIPTION:
XS GIS Cut Line= 3
      2375690.96      7038055.32      2376129.00      7038060.00
      2376529.02      7038110.00
#Sta/Elev= 30
  4566.7  612.37  4584.7  610.79  4664.7  610.95  4694.8  609.96  4724.8  609.90
  4734.8  608.36  4764.8  606.59  4874.8  603.65  4944.8  599.57  4964.8  599.21
  4984.8  599.71  4994.8  599.30  5002.3  597.83  5012.4  597.65  5013.0  597.15
  5016.7  597.15  5017.3  597.65  5024.9  599.21  5085.4  599.00  5095.5  599.96
  5105.5  603.02  5115.6  604.20  5186.2  604.87  5236.6  607.02  5246.6  608.22
  5297.0  610.29  5307.1  611.97  5327.3  611.67  5347.4  613.89  5407.9  618.06
#Mann=4,-1,0
  4566.7    0.05       0  4874.8    0.12       0  5012.4    0.07       0
  5017.3    0.12       0
Bank Sta=5012.4,5017.3
Exp/Cntr=0.3,0.1

Type RM Length L Ch R = 1,2346,224,224,224
BEGIN DESCRIPTION:
Higgins Branch 4.0
END DESCRIPTION:
XS GIS Cut Line= 3
      2375616.04      7038461.74      2376273.24      7038484.80
      2376581.68      7038464.62
#Sta/Elev= 30
  4586.5  611.49  4609.5  610.20  4619.5  608.38  4629.5  607.60  4649.5  609.11
  4682.0  607.34  4719.5  607.33  4749.6  606.16  4799.6  606.42  4912.7  600.45
  4989.7  597.87  4999.7  596.94  5007.2  595.08  5007.9  594.58  5011.6  594.58
  5012.2  595.08  5029.7  596.20  5039.7  595.40  5049.7  597.22  5059.8  597.77
  5069.8  596.88  5089.8  598.22  5139.8  598.71  5296.5  606.12  5389.7  609.19
  5394.7  608.58  5400.2  609.68  5430.3  610.03  5500.4  613.63  5553.2  614.57
#Mann=5,-1,0
  4586.5    0.05       0  4912.7    0.12       0  5007.2    0.07       0
  5012.2    0.12       0  5296.5    0.05       0
Bank Sta=5007.2,5012.2
Exp/Cntr=0.3,0.1

Type RM Length L Ch R = 1,2122,130,130,130
BEGIN DESCRIPTION:
Higgins Branch 3.6
END DESCRIPTION:
XS GIS Cut Line= 4
      2375538.21      7038836.46      2375918.71      7038700.98
      2376028.24      7038700.98      2376431.76      7038585.69
#Sta/Elev= 30
  4485.8  604.61  4497.3  605.11  4578.2  604.61  4789.1  601.91  4794.5  601.19
  4819.5  601.03  4850.4  599.86  4910.0  596.43  4960.0  596.11  4970.0  595.41
  4977.5  593.61  4978.1  593.11  4982.5  593.61  4990.0  594.62  4997.1  597.34
  5114.4  599.39  5130.1  600.59  5135.3  600.22  5202.9  603.03  5228.8  602.75
  5241.9  604.57  5249.6  604.86  5260.0  604.22  5270.4  605.02  5280.9  606.92
  5304.9  608.20  5348.5  610.86  5382.3  611.92  5405.6  611.46  5418.9  612.61
#Mann=5,-1,0
  4485.8    0.05       0  4789.1    0.12       0  4977.5    0.07       0
  4982.5    0.12       0  5304.9    0.05       0
Bank Sta=4977.5,4982.5
Exp/Cntr=0.3,0.1

Type RM Length L Ch R = 1,1992,184,184,184
BEGIN DESCRIPTION:
Higgins Branch 3.4
END DESCRIPTION:
XS GIS Cut Line= 4
      2375567.10      7038966.14      2375947.53      7038830.69
      2376057.06      7038830.69      2376460.56      7038715.40
#Sta/Elev= 30
  4514.9  603.14  4545.8  603.15  4551.1  604.46  4581.9  604.52  4633.0  602.82
  4669.1  604.18  4686.8  602.84  4730.8  603.12  4756.3  601.48  4783.7  601.41
  4889.8  597.68  4916.9  596.34  4990.2  595.40  4997.7  593.52  4998.3  593.02
  5002.7  593.52  5010.2  593.58  5018.6  595.08  5092.8  597.44  5154.0  600.33
  5198.2  604.95  5248.7  607.40  5300.3  611.83  5355.1  612.79  5377.6  612.96
  5383.9  613.81  5394.3  618.11  5411.4  618.93  5416.6  618.15  5447.9  619.63
#Mann=9,-1,0
  4514.9    0.05       0  4783.7    0.12       0  4889.8    0.05       0
  4997.7   0.033       0  5002.7    0.05       0  5018.6    0.12       0
  5092.8    0.05       0  5300.3    0.12       0  5355.1    0.05       0
Bank Sta=4997.7,5002.7
Exp/Cntr=0.3,0.1

Type RM Length L Ch R = 1,1808,355,355,355
BEGIN DESCRIPTION:
Higgins Branch 3.0
END DESCRIPTION:
XS GIS Cut Line= 3
      2375555.56      7039041.10      2375956.18      7038989.22
      2376469.24      7039026.69
#Sta/Elev= 30
  4472.4  601.60  4546.5  601.85  4594.8  600.87  4599.8  601.28  4657.4  599.69
  4717.9  600.21  4748.1  599.61  4758.4  598.27  4818.7  595.77  4836.3  595.73
  4899.3  594.87  4960.1  595.13  4979.5  594.57  4987.0  593.49  4987.6  592.99
  4991.4  592.99  4992.0  593.49  5009.5  594.59  5048.5  595.45  5069.7  596.62
  5109.8  601.23  5178.4  604.60  5200.0  606.58  5227.7  610.92  5232.7  610.49
  5280.3  613.57  5290.3  614.81  5332.4  616.21  5350.4  620.62  5390.8  624.26
#Mann=7,-1,0
  4472.4    0.05       0  4836.3    0.12       0  4987.0    0.07       0
  4992.0    0.12       0  5048.5    0.05       0  5178.4    0.12       0
  5332.4    0.05       0
Bank Sta=4987,4992
Exp/Cntr=0.3,0.1

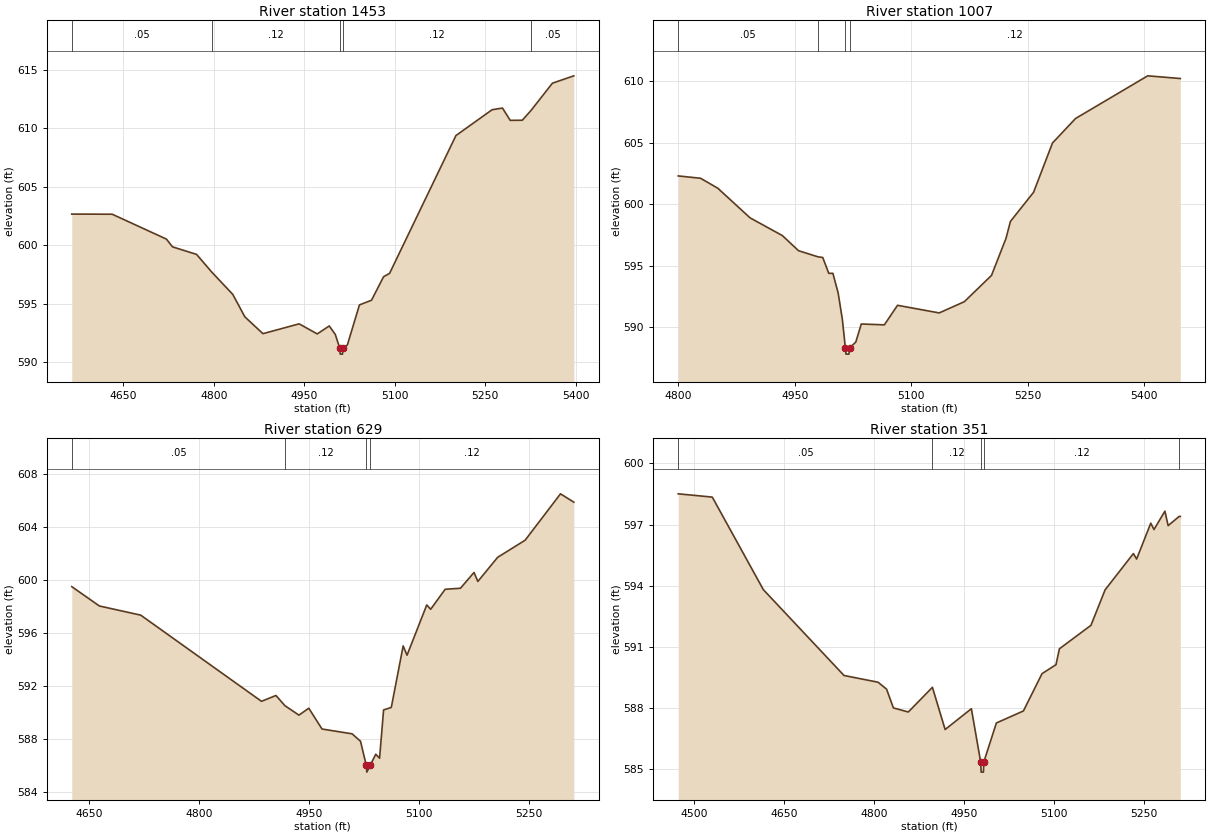
Type RM Length L Ch R = 1,1453,446,446,446
BEGIN DESCRIPTION:
Higgins Branch 2.0
END DESCRIPTION:
XS GIS Cut Line= 3
      2375642.00      7039320.69      2376013.83      7039320.69
      2376474.47      7039326.45
#Sta/Elev= 30
  4564.5  602.67  4631.5  602.66  4721.5  600.53  4731.5  599.87  4771.5  599.22
  4796.6  597.71  4831.5  595.80  4851.5  593.88  4881.5  592.44  4941.5  593.28
  4971.5  592.42  4991.5  593.10  5001.5  592.37  5008.9  591.19  5009.6  590.69
  5013.4  590.69  5014.1  591.19  5021.5  591.48  5041.5  594.90  5061.5  595.30
  5081.5  597.31  5091.5  597.60  5201.5  609.39  5261.5  611.60  5278.7  611.74
  5291.5  610.69  5311.5  610.70  5325.9  611.53  5361.5  613.87  5397.0  614.50
#Mann=5,-1,0
  4564.5    0.05       0  4796.6    0.12       0  5008.9    0.07       0
  5014.1    0.12       0  5325.9    0.05       0
Bank Sta=5008.9,5014.1
Exp/Cntr=0.3,0.1

Type RM Length L Ch R = 1,1007,378,378,378
BEGIN DESCRIPTION:
Higgins Branch 1.0
END DESCRIPTION:
XS GIS Cut Line= 3
      2375739.96      7039606.04      2375929.00      7039660.00
      2376348.07      7039825.07
#Sta/Elev= 30
  4799.7  602.30  4828.5  602.11  4850.7  601.30  4892.3  598.89  4933.9  597.45
  4954.7  596.22  4979.9  595.72  4985.9  595.67  4993.7  594.38  4999.0  594.38
  5005.8  592.78  5011.2  590.63  5015.1  588.31  5015.9  587.81  5019.7  587.81
  5020.4  588.31  5028.5  588.79  5035.6  590.26  5065.3  590.19  5082.3  591.78
  5136.0  591.16  5168.3  592.07  5203.4  594.21  5222.0  597.21  5227.8  598.60
  5257.6  600.97  5282.0  604.98  5311.7  606.97  5404.7  610.44  5446.7  610.22
#Mann=4,-1,0
  4799.7    0.05       0  4979.9    0.12       0  5015.1    0.07       0
  5020.4    0.12       0
Bank Sta=5015.1,5020.4
Exp/Cntr=0.3,0.1

Type RM Length L Ch R = 1,629,278,278,278
BEGIN DESCRIPTION:
Higgins Branch 0.5
END DESCRIPTION:
XS GIS Cut Line= 3
      2375708.26      7039819.33      2375900.18      7039959.77
      2376326.36      7040095.53
#Sta/Elev= 30
  4626.5  599.47  4664.2  598.01  4720.6  597.32  4885.4  590.82  4905.1  591.26
  4917.4  590.49  4936.5  589.78  4949.9  590.30  4968.0  588.73  5009.0  588.37
  5020.5  587.81  5028.4  585.98  5029.1  585.48  5033.7  585.98  5041.3  586.83
  5046.5  586.53  5052.0  590.17  5062.5  590.36  5078.7  595.00  5084.0  594.30
  5110.9  598.09  5116.2  597.76  5136.0  599.27  5156.9  599.35  5175.4  600.54
  5180.6  599.86  5207.6  601.68  5245.1  602.97  5293.4  606.47  5311.6  605.84
#Mann=4,-1,0
  4626.5    0.05       0  4917.4    0.12       0  5028.4    0.07       0
  5033.7    0.12       0
Bank Sta=5028.4,5033.7
Exp/Cntr=0.3,0.1

Type RM Length L Ch R = 1,351,0,0,0
BEGIN DESCRIPTION:
Higgins Branch 0.3
END DESCRIPTION:
XS GIS Cut Line= 3
      2375679.47      7039928.88      2375920.35      7040196.13
      2376359.67      7040384.28
#Sta/Elev= 30
  4473.0  598.51  4529.8  598.35  4615.0  593.81  4749.6  589.60  4806.4  589.27
  4820.6  588.93  4832.0  588.01  4856.9  587.81  4897.1  589.02  4918.3  586.95
  4962.1  587.97  4977.6  585.36  4978.4  584.86  4982.2  584.86  4982.9  585.36
  5003.8  587.27  5048.9  587.86  5080.0  589.69  5103.3  590.13  5109.0  590.91
  5161.6  592.06  5185.2  593.80  5232.4  595.58  5237.8  595.31  5261.4  597.07
  5266.8  596.76  5285.0  597.66  5290.4  596.95  5308.7  597.40  5310.7  597.40
#Mann=5,-1,0
  4473.0    0.05       0  4897.1    0.12       0  4977.6    0.07       0
  4982.9    0.12       0  5308.7    0.05       0
Bank Sta=4977.6,4982.9
Exp/Cntr=0.3,0.1

Chan Stop Cuts=-1