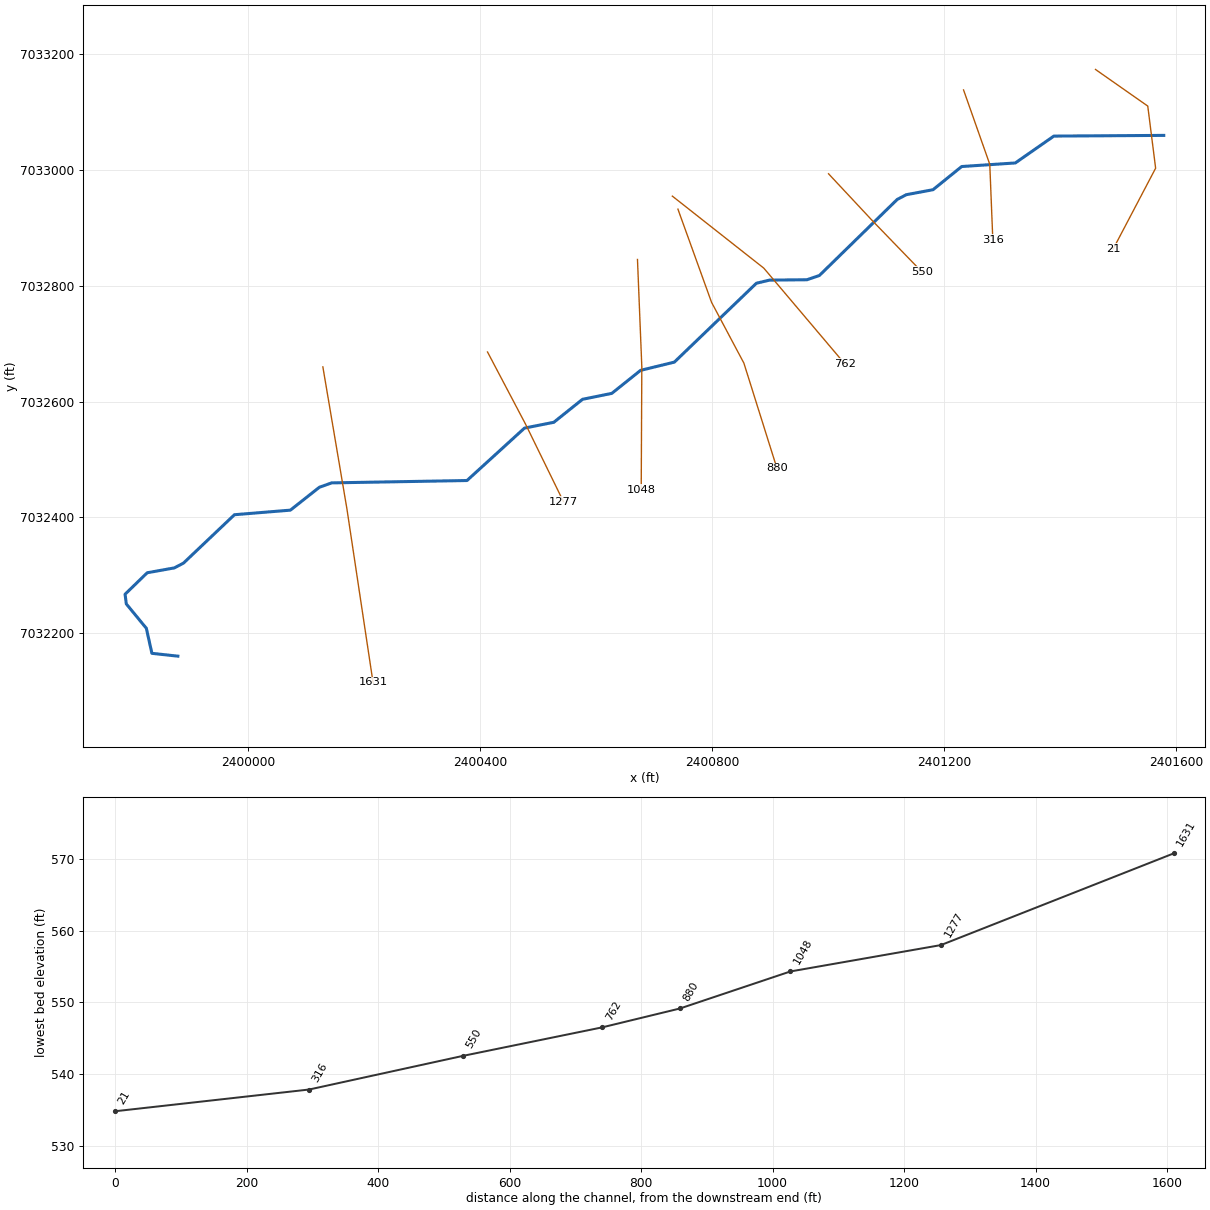
--- Hudgens Branch.prj (project) ---

Proj Title=Hudgens Branch Base Level Engineering
Current Plan=p01
Default Exp/Contr=0.3,0.1
English Units
Geom File=g01
Flow File=f01
Plan File=p01
BEGIN DESCRIPTION:
Hudgens Branch
END DESCRIPTION:

--- Hudgens Branch.p01 (plan) ---

Plan Title=Multiple Run
Short Identifier=Multiple
Geom File=g01
Flow File=f01
Subcritical Flow
K Sum by GR= 0
Std Step Tol= 0.01
Critical Tol= 0.01
Num of Std Step Trials= 20
Max Error Tol= 0.3
Flow Tol Ratio= 0.001
Split Flow NTrial= 30
Split Flow Tol= 0.02
Split Flow Ratio= 0.02
Log Output Level= 0
Friction Slope Method= 1
Unsteady Friction Slope Method= 2
Unsteady Bridges Friction Slope Method= 1
Parabolic Critical Depth
Global Vel Dist=  1 , 1 , 1
Global Log Level= 0
CheckData=True
Encroach Param= -1, 0, 0, 0
BEGIN DESCRIPTION:
Multiple Run
END DESCRIPTION:

--- Hudgens Branch.f01 (steady flow) ---

Flow Title=Multiple
Number of Profiles=7
Profile Names=10-year,25-year,50-year,1pct_min,100-year,1pct_plu,500-year
River Rch & RM= Hudgens Branch,Reach-1,1631
     385     513     616     368     734    1465    1042
River Rch & RM= Hudgens Branch,Reach-1,21
     910    1271    1574     965    1925    3842    2883
Boundary for River Rch & Prof#=Hudgens Branch,Reach-1,1
Up Type=0
Dn Type=3
Dn Slope=0.005
Boundary for River Rch & Prof#=Hudgens Branch,Reach-1,2
Up Type=0
Dn Type=3
Dn Slope=0.005
Boundary for River Rch & Prof#=Hudgens Branch,Reach-1,3
Up Type=0
Dn Type=3
Dn Slope=0.005
Boundary for River Rch & Prof#=Hudgens Branch,Reach-1,4
Up Type=0
Dn Type=3
Dn Slope=0.005
Boundary for River Rch & Prof#=Hudgens Branch,Reach-1,5
Up Type=0
Dn Type=3
Dn Slope=0.005
Boundary for River Rch & Prof#=Hudgens Branch,Reach-1,6
Up Type=0
Dn Type=3
Dn Slope=0.005
Boundary for River Rch & Prof#=Hudgens Branch,Reach-1,7
Up Type=0
Dn Type=3
Dn Slope=0.005

--- Hudgens Branch.g01 (geometry) ---

Geom Title=Existing Conditions

River Reach=Hudgens Branch,Reach-1
Reach XY= 30
      2399879.00      7032160.00      2399834.23      7032164.92
      2399824.63      7032208.21      2399790.13      7032250.22
      2399787.96      7032267.00      2399826.15      7032304.15
      2399872.87      7032312.54      2399888.63      7032320.80
      2399976.58      7032404.46      2400073.02      7032412.36
      2400122.94      7032451.86      2400144.22      7032459.48
      2400377.53      7032463.55      2400476.71      7032554.15
      2400527.26      7032564.19      2400576.80      7032603.92
      2400627.28      7032614.16      2400676.81      7032653.90
      2400735.06      7032668.14      2400876.57      7032804.48
      2400899.06      7032809.87      2400963.78      7032810.53
      2400985.17      7032817.86      2401119.32      7032949.24
      2401135.03      7032957.50      2401181.17      7032966.14
      2401230.58      7033006.18      2401323.02      7033012.36
      2401389.50      7033058.79      2401579.00      7033060.00

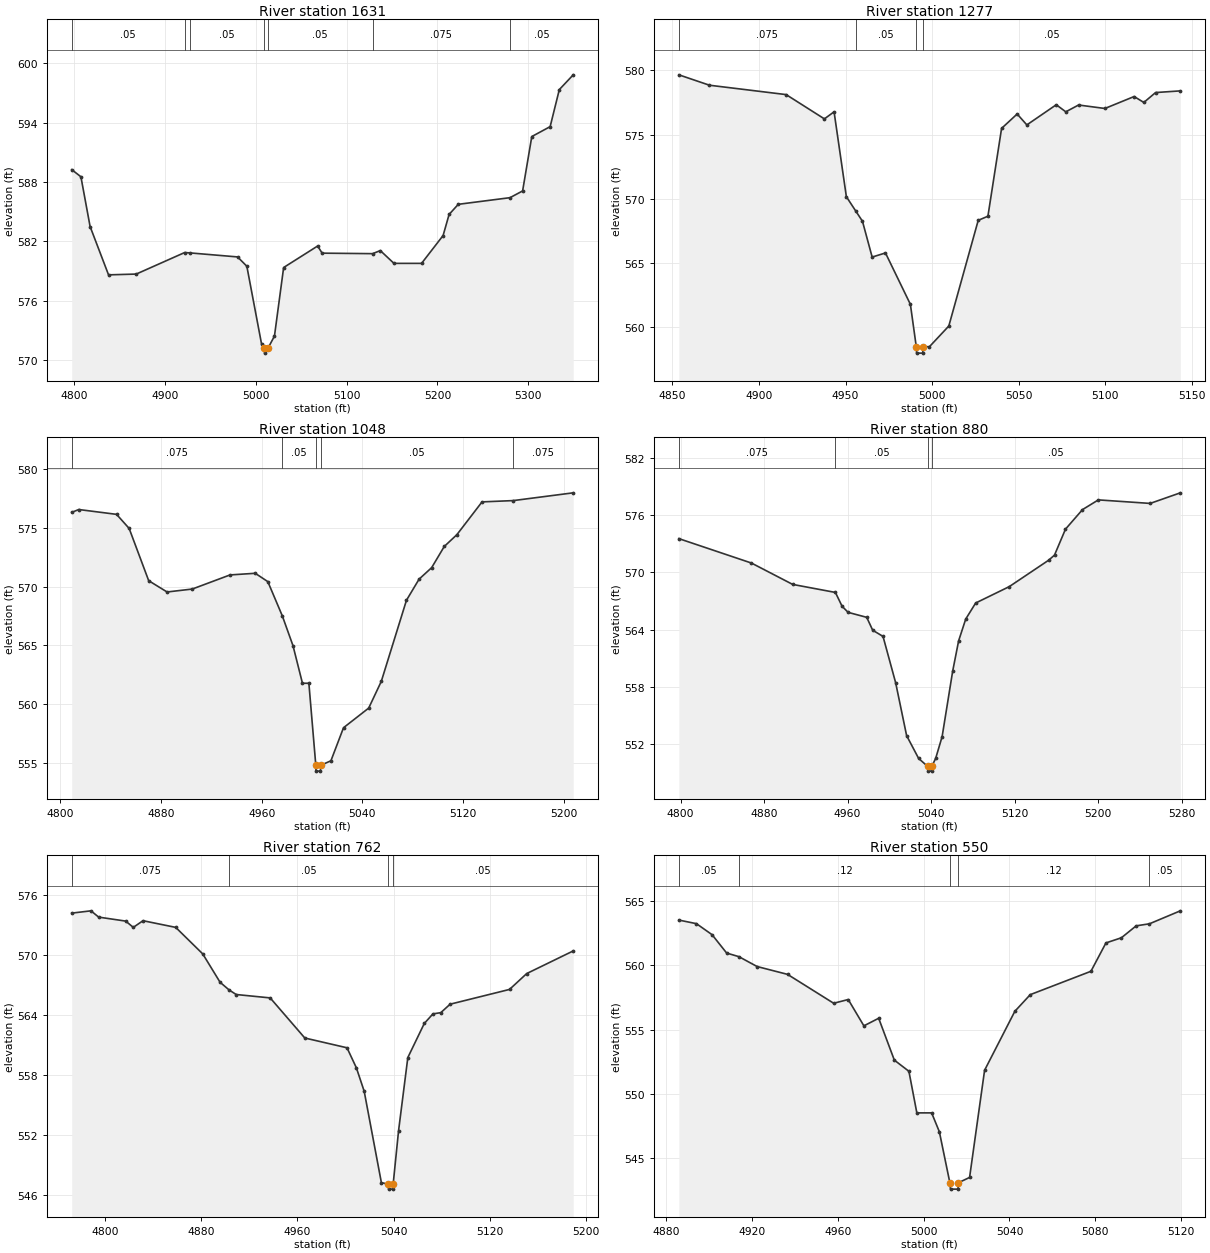
Type RM Length L Ch R = 1,1631,354,354,354
BEGIN DESCRIPTION:
Hudgens Branch 6.0
END DESCRIPTION:
XS GIS Cut Line= 3
      2400129.01      7032659.96      2400170.56      7032414.16
      2400215.48      7032114.90
#Sta/Elev= 30
  4797.6  589.25  4807.7  588.53  4817.8  583.51  4838.1  578.63  4868.6  578.71
  4921.8  580.88  4927.2  580.85  4980.1  580.44  4990.3  579.50  5006.5  571.65
  5009.6  571.23  5009.8  570.73  5013.6  571.23  5020.7  572.45  5030.8  579.37
  5068.2  581.54  5073.2  580.82  5128.7  580.77  5137.2  581.08  5152.2  579.79
  5182.6  579.79  5206.3  582.60  5212.9  584.73  5223.0  585.75  5279.9  586.42
  5293.8  587.10  5303.9  592.59  5324.1  593.59  5334.2  597.33  5349.5  598.82
#Mann=7,-1,0
  4797.6    0.05       0  4921.8   0.075       0  4927.2    0.05       0
  5009.6    0.05       0  5013.6    0.05       0  5128.7   0.075       0
  5279.9    0.05       0
Bank Sta=5009.6,5013.6
Exp/Cntr=0.3,0.1

Type RM Length L Ch R = 1,1277,229,229,229
BEGIN DESCRIPTION:
Hudgens Branch 5.0
END DESCRIPTION:
XS GIS Cut Line= 3
      2400412.94      7032685.68      2400479.00      7032560.00
      2400543.81      7032427.15
#Sta/Elev= 30
  4853.7  579.65  4871.4  578.84  4915.7  578.11  4937.8  576.22  4943.4  576.77
  4950.5  570.16  4955.9  569.05  4959.8  568.25  4965.4  565.46  4973.1  565.78
  4987.5  561.78  4990.9  558.48  4991.1  557.98  4994.6  557.98  4994.9  558.48
  4998.5  558.48  5009.7  560.09  5026.7  568.32  5032.3  568.64  5040.2  575.48
  5049.2  576.60  5054.8  575.75  5071.8  577.32  5077.3  576.77  5084.7  577.30
  5099.9  577.03  5116.8  577.96  5122.4  577.50  5129.2  578.27  5143.5  578.40
#Mann=4,-1,0
  4853.7   0.075       0  4955.9    0.05       0  4990.9   0.033       0
  4994.9    0.05       0
Bank Sta=4990.9,4994.9
Exp/Cntr=0.3,0.1

Type RM Length L Ch R = 1,1048,168,168,168
BEGIN DESCRIPTION:
Hudgens Branch 4.0
END DESCRIPTION:
XS GIS Cut Line= 3
      2400671.52      7032845.60      2400679.00      7032660.00
      2400677.96      7032447.55
#Sta/Elev= 30
  4809.2  576.31  4814.8  576.55  4844.8  576.14  4854.8  574.94  4870.3  570.50
  4884.9  569.54  4904.9  569.79  4934.9  570.99  4954.9  571.13  4964.9  570.42
  4976.4  567.51  4984.9  564.97  4992.4  561.78  4997.5  561.78  5003.0  554.81
  5003.2  554.31  5006.7  554.31  5007.0  554.81  5015.0  555.19  5025.0  558.00
  5045.0  559.67  5055.0  561.94  5075.0  568.84  5085.0  570.63  5095.0  571.61
  5105.0  573.41  5115.0  574.41  5135.0  577.20  5159.8  577.31  5207.4  577.97
#Mann=5,-1,0
  4809.2   0.075       0  4976.4    0.05       0  5003.0   0.033       0
  5007.0    0.05       0  5159.8   0.075       0
Bank Sta=5003,5007
Exp/Cntr=0.3,0.1

Type RM Length L Ch R = 1,880,118,118,118
BEGIN DESCRIPTION:
Hudgens Branch 3.5
END DESCRIPTION:
XS GIS Cut Line= 4
      2400741.26      7032932.54      2400799.21      7032771.57
      2400855.01      7032666.41      2400911.88      7032485.05
#Sta/Elev= 30
  4798.4  573.53  4867.9  570.97  4907.4  568.73  4948.3  567.89  4954.7  566.44
  4960.5  565.80  4978.3  565.28  4984.0  563.93  4993.9  563.28  5006.0  558.42
  5016.5  552.88  5028.0  550.49  5036.6  549.66  5036.9  549.16  5040.4  549.16
  5040.6  549.66  5044.3  550.49  5050.5  552.78  5060.6  559.64  5066.3  562.82
  5073.1  565.10  5082.6  566.78  5114.8  568.50  5152.4  571.26  5158.1  571.80
  5168.6  574.52  5184.9  576.57  5200.1  577.59  5249.7  577.22  5278.6  578.33
#Mann=4,-1,0
  4798.4   0.075       0  4948.3    0.05       0  5036.6    0.05       0
  5040.6    0.05       0
Bank Sta=5036.6,5040.6
Exp/Cntr=0.3,0.1

Type RM Length L Ch R = 1,762,212,212,212
BEGIN DESCRIPTION:
Hudgens Branch 3.0
END DESCRIPTION:
XS GIS Cut Line= 3
      2400731.63      7032955.04      2400889.34      7032830.58
      2401028.86      7032665.31
#Sta/Elev= 30
  4772.3  574.21  4788.3  574.44  4794.7  573.81  4817.2  573.41  4823.5  572.78
  4831.6  573.45  4858.8  572.78  4881.3  570.12  4895.7  567.28  4903.2  566.51
  4909.1  566.05  4937.4  565.71  4966.2  561.69  5001.3  560.71  5009.1  558.70
  5015.6  556.35  5029.9  547.19  5035.7  547.04  5035.9  546.54  5039.4  546.54
  5039.7  547.04  5044.2  552.40  5051.9  559.73  5065.6  563.15  5072.8  564.11
  5079.3  564.23  5087.1  565.08  5136.5  566.56  5150.8  568.15  5189.5  570.42
#Mann=4,-1,0
  4772.3   0.075       0  4903.2    0.05       0  5035.7    0.05       0
  5039.7    0.05       0
Bank Sta=5035.7,5039.7
Exp/Cntr=0.3,0.1

Type RM Length L Ch R = 1,550,234,234,234
BEGIN DESCRIPTION:
Hudgens Branch 2.0
END DESCRIPTION:
XS GIS Cut Line= 3
      2401000.96      7032993.67      2401079.00      7032910.00
      2401162.01      7032824.06
#Sta/Elev= 30
  4885.8  563.53  4894.0  563.25  4901.3  562.39  4908.1  560.96  4913.8  560.68
  4922.3  559.91  4936.5  559.30  4958.0  557.05  4964.8  557.34  4972.1  555.29
  4979.0  555.88  4986.3  552.62  4993.1  551.75  4996.8  548.51  5003.7  548.51
  5007.3  547.04  5012.2  543.07  5012.5  542.57  5016.0  542.57  5016.2  543.07
  5021.4  543.48  5028.4  551.83  5042.5  556.42  5049.7  557.72  5078.0  559.54
  5085.0  561.75  5092.2  562.15  5099.1  563.08  5105.3  563.24  5119.7  564.25
#Mann=5,-1,0
  4885.8    0.05       0  4913.8    0.12       0  5012.2    0.07       0
  5016.2    0.12       0  5105.3    0.05       0
Bank Sta=5012.2,5016.2
Exp/Cntr=0.3,0.1

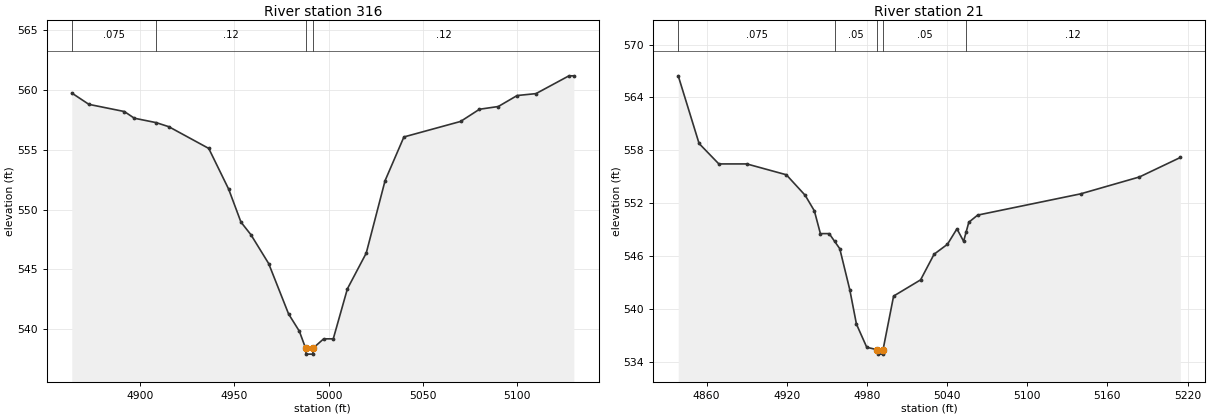
Type RM Length L Ch R = 1,316,295,295,295
BEGIN DESCRIPTION:
Hudgens Branch 1.0
END DESCRIPTION:
XS GIS Cut Line= 3
      2401233.77      7033138.58      2401279.00      7033010.00
      2401284.22      7032879.91
#Sta/Elev= 30
  4863.7  559.76  4872.8  558.81  4891.6  558.21  4896.9  557.65  4908.5  557.28
  4915.2  556.94  4936.4  555.12  4947.0  551.70  4953.5  548.95  4958.8  547.89
  4968.2  545.48  4978.8  541.25  4984.5  539.81  4987.8  538.39  4988.1  537.89
  4991.6  537.89  4991.8  538.39  4997.4  539.17  5002.5  539.17  5010.0  543.36
  5020.0  546.35  5030.0  552.42  5040.0  556.08  5070.1  557.38  5080.1  558.40
  5090.1  558.63  5100.1  559.55  5110.1  559.71  5127.6  561.20  5130.2  561.20
#Mann=4,-1,0
  4863.7   0.075       0  4908.5    0.12       0  4987.8    0.07       0
  4991.8    0.12       0
Bank Sta=4987.8,4991.8
Exp/Cntr=0.3,0.1

Type RM Length L Ch R = 1,21,0,0,0
BEGIN DESCRIPTION:
Hudgens Branch 0.3
END DESCRIPTION:
XS GIS Cut Line= 4
      2401461.25      7033173.97      2401551.41      7033110.65
      2401564.98      7033003.29      2401491.89      7032863.86
#Sta/Elev= 30
  4838.8  566.46  4854.4  558.78  4869.2  556.46  4890.1  556.46  4919.7  555.23
  4933.8  552.90  4940.7  551.13  4945.2  548.55  4951.8  548.55  4955.9  547.66
  4959.7  546.84  4967.2  542.18  4972.2  538.27  4979.9  535.65  4987.7  535.37
  4988.1  534.87  4991.7  534.87  4992.1  535.37  5000.0  541.46  5020.2  543.30
  5030.3  546.21  5040.3  547.34  5047.4  549.09  5052.4  547.68  5054.2  548.68
  5056.3  549.84  5062.9  550.65  5139.9  553.06  5184.0  554.98  5214.6  557.19
#Mann=5,-1,0
  4838.8   0.075       0  4955.9    0.05       0  4987.7    0.05       0
  4992.1    0.05       0  5054.2    0.12       0
Bank Sta=4987.7,4992.1
Exp/Cntr=0.3,0.1

Chan Stop Cuts=-1