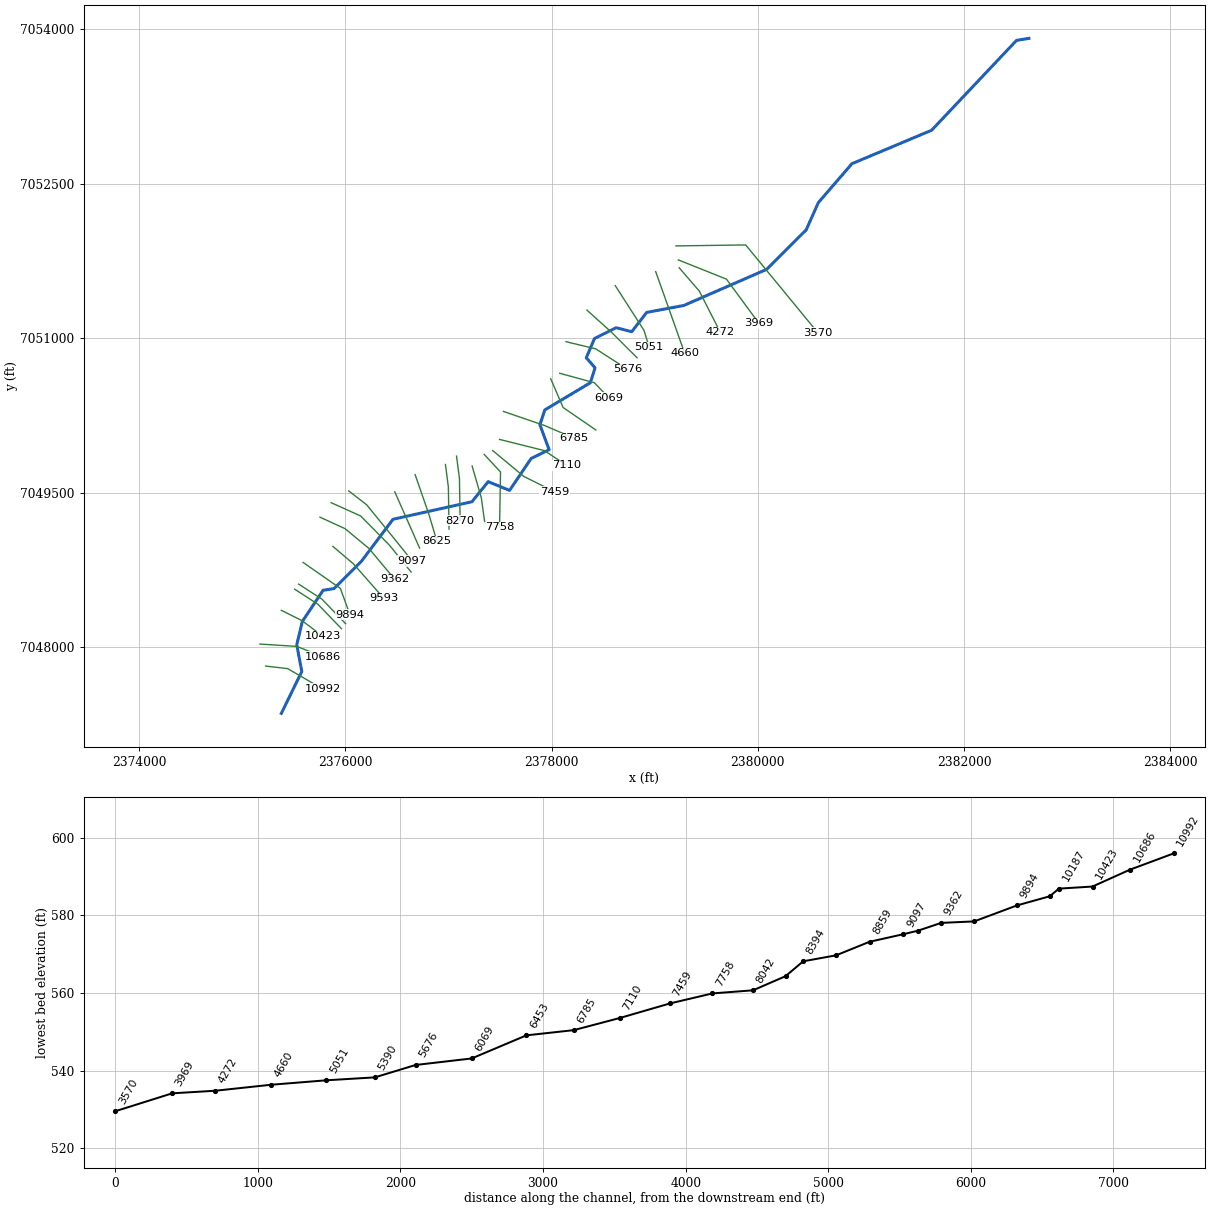
--- Indian Cr at Grapevine Lake.prj (project) ---

Proj Title=Indian Cr at Grapevine Lake Base Level Engineering
Current Plan=p01
Default Exp/Contr=0.3,0.1
English Units
Geom File=g01
Flow File=f01
Plan File=p01
Y Axis Title=Elevation
X Axis Title(PF)=Main Channel Distance
X Axis Title(XS)=Station
BEGIN DESCRIPTION:
Indian Cr at Grapevine Lake
END DESCRIPTION:
DSS Export Rating Curves= 0
DSS Export Rating Curve Sorted= 0
DSS Export Volume Flow Curves= 0
DXF OffsetX= 0
DXF OffsetY= 0
DXF ScaleX= 1
DXF ScaleY= 10

--- Indian Cr at Grapevine Lake.p01 (plan) ---

Plan Title=Multiple Run
Program Version=4.10
Short Identifier=Multiple
Geom File=g01
Flow File=f01
Subcritical Flow
K Sum by GR= 0
Std Step Tol= 0.01
Critical Tol= 0.01
Num of Std Step Trials= 20
Max Error Tol= 0.3
Flow Tol Ratio= 0.001
Split Flow NTrial= 30
Split Flow Tol= 0.02
Split Flow Ratio= 0.02
Log Output Level= 0
Friction Slope Method= 1
Unsteady Friction Slope Method= 2
Unsteady Bridges Friction Slope Method= 1
Parabolic Critical Depth
Global Vel Dist= 1 , 1 , 1
Global Log Level= 0
CheckData=True
Encroach Param=-1 ,0,0, 0
BEGIN DESCRIPTION:
Multiple Run
END DESCRIPTION:
Computation Interval=1HOUR
Output Interval=1HOUR
Run HTab= 0
Run UNet= 0
Run PostProcess= 0
Run WQNet= 0
UNET Theta= 1
UNET Theta Warmup= 1
UNET ZTol= 0.02
UNET ZSATol= 0.05
UNET MxIter= 20
UNET MaxInSteps= 0
UNET DtIC= 0
UNET DtMin= 0
UNET MaxCRTS= 20
UNET WFStab= 2
UNET SFStab= 1
UNET WFX= 1
UNET SFX= 1
UNET DSS MLevel= 4
UNET DZMax Abort= 100
UNET Convert EG Bridges= 0
UNET Use Existing IB Tables=-1
UNET Froude Reduction=False
UNET Froude Limit= 1
UNET Froude Power= 10
UNET Time Slicing=0,0, 5
UNET Junction Losses=0
Instantaneous Interval=1HOUR
Write IC File= 0
Write IC File at Sim End=0
Echo Input=False
Echo Parameters=False
Echo Output=False
Write Detailed= 0
WQ AD Non Conservative
WQ ULTIMATE=-1
WQ Max Comp Step=1HOUR
WQ Output Interval=15MIN
WQ Output Selected Increments= 0
WQ Output face flow=0
WQ Output face velocity=0
WQ Output face area=0
WQ Output face dispersion=0
WQ Output cell volume=0
WQ Output cell surface area=0
WQ Output cell continuity=0
WQ Output cumulative cell continuity=0
WQ Output face conc=0
WQ Output face dconc_dx=0
WQ Output face courant=0
WQ Output face peclet=0
WQ Output face adv mass=0
WQ Output face disp mass=0
WQ Output cell mass=0
WQ Output cell source sink temp=0
WQ Output cell source sink nsm=0
WQ Output MaxMinRange=-1
WQ Daily Max Min Mean=-1
WQ Daily Range=0
WQ Daily Time=0
WQ Create Restart=0
WQ Fixed Restart=0
WQ System Summary=0
WQ Use Fixed Temperature=0
Sorting and Armoring Iterations= 10
XS Update Threshold= 0.02
Hydraulics Update Threshold= 0.02
Energy Slope Method= 1
Volume Change Method= 0
XS Weighting Method= 0
Number of US Weighted Cross Sections= 1
Number of DS Weighted Cross Sections= 1
Upstream XS Weight=0.25
Main XS Weight=0.5
Downstream XS Weight=0.25
Number of DS XS's Weighted with US Boundary= 1
Upstream Boundary Weight= 1
Weight of XSs Associated with US Boundary= 0
Number of US XS's Weighted with DS Boundary= 1
Downstream Boundary Weight= 0.5
Weight of XSs Associated with DS Boundary= 0.5
Sediment Output Level= 4
Mass or Volume Output= 0
Output Increment Type= 1
Profile and TS Output Increment= 10
XS Output Flag= 0
XS Output Increment= 10
Disregard all LS=0
Disregard all Conn=0
Disregard all Breaches=0
Disregard all Pumps=0

--- Indian Cr at Grapevine Lake.f01 (steady flow) ---

Flow Title=Multiple
Number of Profiles=7
Profile Names=10-year,25-year,50-year,1pct_min,100-year,1pct_plu,500-year
River Rch & RM= Indian Cr at Gra,Reach-1,10992
     667     919    1127     687    1370    2733    2021
River Rch & RM= Indian Cr at Gra,Reach-1,7459
     610     838    1028     626    1249    2492    1848
Boundary for River Rch & Prof#=Indian Cr at Gra,Reach-1,1
Up Type=0
Dn Type=3
Dn Slope=0.005
Boundary for River Rch & Prof#=Indian Cr at Gra,Reach-1,2
Up Type=0
Dn Type=3
Dn Slope=0.005
Boundary for River Rch & Prof#=Indian Cr at Gra,Reach-1,3
Up Type=0
Dn Type=3
Dn Slope=0.005
Boundary for River Rch & Prof#=Indian Cr at Gra,Reach-1,4
Up Type=0
Dn Type=3
Dn Slope=0.005
Boundary for River Rch & Prof#=Indian Cr at Gra,Reach-1,5
Up Type=0
Dn Type=3
Dn Slope=0.005
Boundary for River Rch & Prof#=Indian Cr at Gra,Reach-1,6
Up Type=0
Dn Type=3
Dn Slope=0.005
Boundary for River Rch & Prof#=Indian Cr at Gra,Reach-1,7
Up Type=0
Dn Type=3
Dn Slope=0.005

--- Indian Cr at Grapevine Lake.g01 (geometry) ---

Geom Title=Existing Conditions
Program Version=4.10

River Reach=Indian Cr at Gra,Reach-1
Reach XY= 30
        2375379.        7047360.      2375577.37      7047766.04
      2375528.57      7048025.18      2375582.41      7048251.56
      2375784.47      7048554.74      2375889.12      7048570.38
      2376156.14      7048836.16      2376462.29      7049243.37
      2377227.54      7049413.54      2377384.85      7049608.46
      2377592.38      7049523.52      2377801.85      7049833.84
      2377976.03      7049918.32      2377886.53      7050159.99
      2377934.24      7050304.56      2378375.84      7050568.34
      2378421.18      7050713.42      2378336.34       7050809.9
      2378415.28      7050996.77      2378625.59      7051102.19
      2378777.51      7051063.46      2378922.05      7051250.81
      2379282.33      7051318.01      2380085.06      7051668.14
      2380468.22      7052050.32      2380586.86      7052316.17
      2380912.32      7052693.36      2381685.06      7053018.14
      2382508.84      7053890.38        2382629.        7053910.

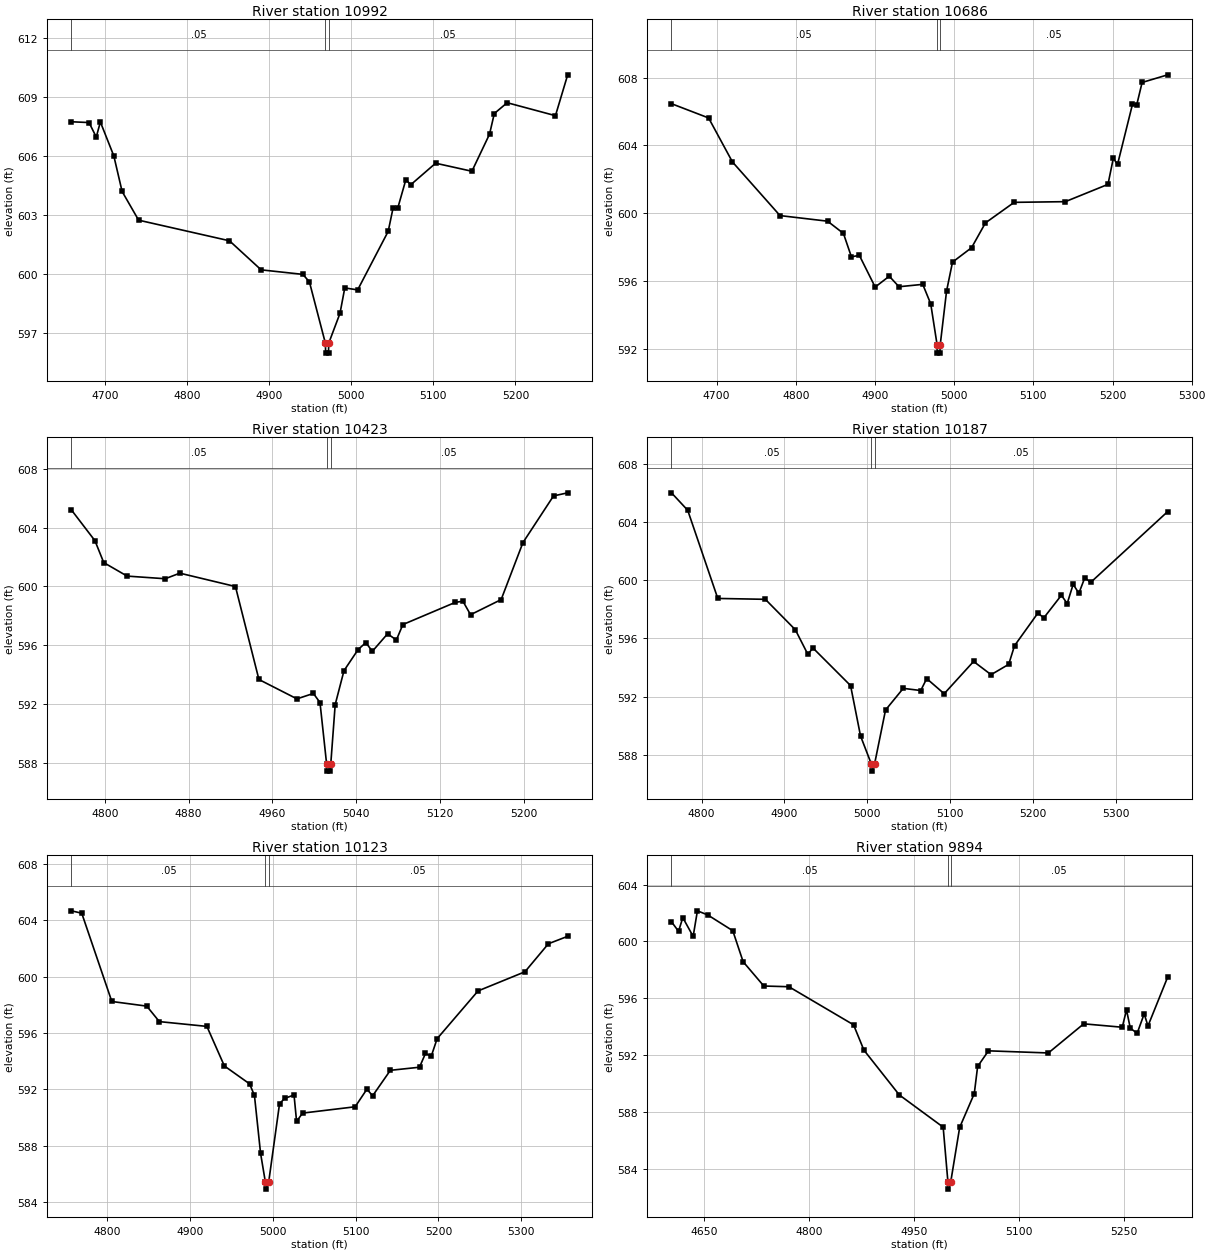
Type RM Length L Ch R = 1 ,10992   ,306,306,306
BEGIN DESCRIPTION:
Indian Cr at Grapevine Lake 27.0
END DESCRIPTION:
XS GIS Cut Line= 3
      2375227.74      7047818.87      2375439.58      7047794.56
       2375778.2      7047598.33
#Sta/Elev= 30
    4659  607.73  4680.4  607.69  4689.2  606.95  4694.2  607.72  4710.6  605.99
  4720.7  604.18  4740.8  602.72  4851.5  601.67  4890.1  600.19  4940.9  599.96
  4948.9  599.58  4968.4  596.45  4968.7  595.95  4972.2  595.95  4972.4  596.45
  4986.2  597.98    4992  599.27  5007.7  599.17  5044.9  602.15  5050.8  603.33
  5056.6  603.34  5066.5  604.79  5072.3  604.52  5102.7  605.62  5146.9  605.21
  5168.4   607.1  5174.2  608.15  5189.9   608.7  5248.7  608.04  5263.6  610.12
#Mann= 3 ,-1 , 0
    4659     .05       0  4968.4    .033       0  4972.4     .05       0
Bank Sta=4968.4,4972.4
XS Rating Curve= 0 ,0
Exp/Cntr=0.3,0.1

Type RM Length L Ch R = 1 ,10686   ,263,263,263
BEGIN DESCRIPTION:
Indian Cr at Grapevine Lake 26.0
END DESCRIPTION:
XS GIS Cut Line= 3
      2375172.19      7048032.43        2375529.        7048010.
      2375779.03      7047909.99
#Sta/Elev= 30
  4642.9  606.46  4689.8  605.62  4719.9  603.03    4780  599.87  4840.1  599.54
  4860.1  598.82  4870.2  597.44  4880.2  597.53  4900.2  595.66    4918   596.3
  4930.3  595.68  4960.3  595.82  4970.4  594.67  4978.4  592.27  4978.6  591.77
  4982.1  591.77  4982.4  592.27  4990.4  595.43  4997.9  597.13    5022  597.98
  5039.5  599.44  5075.8  600.65  5140.4  600.69  5194.3  601.71    5201  603.24
  5206.4  602.89  5225.2  606.42  5230.6  606.39  5237.4  607.71  5269.7  608.16
#Mann= 3 ,-1 , 0
  4642.9     .05       0  4978.4    .033       0  4982.4     .05       0
Bank Sta=4978.4,4982.4
XS Rating Curve= 0 ,0
Exp/Cntr=0.3,0.1

Type RM Length L Ch R = 1 ,10423   ,236,236,236
BEGIN DESCRIPTION:
Indian Cr at Grapevine Lake 25.0
END DESCRIPTION:
XS GIS Cut Line= 3
      2375378.99      7048360.01        2375579.        7048260.
      2375778.98      7048110.01
#Sta/Elev= 30
  4768.2   605.2  4790.6  603.11    4799  601.62  4821.3   600.7  4857.7  600.52
  4871.6   600.9  4924.7  599.99  4947.1  593.66  4983.4  592.34  4999.1  592.71
  5005.4  592.09  5011.7  587.92  5011.9  587.42  5015.4  587.42  5015.7  587.92
  5019.9  591.95  5028.3  594.26  5041.8   595.7  5049.1  596.17  5055.4  595.58
  5069.9  596.77  5078.3  596.35  5084.5   597.4  5134.5  598.91  5141.8  598.99
  5149.1  598.07  5178.3   599.1  5199.1  602.98  5228.3  606.16  5241.8  606.37
#Mann= 3 ,-1 , 0
  4768.2     .05       0  5011.7    .033       0  5015.7     .05       0
Bank Sta=5011.7,5015.7
XS Rating Curve= 0 ,0
Exp/Cntr=0.3,0.1

Type RM Length L Ch R = 1 ,10187   ,64,64,64
BEGIN DESCRIPTION:
Indian Cr at Grapevine Lake 24.2
END DESCRIPTION:
XS GIS Cut Line= 3
      2375507.32      7048565.47      2375733.02      7048419.63
      2375962.19      7048181.79
#Sta/Elev= 30
  4763.7  606.01  4783.3  604.81  4819.6  598.75    4877  598.69  4913.2   596.6
  4928.4   594.9  4934.4  595.35  4979.9  592.76  4991.9   589.3  5004.9  587.38
  5005.2  586.88  5008.9  587.38  5022.1  591.08  5043.5  592.57  5064.6  592.42
  5071.8  593.24  5092.9   592.2  5128.4  594.42  5149.5  593.51  5170.8  594.22
  5177.8   595.5  5206.1  597.75  5213.1  597.41  5234.4  598.97  5241.4   598.4
  5248.6  599.72  5255.5  599.11  5262.7  600.18  5269.7  599.85  5362.7  604.72
#Mann= 3 ,-1 , 0
  4763.7     .05       0  5004.9    .033       0  5008.9     .05       0
Bank Sta=5004.9,5008.9
XS Rating Curve= 0 ,0
Exp/Cntr=0.3,0.1

Type RM Length L Ch R = 1 ,10123   ,229,229,229
BEGIN DESCRIPTION:
Indian Cr at Grapevine Lake 24.0
END DESCRIPTION:
XS GIS Cut Line= 3
      2375547.23       7048614.1      2375772.96      7048468.25
      2376002.17      7048230.35
#Sta/Elev= 30
  4756.9  604.68  4769.3  604.51  4805.6  598.24  4847.8  597.91    4863  596.81
  4920.4  596.47  4941.5  593.66  4971.9  592.39  4977.8  591.57  4985.2  587.46
    4991  585.41  4991.2  584.91    4995  585.41  5008.1  590.97  5014.1  591.35
  5025.6   591.6  5028.7  589.72  5035.9  590.31  5099.4  590.76  5113.6  592.01
  5120.5  591.54  5141.9  593.35  5177.1  593.57  5184.3  594.55  5191.2  594.34
  5198.4   595.6  5247.8  598.99  5304.4  600.35  5332.7  602.34    5356  602.87
#Mann= 3 ,-1 , 0
  4756.9     .05       0    4991    .033       0    4995     .05       0
Bank Sta=4991,4995
XS Rating Curve= 0 ,0
Exp/Cntr=0.3,0.1

Type RM Length L Ch R = 1 ,9894    ,301,301,301
BEGIN DESCRIPTION:
Indian Cr at Grapevine Lake 23.0
END DESCRIPTION:
XS GIS Cut Line= 3
      2375590.65      7048824.18       2375951.8      7048572.43
      2376043.81      7048318.95
#Sta/Elev= 30
  4602.9  601.38    4613  600.71  4619.1  601.67  4633.9  600.35    4640  602.15
  4654.8  601.86  4690.6  600.75  4705.4  598.57    4735  596.86  4770.9  596.81
  4863.4  594.13  4878.2  592.35  4928.8   589.2  4991.6  586.93  4998.4  583.07
  4998.6  582.57  5002.4  583.07  5015.2  586.91  5036.1  589.29  5040.9   591.2
  5056.4   592.3  5142.1  592.15  5192.7   594.2  5247.8  593.96  5253.9  595.18
  5259.3   593.9  5269.1  593.53  5279.2   594.9  5284.6  594.05  5312.8  597.49
#Mann= 3 ,-1 , 0
  4602.9     .05       0  4998.4    .033       0  5002.4     .05       0
Bank Sta=4998.4,5002.4
XS Rating Curve= 0 ,0
Exp/Cntr=0.3,0.1

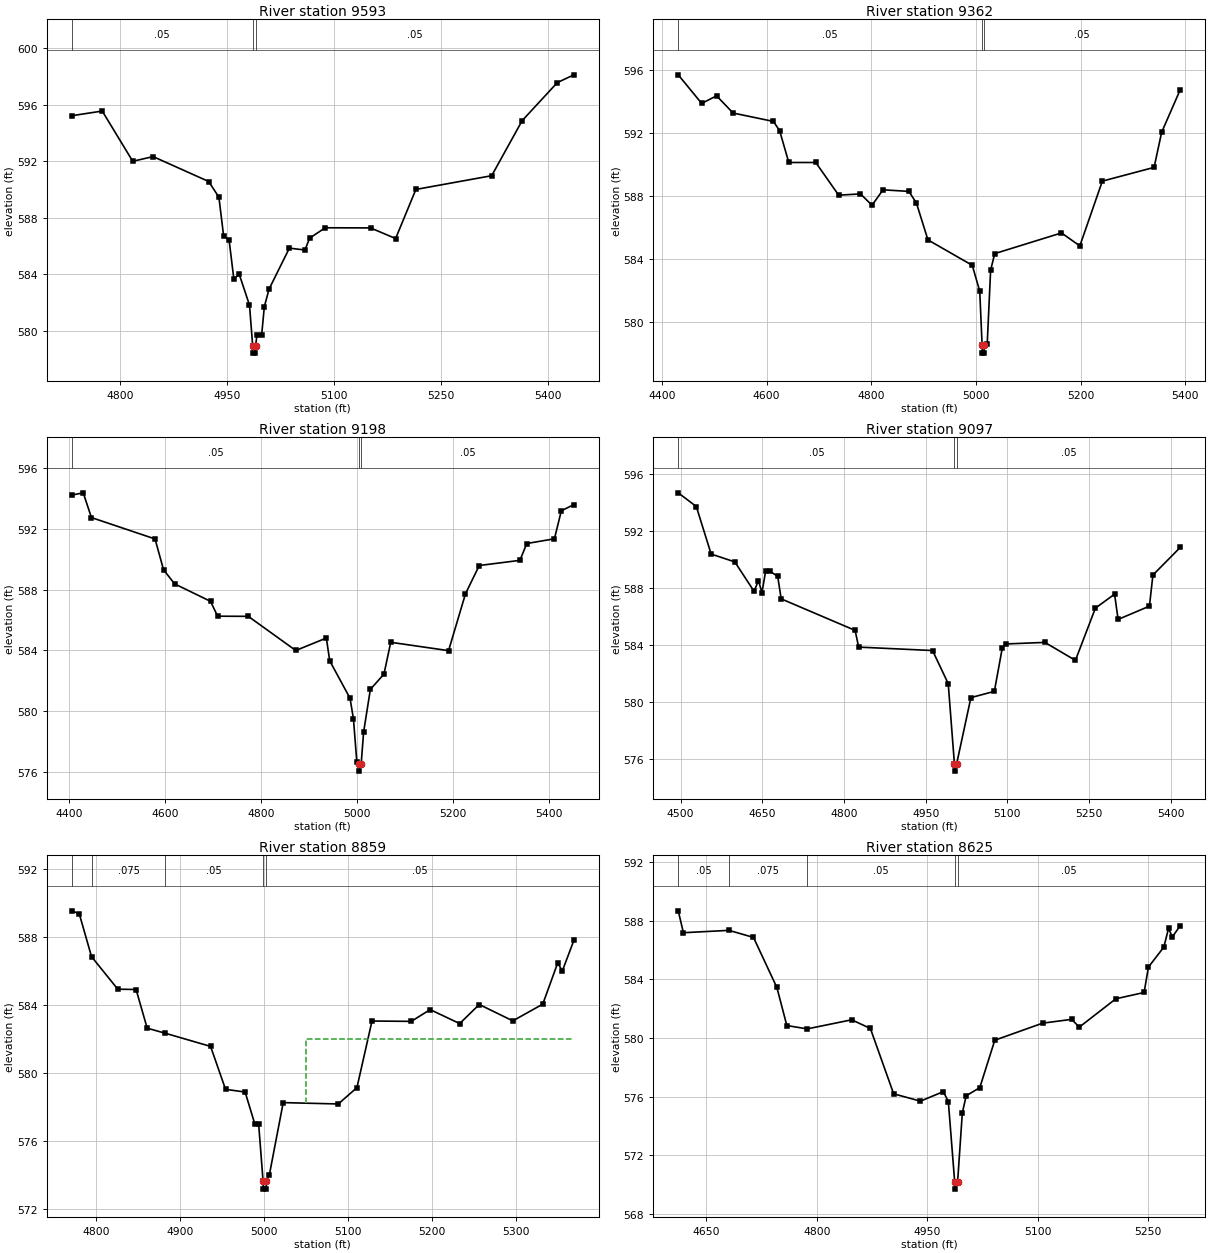
Type RM Length L Ch R = 1 ,9593    ,231,231,231
BEGIN DESCRIPTION:
Indian Cr at Grapevine Lake 22.0
END DESCRIPTION:
XS GIS Cut Line= 3
      2375878.88      7048980.45        2376079.        7048810.
      2376370.24      7048478.68
#Sta/Elev= 30
  4732.2  595.22  4774.9  595.55  4817.7     592  4846.3  592.33  4924.2  590.57
  4938.5  589.46  4945.1  586.73  4952.8  586.43  4959.4   583.7  4967.1     584
  4981.4  581.83  4985.9  578.94  4986.2  578.44  4989.7  578.44  4989.9  578.94
  4991.8  579.69  4998.4  579.69  5002.2  581.72  5008.8  582.96  5037.3  585.86
  5059.1  585.73  5065.8  586.57  5087.6   587.3  5151.1  587.29  5186.3  586.54
  5214.7  590.01    5321  590.98  5363.7  594.87    5413  597.56  5436.2  598.11
#Mann= 3 ,-1 , 0
  4732.2     .05       0  4985.9    .033       0  4989.9     .05       0
Bank Sta=4985.9,4989.9
XS Rating Curve= 0 ,0
Exp/Cntr=0.3,0.1

Type RM Length L Ch R = 1 ,9362    ,164,164,164
BEGIN DESCRIPTION:
Indian Cr at Grapevine Lake 21.0
END DESCRIPTION:
XS GIS Cut Line= 4
      2375753.63      7049263.81      2375997.22      7049152.18
        2376229.        7048960.      2376478.97      7048660.04
#Sta/Elev= 30
  4431.2  595.68    4476  593.87  4504.5  594.35  4536.1  593.26  4613.1  592.73
    4625  592.14  4642.5  590.13    4694  590.13  4737.8  588.06  4779.5  588.14
  4801.6  587.42  4822.5   588.4  4871.9   588.3  4886.3  587.57  4908.4  585.23
  4993.1  583.62  5007.4  581.98  5011.9  578.56  5012.2  578.06  5015.7  578.06
  5015.9  578.56  5021.7  578.66  5028.2  583.31    5036  584.36  5163.6  585.67
  5198.7  584.85  5241.7  588.95  5340.6  589.82    5355  592.04  5390.7  594.75
#Mann= 3 ,-1 , 0
  4431.2     .05       0  5011.9     .05       0  5015.9     .05       0
Bank Sta=5011.9,5015.9
XS Rating Curve= 0 ,0
Exp/Cntr=0.3,0.1

Type RM Length L Ch R = 1 ,9198    ,101,101,101
BEGIN DESCRIPTION:
Indian Cr at Grapevine Lake 20.7
END DESCRIPTION:
XS GIS Cut Line= 4
      2375861.62      7049404.57      2376148.47      7049275.36
      2376428.89      7048990.42      2376637.56      7048731.15
#Sta/Elev= 30
  4405.1  594.23    4429  594.38  4446.1  592.75  4578.8  591.34  4596.5  589.31
  4619.6  588.38  4694.5  587.23  4709.3  586.25  4773.3  586.24  4872.3  583.99
  4936.1  584.81  4943.1  583.31  4985.5  580.84  4992.6  579.49  4999.6  576.67
  5004.8  576.54    5005  576.04  5008.8  576.54  5013.8  578.61  5027.9  581.43
  5056.2  582.43  5070.4  584.53    5191  583.98  5226.2  587.72    5255  589.59
  5339.8  589.93  5354.2  591.04  5411.8  591.35  5426.2   593.2  5452.3   593.6
#Mann= 3 ,-1 , 0
  4405.1     .05       0  5004.8     .05       0  5008.8     .05       0
Bank Sta=5004.8,5008.8
XS Rating Curve= 0 ,0
Exp/Cntr=0.3,0.1

Type RM Length L Ch R = 1 ,9097    ,238,238,238
BEGIN DESCRIPTION:
Indian Cr at Grapevine Lake 20.0
END DESCRIPTION:
XS GIS Cut Line= 4
      2376032.11      7049518.75      2376205.84      7049384.34
       2376439.3      7049098.07      2376647.94      7048838.86
#Sta/Elev= 30
  4495.7  594.65  4528.9  593.69  4556.1  590.36  4599.6  589.81  4634.9  587.75
    4643   588.5  4649.4  587.66  4656.1  589.15  4663.9  589.16  4678.3   588.8
  4684.7  587.22  4820.5  585.01  4826.9  583.84  4962.6   583.6  4991.4  581.28
  5002.8  575.65  5003.1  575.15  5006.8  575.65    5033   580.3  5076.1  580.74
  5090.5  583.75  5096.9  584.06  5168.9  584.17  5224.9  582.91  5261.6  586.57
  5296.8  587.55  5303.3  585.78  5360.8  586.71  5367.2  588.89  5417.5  590.83
#Mann= 3 ,-1 , 0
  4495.7     .05       0  5002.8    .033       0  5006.8     .05       0
Bank Sta=5002.8,5006.8
XS Rating Curve= 0 ,0
Exp/Cntr=0.3,0.1

Type RM Length L Ch R = 1 ,8859    ,234,234,234
BEGIN DESCRIPTION:
Indian Cr at Grapevine Lake 19.0
END DESCRIPTION:
XS GIS Cut Line= 3
        2376479.        7049510.      2376568.92      7049306.72
      2376720.02      7048963.59
#Sta/Elev= 30
  4771.3  589.53  4780.2  589.36  4794.8  586.84    4826  584.93  4847.8  584.91
    4861  582.64  4882.7  582.34  4936.4  581.57  4954.2  579.05  4977.5  578.89
  4989.1     577  4993.6     577  4998.8  573.69  4999.1  573.19  5002.6  573.19
  5002.8  573.69  5006.3  574.02  5022.8  578.27  5088.3  578.19  5110.5  579.15
  5128.4  583.06  5175.1  583.04  5197.6  583.73  5232.7  582.91    5256  584.03
  5295.9  583.07  5331.5  584.05  5349.3  586.47  5354.8     586  5368.5  587.79
#Mann= 5 ,-1 , 0
  4771.3     .05       0  4794.8    .075       0  4882.7     .05       0
  4998.8    .033       0  5002.8     .05       0
#XS Ineff= 2 , 0
       0                    5050       0     582
Permanent Ineff=
       F       F
Bank Sta=4998.8,5002.8
XS Rating Curve= 0 ,0
Exp/Cntr=0.3,0.1

Type RM Length L Ch R = 1 ,8625    ,231,231,231
BEGIN DESCRIPTION:
Indian Cr at Grapevine Lake 18.0
END DESCRIPTION:
XS GIS Cut Line= 3
       2376676.4      7049676.59      2376809.18      7049294.07
      2376888.22       7049028.5
#Sta/Elev= 30
  4611.8  588.66  4618.8  587.17  4680.7  587.33    4714  586.85  4745.8  583.44
  4759.3  580.85  4786.9  580.62  4847.4  581.24  4872.8  580.65  4904.4   576.2
  4940.8   575.7  4971.9  576.35  4978.7  575.67  4987.3  570.21  4987.5  569.71
  4991.3  570.21  4997.7  574.91    5003  576.07  5021.4  576.62  5041.8  579.85
  5106.7  581.01  5146.2  581.27  5156.6  580.74  5206.2  582.67  5244.6   583.1
  5250.5  584.83  5271.4  586.19  5277.8  587.46    5283  586.88  5293.8  587.66
#Mann= 5 ,-1 , 0
  4611.8     .05       0  4680.7    .075       0  4786.9     .05       0
  4987.3    .033       0  4991.3     .05       0
Bank Sta=4987.3,4991.3
XS Rating Curve= 0 ,0
Exp/Cntr=0.3,0.1

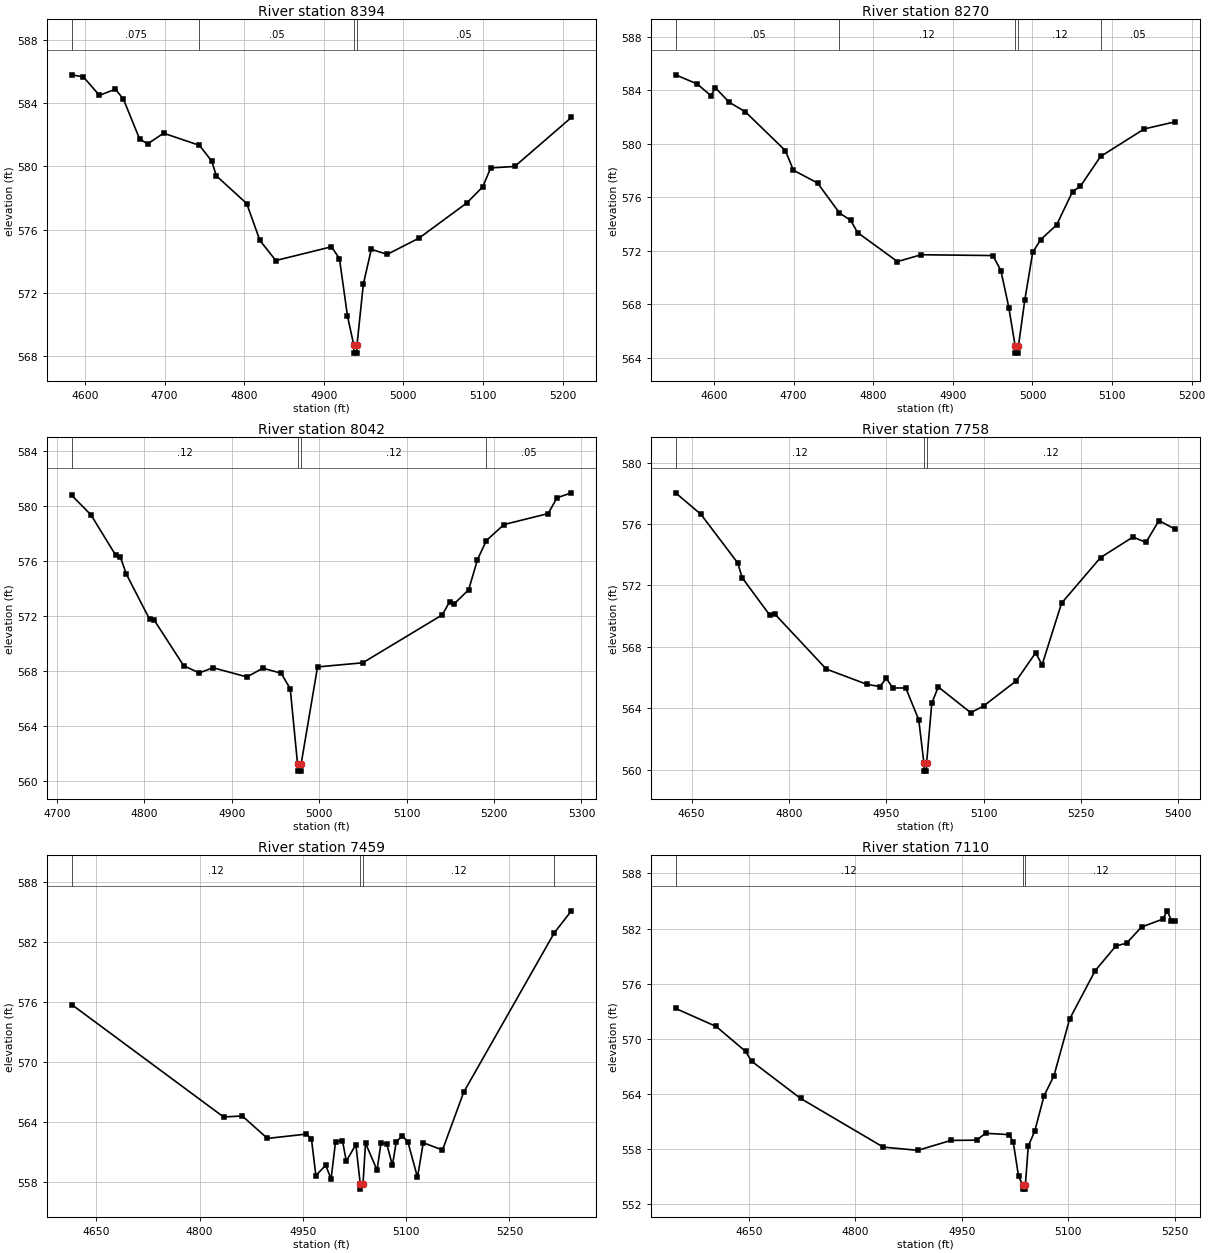
Type RM Length L Ch R = 1 ,8394    ,124,124,124
BEGIN DESCRIPTION:
Indian Cr at Grapevine Lake 17.3
END DESCRIPTION:
XS GIS Cut Line= 3
      2376970.41      7049774.56      2376998.86      7049556.47
      2377005.18      7049148.66
#Sta/Elev= 30
  4583.3  585.81    4598  585.68  4618.2  584.51  4638.3   584.9  4648.4  584.26
  4668.6  581.75  4678.7  581.43  4698.8  582.11  4743.8  581.34  4759.3  580.34
    4765  579.41  4803.2  577.65  4819.7  575.32  4839.7  574.04  4909.7  574.91
  4919.7  574.16  4929.7  570.55  4937.7  568.67    4938  568.17  4941.5  568.17
  4941.7  568.67  4949.7  572.54  4959.7  574.75  4979.7  574.43  5019.7  575.46
  5079.7  577.69  5099.7  578.71  5109.7  579.91  5139.8     580  5211.1  583.11
#Mann= 4 ,-1 , 0
  4583.3    .075       0  4743.8     .05       0  4937.7    .033       0
  4941.7     .05       0
Bank Sta=4937.7,4941.7
XS Rating Curve= 0 ,0
Exp/Cntr=0.3,0.1

Type RM Length L Ch R = 1 ,8270    ,228,228,228
BEGIN DESCRIPTION:
Indian Cr at Grapevine Lake 17.0
END DESCRIPTION:
XS GIS Cut Line= 3
       2377077.9      7049856.76      2377106.35      7049638.66
      2377112.67      7049230.85
#Sta/Elev= 30
  4551.7  585.15  4578.7  584.47  4596.3  583.58  4601.4   584.2    4619   583.1
  4639.2  582.39  4689.6  579.48  4699.7  578.01    4730  577.06  4757.5  574.82
  4771.6  574.26  4780.3  573.35  4830.3  571.18  4860.3  571.69  4950.3  571.63
  4960.3  570.51  4970.3  567.74  4978.3  564.83  4978.6  564.33  4982.1  564.33
  4982.3  564.83  4990.3  568.28  5000.3  571.87  5010.3  572.82  5030.3  573.92
  5050.3  576.41  5060.3  576.82  5085.5  579.04  5140.3   581.1  5179.5  581.64
#Mann= 5 ,-1 , 0
  4551.7     .05       0  4757.5     .12       0  4978.3     .07       0
  4982.3     .12       0  5085.5     .05       0
Bank Sta=4978.3,4982.3
XS Rating Curve= 0 ,0
Exp/Cntr=0.3,0.1

Type RM Length L Ch R = 1 ,8042    ,284,284,284
BEGIN DESCRIPTION:
Indian Cr at Grapevine Lake 16.0
END DESCRIPTION:
XS GIS Cut Line= 3
        2377229.      7049760.02      2377318.16      7049452.14
      2377352.75      7049203.66
#Sta/Elev= 30
  4717.1  580.79  4739.1  579.37  4767.5  576.42  4772.7  576.31  4779.6  575.05
  4806.3  571.75  4811.5   571.7  4845.1  568.38  4862.9  567.85  4878.7  568.23
  4917.5  567.56  4935.7   568.2  4956.6  567.83    4967   566.7  4975.4   561.2
  4975.6   560.7  4979.1   560.7  4979.4   561.2  4998.2  568.29  5049.9  568.59
  5140.8  572.08  5149.2  573.03  5154.2  572.87    5171  573.91  5181.1  576.11
  5191.2  577.49  5211.4  578.66  5261.9  579.46    5272  580.61  5288.5  580.97
#Mann= 4 ,-1 , 0
  4717.1     .12       0  4975.4     .07       0  4979.4     .12       0
  5191.2     .05       0
Bank Sta=4975.4,4979.4
XS Rating Curve= 0 ,0
Exp/Cntr=0.3,0.1

Type RM Length L Ch R = 1 ,7758    ,299,299,299
BEGIN DESCRIPTION:
Indian Cr at Grapevine Lake 15.0
END DESCRIPTION:
XS GIS Cut Line= 3
      2377346.59      7049872.62      2377504.67      7049701.89
       2377495.2      7049164.75
#Sta/Elev= 30
  4625.5  578.04  4664.5  576.64  4721.2  573.47    4728  572.51  4770.5  570.07
  4777.9  570.16  4857.7  566.55  4920.1  565.56  4940.1  565.41  4950.1  565.95
  4960.1  565.32  4980.1  565.32  5000.1  563.24  5008.1   560.4  5008.3   559.9
  5011.8   559.9  5012.1   560.4  5020.1  564.32  5030.1  565.39  5080.1  563.71
  5100.1  564.15  5150.1  565.78  5180.1  567.61  5190.1  566.83  5220.1  570.85
  5280.1  573.82  5330.1  575.16  5350.1  574.81  5370.1  576.23  5395.4  575.66
#Mann= 3 ,-1 , 0
  4625.5     .12       0  5008.1     .07       0  5012.1     .12       0
Bank Sta=5008.1,5012.1
XS Rating Curve= 0 ,0
Exp/Cntr=0.3,0.1

Type RM Length L Ch R = 1 ,7459    ,349,349,349
BEGIN DESCRIPTION:
Indian Cr at Grapevine Lake 14.0
END DESCRIPTION:
XS GIS Cut Line= 3
      2377429.02      7049909.98        2377729.        7049660.
      2378029.01        7049510.
#Sta/Elev= 30
  4614.1  575.77  4834.7  564.53    4862  564.62  4898.5  562.38  4954.5  562.81
  4962.3  562.37  4968.8  558.67  4983.1   559.7  4990.9  558.32  4997.4  562.06
  5007.4  562.17    5013  560.11  5026.9  561.76  5033.3  557.81  5033.6  557.31
  5037.3  557.81  5040.9  561.92  5057.7   559.2  5063.3   561.9  5071.7  561.84
    5080  559.69  5085.6  562.04    5094  562.63  5102.4  562.05  5116.4  558.49
  5124.8  561.95  5152.7  561.22  5183.5     567  5315.2  582.95    5340  585.14
#Mann= 4 ,-1 , 0
  4614.1     .12       0  5033.3     .07       0  5037.3     .12       0
  5315.2     .05       0
Bank Sta=5033.3,5037.3
XS Rating Curve= 0 ,0
Exp/Cntr=0.3,0.1

Type RM Length L Ch R = 1 ,7110    ,325,325,325
BEGIN DESCRIPTION:
Indian Cr at Grapevine Lake 13.0
END DESCRIPTION:
XS GIS Cut Line= 3
       2377495.2      7050018.02        2377929.        7049910.
      2378143.23       7049768.3
#Sta/Elev= 30
  4546.8  573.29    4604  571.32  4645.3  568.61  4653.8  567.54  4722.8  563.48
  4839.3  558.17    4888  557.82  4934.5   558.9  4970.6  558.93  4983.5  559.68
  5016.4  559.53  5022.4  558.71  5029.8  554.99  5035.5  554.09  5035.7  553.59
  5039.2  553.59  5039.5  554.09  5043.5  558.29  5052.5  559.88  5065.8  563.78
  5079.6  565.93  5101.8  572.14  5137.7   577.4  5166.9   580.1  5181.9   580.4
    5203  582.16  5233.1  583.03  5239.1  583.93  5245.2  582.87  5250.7  582.87
#Mann= 3 ,-1 , 0
  4546.8     .12       0  5035.5     .07       0  5039.5     .12       0
Bank Sta=5035.5,5039.5
XS Rating Curve= 0 ,0
Exp/Cntr=0.3,0.1

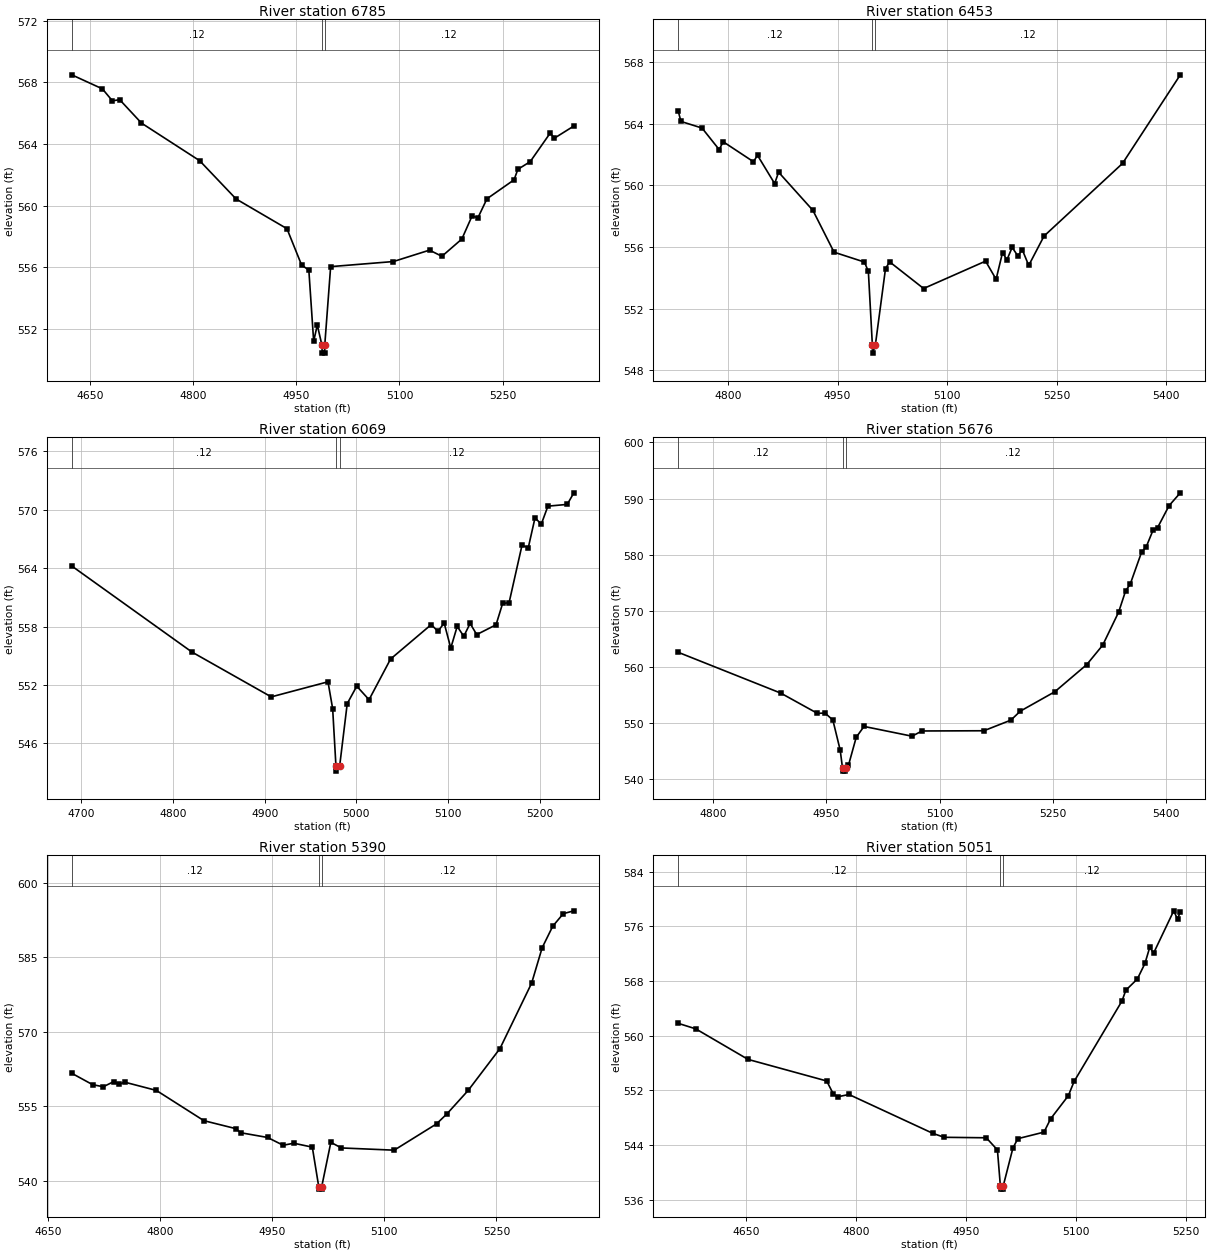
Type RM Length L Ch R = 1 ,6785    ,332,332,332
BEGIN DESCRIPTION:
Indian Cr at Grapevine Lake 12.0
END DESCRIPTION:
XS GIS Cut Line= 3
      2377533.16      7050289.89      2377937.78       7050150.8
      2378214.98       7050031.1
#Sta/Elev= 30
  4623.7  568.49  4668.2  567.58  4682.8   566.8  4693.3  566.88    4725  565.36
  4809.6  562.92  4862.5  560.44  4936.5  558.51  4957.7  556.16  4968.3  555.82
  4975.3  551.21  4980.6  552.26  4987.4  550.94  4987.7  550.44  4991.2  550.44
  4991.4  550.94    5000  556.05  5091.2  556.38  5143.7  557.12  5161.7  556.72
  5190.7  557.84  5205.4  559.32  5214.2  559.23  5227.2  560.45  5266.6  561.68
  5272.1  562.36  5290.1  562.86  5319.1  564.71  5325.2  564.38  5353.5  565.17
#Mann= 3 ,-1 , 0
  4623.7     .12       0  4987.4     .07       0  4991.4     .12       0
Bank Sta=4987.4,4991.4
XS Rating Curve= 0 ,0
Exp/Cntr=0.3,0.1

Type RM Length L Ch R = 1 ,6453    ,384,384,384
BEGIN DESCRIPTION:
Indian Cr at Grapevine Lake 11.0
END DESCRIPTION:
XS GIS Cut Line= 3
      2377991.53      7050606.01      2378111.65      7050327.83
      2378428.98      7050110.01
#Sta/Elev= 30
  4731.7  564.83  4735.4  564.16  4764.3  563.73  4787.8  562.33  4793.3  562.84
  4834.8  561.54  4840.3  561.96  4863.8  560.12  4869.2  560.86  4916.2  558.38
  4945.2  555.66  4986.8  555.02  4992.2  554.41  4997.7   549.6  4997.9   549.1
  5001.7   549.6  5015.7   554.6  5021.4  555.03  5067.9   553.3  5152.8  555.08
  5167.2   553.9    5176  555.63  5182.1  555.17  5189.2  555.97    5197  555.42
  5203.1  555.82  5211.9   554.8  5232.9  556.71  5340.4  561.43  5419.6  567.19
#Mann= 3 ,-1 , 0
  4731.7     .12       0  4997.7     .07       0  5001.7     .12       0
Bank Sta=4997.7,5001.7
XS Rating Curve= 0 ,0
Exp/Cntr=0.3,0.1

Type RM Length L Ch R = 1 ,6069    ,393,393,393
BEGIN DESCRIPTION:
Indian Cr at Grapevine Lake 10.0
END DESCRIPTION:
XS GIS Cut Line= 3
        2378079.        7050660.      2378415.14      7050568.09
      2378552.98      7050423.98
#Sta/Elev= 30
  4689.5  564.23  4820.6  555.39  4907.2  550.78  4969.1  552.33  4974.2  549.57
  4977.8  543.65    4978  543.15  4981.8  543.65  4990.1  550.09  5000.5  551.88
  5013.9  550.49  5037.4  554.67  5081.8  558.21    5089  557.52  5095.9  558.36
  5103.1   555.8  5110.1  558.02  5117.3  557.01  5124.2  558.33  5131.4  557.18
  5152.5  558.19  5159.7  560.39  5166.7  560.45  5180.8  566.35  5187.7  566.12
    5195  569.17  5201.9  568.54  5209.1  570.38  5230.2  570.56  5237.4  571.75
#Mann= 3 ,-1 , 0
  4689.5     .12       0  4977.8     .07       0  4981.8     .12       0
Bank Sta=4977.8,4981.8
XS Rating Curve= 0 ,0
Exp/Cntr=0.3,0.1

Type RM Length L Ch R = 1 ,5676    ,286,286,286
BEGIN DESCRIPTION:
Indian Cr at Grapevine Lake 9.0
END DESCRIPTION:
XS GIS Cut Line= 3
       2378140.1      7050966.42      2378427.78      7050896.87
      2378737.61       7050697.7
#Sta/Elev= 30
  4754.3  562.63    4890  555.36  4938.4  551.76  4948.6  551.81  4958.9  550.56
  4968.6   545.2  4971.7  541.97    4972  541.47  4975.5  541.47  4975.7  541.97
  4979.5  542.49  4989.8   547.5  5000.1  549.43  5063.6  547.69  5076.8  548.62
  5158.7  548.66  5194.4  550.55  5206.9  552.15  5252.5   555.6  5294.8  560.44
  5315.9   563.9    5337  569.79  5346.3   573.6  5352.2  574.72  5367.4  580.48
  5373.4  581.38  5382.6  584.41  5388.6  584.85  5403.8  588.76  5418.6  591.03
#Mann= 3 ,-1 , 0
  4754.3     .12       0  4971.7     .07       0  4975.7     .12       0
Bank Sta=4971.7,4975.7
XS Rating Curve= 0 ,0
Exp/Cntr=0.3,0.1

Type RM Length L Ch R = 1 ,5390    ,339,339,339
BEGIN DESCRIPTION:
Indian Cr at Grapevine Lake 8.0
END DESCRIPTION:
XS GIS Cut Line= 3
      2378342.42      7051273.08        2378579.        7051060.
      2378828.97      7050810.03
#Sta/Elev= 30
  4681.7   561.6  4709.7   559.3  4723.9  558.89  4738.1  559.94  4744.9  559.35
  4752.3  559.82  4794.9  558.15  4858.5  552.06  4901.1  550.46  4907.8  549.63
  4943.7  548.68  4964.6  547.11  4978.8  547.52  5003.6  546.73  5012.2  538.78
  5012.5  538.28    5016  538.28  5016.2  538.78  5028.4   547.7  5042.5  546.57
  5113.2  546.12  5169.8  551.41  5183.9  553.45  5212.2  558.15  5254.7  566.57
  5297.1  579.74  5311.2  586.87  5325.4  591.21  5339.5  593.73  5353.6   594.3
#Mann= 3 ,-1 , 0
  4681.7     .12       0  5012.2     .07       0  5016.2     .12       0
Bank Sta=5012.2,5016.2
XS Rating Curve= 0 ,0
Exp/Cntr=0.3,0.1

Type RM Length L Ch R = 1 ,5051    ,391,391,391
BEGIN DESCRIPTION:
Indian Cr at Grapevine Lake 7.0
END DESCRIPTION:
XS GIS Cut Line= 3
      2378617.46      7051510.17      2378895.66      7051077.07
      2378945.88      7050913.88
#Sta/Elev= 30
    4557  561.81    4581     561  4652.3  556.53  4759.7  553.37  4768.9  551.43
  4774.9  551.06  4790.1  551.39    4905  545.68  4920.2  545.12  4977.6  545.05
  4992.8  543.27  4996.8  538.03    4997  537.53  5000.5  537.53  5000.8  538.03
    5014  543.57  5020.7  544.92  5056.4  545.88  5065.5  547.84  5089.6  551.21
  5097.5   553.3  5162.9  565.09  5168.1  566.66  5183.8   568.3  5194.2  570.58
  5200.8  572.96    5206  572.09  5233.5  578.29  5238.7  577.07  5242.5  578.16
#Mann= 3 ,-1 , 0
    4557     .12       0  4996.8     .07       0  5000.8     .12       0
Bank Sta=4996.8,5000.8
XS Rating Curve= 0 ,0
Exp/Cntr=0.3,0.1

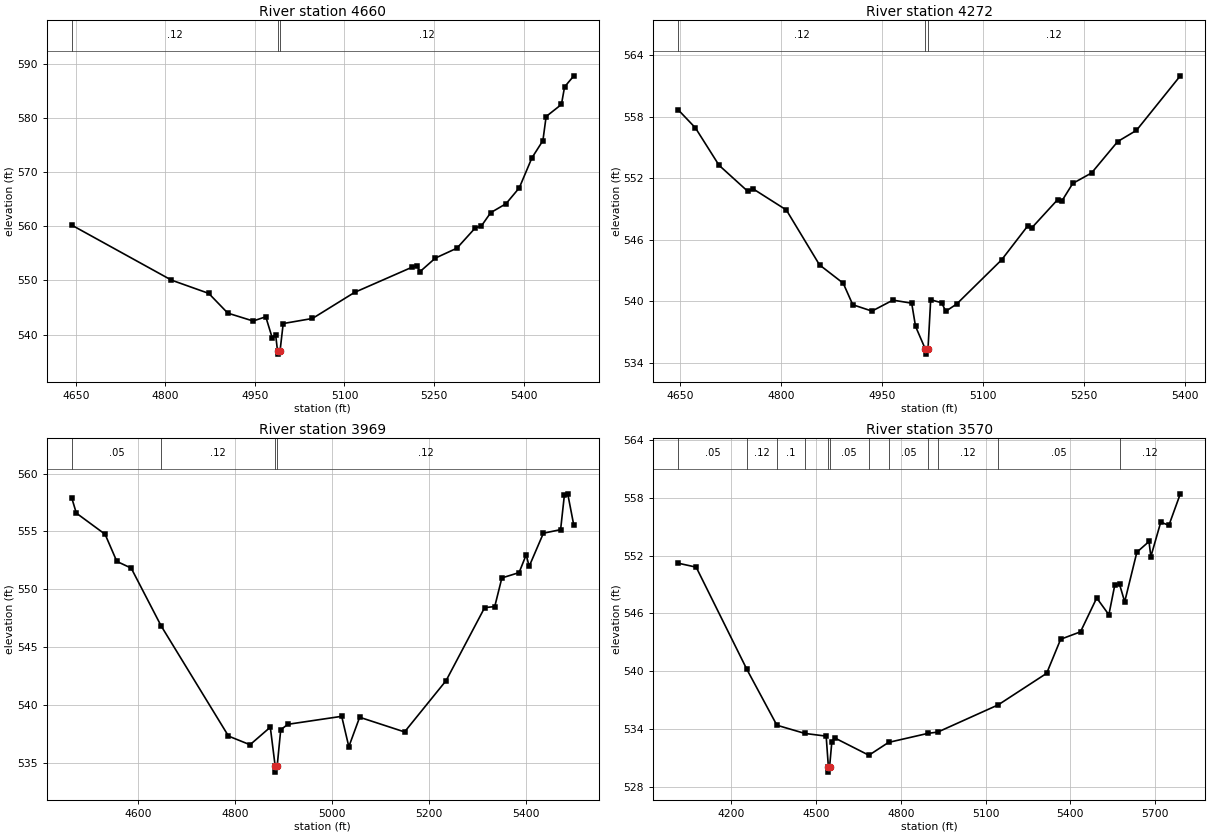
Type RM Length L Ch R = 1 ,4660    ,388,388,388
BEGIN DESCRIPTION:
Indian Cr at Grapevine Lake 6.0
END DESCRIPTION:
XS GIS Cut Line= 3
      2379009.48      7051646.07        2379129.        7051310.
      2379290.41       7050853.8
#Sta/Elev= 30
  4643.4  560.24  4810.2  550.07  4872.7  547.61  4904.6  543.96    4947   542.5
  4968.2  543.28  4978.9  539.42  4984.7  539.96    4988  536.87  4988.2  536.37
    4992  536.87  4997.4  542.03  5046.4  542.97  5116.8  547.79  5212.2  552.41
  5221.2  552.71  5226.5  551.64  5252.1  554.14  5288.3  555.98  5319.3  559.77
  5328.9  560.04  5344.8  562.55  5370.4   564.2  5392.6  567.13  5413.8  572.69
  5432.2  575.88  5437.6  580.34  5463.2  582.57  5468.5  585.83    5484  587.87
#Mann= 3 ,-1 , 0
  4643.4     .12       0    4988     .07       0    4992     .12       0
Bank Sta=4988,4992
XS Rating Curve= 0 ,0
Exp/Cntr=0.3,0.1

Type RM Length L Ch R = 1 ,4272    ,303,303,303
BEGIN DESCRIPTION:
Indian Cr at Grapevine Lake 5.0
END DESCRIPTION:
XS GIS Cut Line= 3
      2379237.09      7051684.04      2379433.09      7051456.43
      2379634.72      7051059.47
#Sta/Elev= 30
  4647.7  558.68  4673.2  556.92  4708.3  553.27  4751.1  550.72  4758.6  550.98
  4808.2  548.91  4857.5  543.55  4892.7  541.76  4906.9  539.66  4935.4  539.04
  4966.5  540.11  4994.4  539.81  5000.1  537.55  5014.6  535.34  5014.9  534.84
  5018.6  535.34  5022.6  540.15  5038.9  539.85    5045  539.02  5061.2  539.73
  5127.9  544.04  5166.8  547.36  5172.4  547.14  5211.3  549.93    5217  549.74
  5233.6   551.5  5261.5  552.52  5300.4  555.59  5328.2  556.68  5393.3     562
#Mann= 3 ,-1 , 0
  4647.7     .12       0  5014.6     .07       0  5018.6     .12       0
Bank Sta=5014.6,5018.6
XS Rating Curve= 0 ,0
Exp/Cntr=0.3,0.1

Type RM Length L Ch R = 1 ,3969    ,399,399,399
BEGIN DESCRIPTION:
Indian Cr at Grapevine Lake 4.0
END DESCRIPTION:
XS GIS Cut Line= 3
      2379229.01        7051760.      2379695.48       7051573.4
      2380011.04      7051144.24
#Sta/Elev= 30
  4463.4   557.9  4472.8  556.59  4532.1  554.76  4556.3  552.41  4585.9  551.83
  4647.6  546.83  4786.5  537.29  4830.9  536.54  4872.7  538.06  4882.8  534.67
    4883  534.17  4886.8  534.67  4894.2  537.84    4909  538.31  5019.9     539
  5034.6  536.37  5056.9  538.92  5149.5  537.65  5235.1  542.09  5314.6  548.41
  5335.4   548.5  5350.1  550.98  5385.6  551.44  5400.2  552.98  5406.4  551.98
  5435.7  554.85  5471.2  555.16  5478.9  558.12  5485.9  558.26  5498.5  555.52
#Mann= 4 ,-1 , 0
  4463.4     .05       0  4647.6     .12       0  4882.8     .07       0
  4886.8     .12       0
Bank Sta=4882.8,4886.8
XS Rating Curve= 0 ,0
Exp/Cntr=0.3,0.1

Type RM Length L Ch R = 1 ,3570    ,0,0,0
BEGIN DESCRIPTION:
Indian Cr at Grapevine Lake 3.0
END DESCRIPTION:
XS GIS Cut Line= 3
      2379205.46      7051895.85        2379882.      7051905.34
      2380580.66      7051054.93
#Sta/Elev= 30
  4012.3  551.21  4075.8   550.8  4255.4   540.2  4361.5  534.42  4460.5  533.57
  4535.9  533.29  4543.9  530.06  4544.1  529.56  4547.9  530.06  4555.9  532.67
  4565.9  533.11  4687.2  531.31  4756.7  532.64  4896.7  533.58  4930.9  533.71
  5144.9  536.53  5316.4   539.8  5365.9  543.33  5436.2   544.1  5493.6  547.61
  5536.6  545.87  5557.5  548.94  5574.3  549.03  5592.6  547.21  5635.7  552.35
  5678.7  553.46  5685.2  551.89  5720.3  555.47    5749  555.13  5789.5   558.4
#Mann= 12 ,-1 , 0
  4012.3     .05       0  4255.4     .12       0  4361.5      .1       0
  4460.5     .05       0  4543.9     .07       0  4547.9     .05       0
  4687.2      .1       0  4756.7     .05       0  4896.7      .1       0
  4930.9     .12       0  5144.9     .05       0  5574.3     .12       0
Bank Sta=4543.9,4547.9
XS Rating Curve= 0 ,0
Exp/Cntr=0.3,0.1

Chan Stop Cuts=-1
Use User Specified Reach Order=0
Composite Channel Slope=5