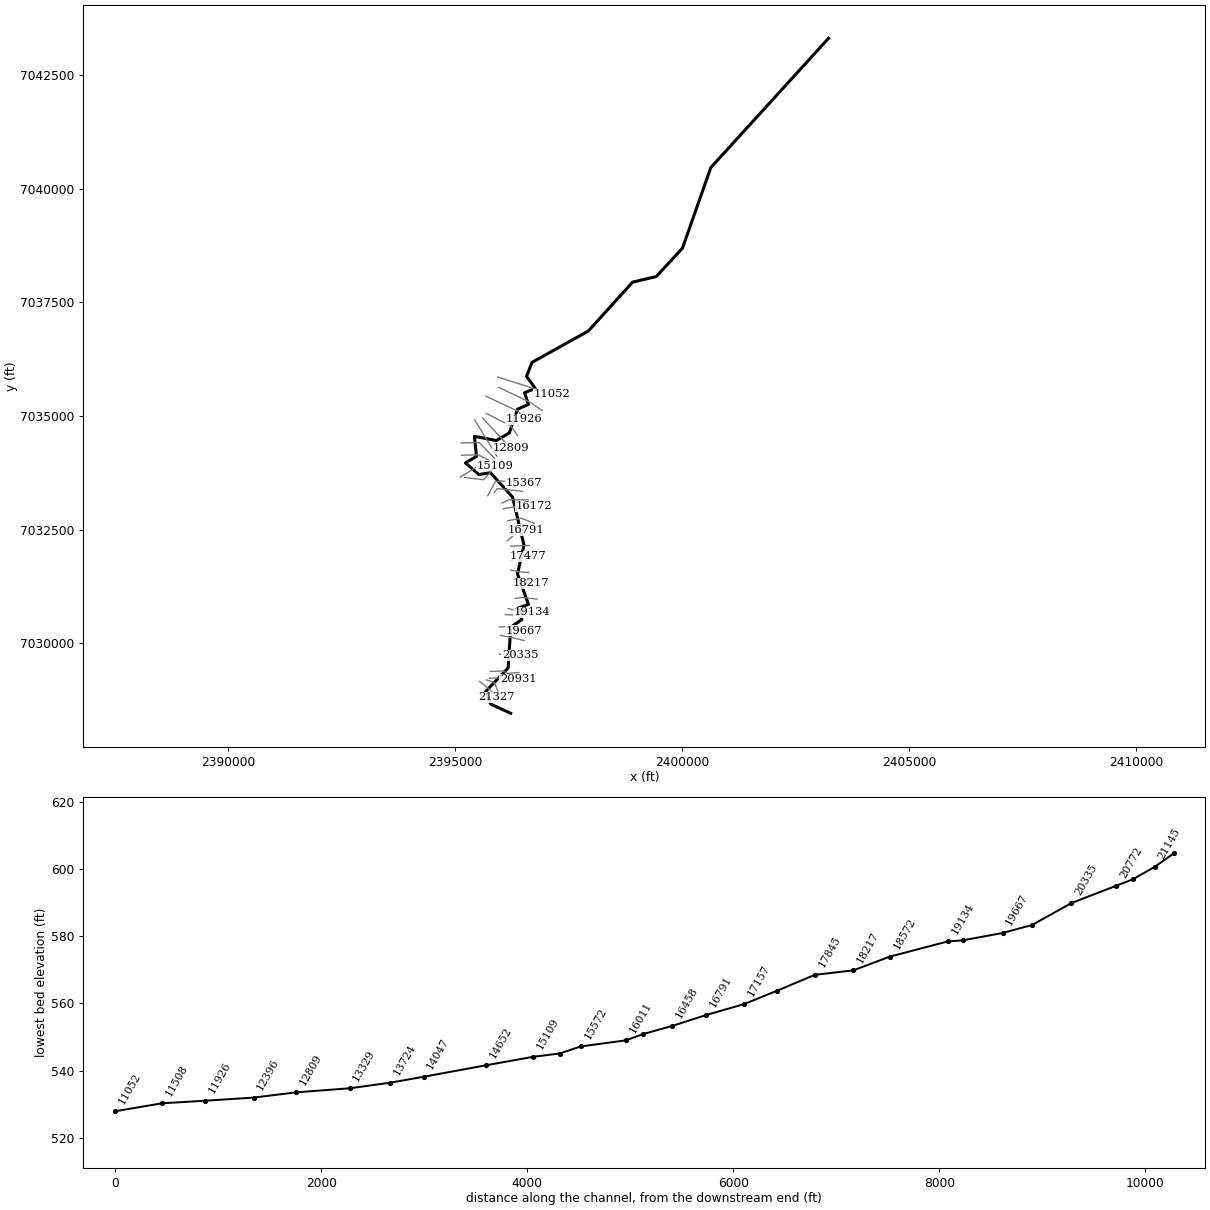
--- Jones Branch.prj (project) ---

Proj Title=Jones Branch Base Level Engineering
Current Plan=p01
Default Exp/Contr=0.3,0.1
English Units
Geom File=g01
Flow File=f01
Plan File=p01
Y Axis Title=Elevation
X Axis Title(PF)=Main Channel Distance
X Axis Title(XS)=Station
BEGIN DESCRIPTION:
Jones Branch
END DESCRIPTION:
DSS Export Rating Curves= 0
DSS Export Rating Curve Sorted= 0
DSS Export Volume Flow Curves= 0
DXF OffsetX= 0
DXF OffsetY= 0
DXF ScaleX= 1
DXF ScaleY= 10

--- Jones Branch.p01 (plan) ---

Plan Title=Multiple Run
Program Version=4.10
Short Identifier=Multiple
Geom File=g01
Flow File=f01
Subcritical Flow
K Sum by GR= 0
Std Step Tol= 0.01
Critical Tol= 0.01
Num of Std Step Trials= 20
Max Error Tol= 0.3
Flow Tol Ratio= 0.001
Split Flow NTrial= 30
Split Flow Tol= 0.02
Split Flow Ratio= 0.02
Log Output Level= 0
Friction Slope Method= 1
Unsteady Friction Slope Method= 2
Unsteady Bridges Friction Slope Method= 1
Parabolic Critical Depth
Global Vel Dist= 1 , 1 , 1
Global Log Level= 0
CheckData=True
Encroach Param=-1 ,0,0, 0
BEGIN DESCRIPTION:
Multiple Run
END DESCRIPTION:
Computation Interval=1HOUR
Output Interval=1HOUR
Run HTab= 0
Run UNet= 0
Run PostProcess= 0
Run WQNet= 0
UNET Theta= 1
UNET Theta Warmup= 1
UNET ZTol= 0.02
UNET ZSATol= 0.05
UNET MxIter= 20
UNET MaxInSteps= 0
UNET DtIC= 0
UNET DtMin= 0
UNET MaxCRTS= 20
UNET WFStab= 2
UNET SFStab= 1
UNET WFX= 1
UNET SFX= 1
UNET DSS MLevel= 4
UNET DZMax Abort= 100
UNET Convert EG Bridges= 0
UNET Use Existing IB Tables=-1
UNET Froude Reduction=False
UNET Froude Limit= 1
UNET Froude Power= 10
UNET Time Slicing=0,0, 5
UNET Junction Losses=0
Instantaneous Interval=1HOUR
Write IC File= 0
Write IC File at Sim End=0
Echo Input=False
Echo Parameters=False
Echo Output=False
Write Detailed= 0
WQ AD Non Conservative
WQ ULTIMATE=-1
WQ Max Comp Step=1HOUR
WQ Output Interval=15MIN
WQ Output Selected Increments= 0
WQ Output face flow=0
WQ Output face velocity=0
WQ Output face area=0
WQ Output face dispersion=0
WQ Output cell volume=0
WQ Output cell surface area=0
WQ Output cell continuity=0
WQ Output cumulative cell continuity=0
WQ Output face conc=0
WQ Output face dconc_dx=0
WQ Output face courant=0
WQ Output face peclet=0
WQ Output face adv mass=0
WQ Output face disp mass=0
WQ Output cell mass=0
WQ Output cell source sink temp=0
WQ Output cell source sink nsm=0
WQ Output MaxMinRange=-1
WQ Daily Max Min Mean=-1
WQ Daily Range=0
WQ Daily Time=0
WQ Create Restart=0
WQ Fixed Restart=0
WQ System Summary=0
WQ Use Fixed Temperature=0
Sorting and Armoring Iterations= 10
XS Update Threshold= 0.02
Hydraulics Update Threshold= 0.02
Energy Slope Method= 1
Volume Change Method= 0
XS Weighting Method= 0
Number of US Weighted Cross Sections= 1
Number of DS Weighted Cross Sections= 1
Upstream XS Weight=0.25
Main XS Weight=0.5
Downstream XS Weight=0.25
Number of DS XS's Weighted with US Boundary= 1
Upstream Boundary Weight= 1
Weight of XSs Associated with US Boundary= 0
Number of US XS's Weighted with DS Boundary= 1
Downstream Boundary Weight= 0.5
Weight of XSs Associated with DS Boundary= 0.5
Sediment Output Level= 4
Mass or Volume Output= 0
Output Increment Type= 1
Profile and TS Output Increment= 10
XS Output Flag= 0
XS Output Increment= 10
Disregard all LS=0
Disregard all Conn=0
Disregard all Breaches=0
Disregard all Pumps=0

--- Jones Branch.f01 (steady flow) ---

Flow Title=Multiple
Number of Profiles=7
Profile Names=10-year,25-year,50-year,1pct_min,100-year,1pct_plu,500-year
River Rch & RM= Jones Branch,Reach-1,21327
     526     714     868     524    1045    2086    1514
River Rch & RM= Jones Branch,Reach-1,20335
     749    1037    1276     779    1554    3100    2303
River Rch & RM= Jones Branch,Reach-1,14652
    1811    2623    3327    2086    4161    8303    6516
River Rch & RM= Jones Branch,Reach-1,9680
    1914    2776    3524    2211    4411    8801    6917
River Rch & RM= Jones Branch,Reach-1,8300
    2038    2961    3764    2362    4713    9404    7401
River Rch & RM= Jones Branch,Reach-1,7003
    2052    2974    3772    2363    4715    9408    7375
River Rch & RM= Jones Branch,Reach-1,4192
    2267    3290    4177    2617    5221   10418    8169
Boundary for River Rch & Prof#=Jones Branch,Reach-1,1
Up Type=0
Dn Type=3
Dn Slope=0.005
Boundary for River Rch & Prof#=Jones Branch,Reach-1,2
Up Type=0
Dn Type=3
Dn Slope=0.005
Boundary for River Rch & Prof#=Jones Branch,Reach-1,3
Up Type=0
Dn Type=3
Dn Slope=0.005
Boundary for River Rch & Prof#=Jones Branch,Reach-1,4
Up Type=0
Dn Type=3
Dn Slope=0.005
Boundary for River Rch & Prof#=Jones Branch,Reach-1,5
Up Type=0
Dn Type=3
Dn Slope=0.005
Boundary for River Rch & Prof#=Jones Branch,Reach-1,6
Up Type=0
Dn Type=3
Dn Slope=0.005
Boundary for River Rch & Prof#=Jones Branch,Reach-1,7
Up Type=0
Dn Type=3
Dn Slope=0.005

--- Jones Branch.g01 (geometry) ---

Geom Title=Existing Conditions
Program Version=4.10

River Reach=Jones Branch    ,Reach-1
Reach XY= 30
        2396229.        7028460.      2395784.08      7028665.04
      2395678.74      7028940.05      2396173.48      7029457.57
      2396230.54      7030354.15      2396477.39      7030521.83
      2396392.27      7030773.83      2396621.41      7030856.64
      2396378.76      7031525.71      2396521.92        7032160.
      2396271.19      7033216.23      2395785.19       7033752.2
       2395530.5      7033713.15      2395231.74      7033968.25
      2395475.49      7034111.25      2395432.21      7034552.75
      2395913.94      7034460.31      2396199.41      7034629.14
      2396382.17      7035152.34      2396621.24      7035256.58
      2396534.28      7035512.71      2396771.35       7035606.3
       2396579.1      7035874.04      2396698.78      7036180.09
      2397938.81      7036870.51      2398915.68      7037946.63
      2399435.07      7038068.13      2400012.54      7038693.25
      2400636.86      7040466.17        2403229.        7043310.

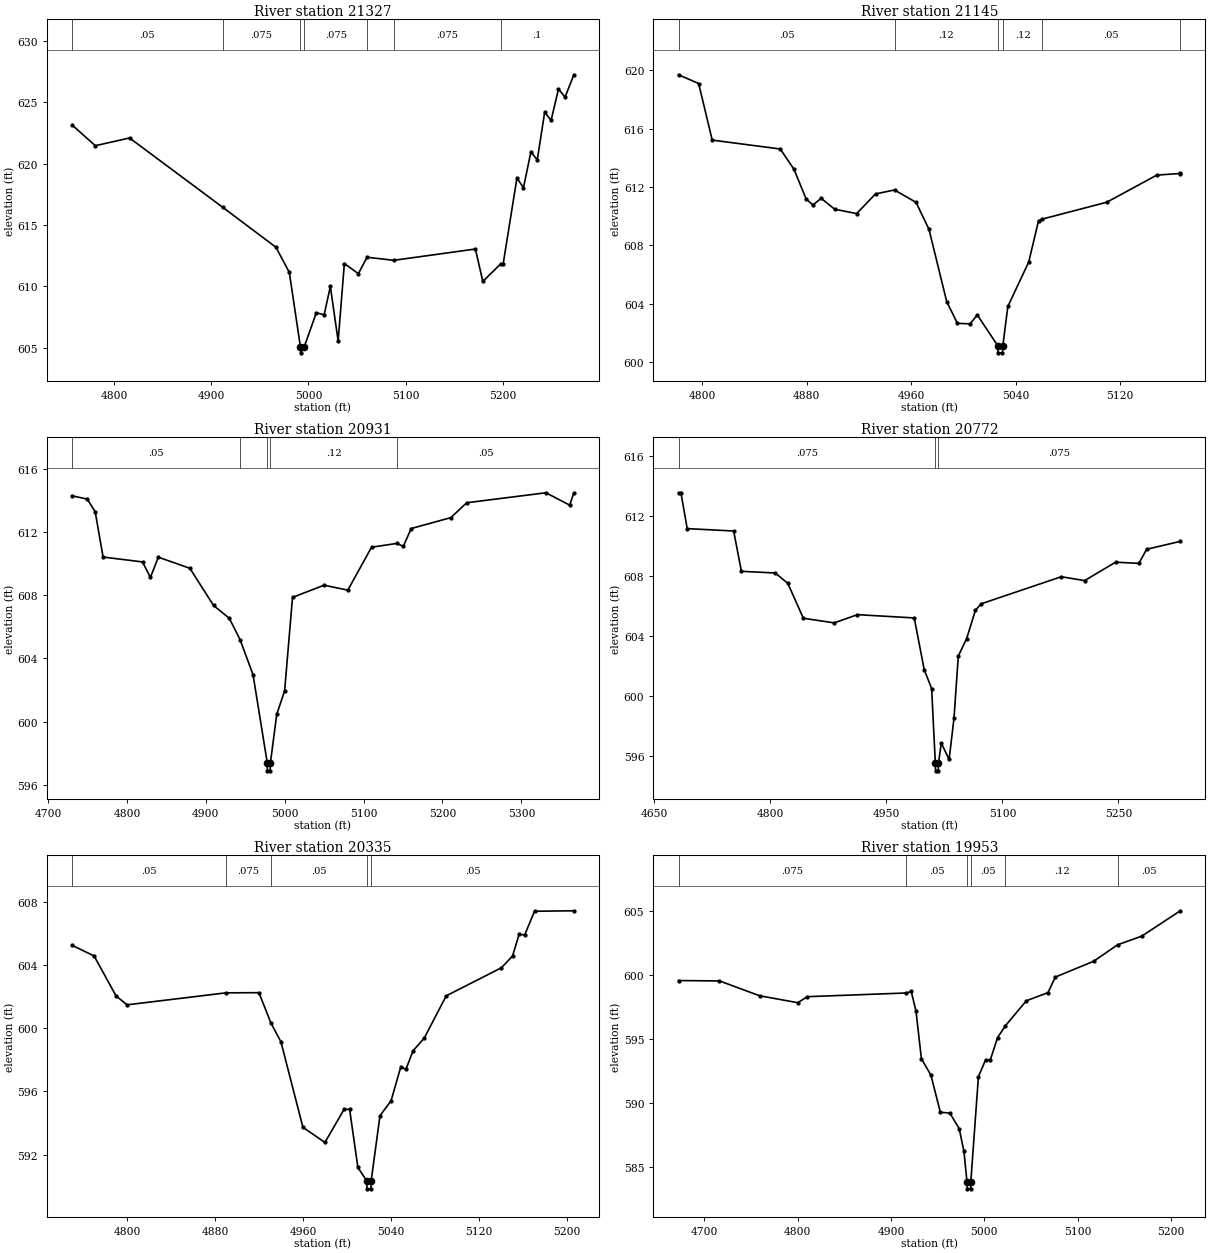
Type RM Length L Ch R = 1 ,21327   ,182,182,182
BEGIN DESCRIPTION:
Jones Branch 50.0
END DESCRIPTION:
XS GIS Cut Line= 3
      2395545.12      7029159.84      2395789.08      7028963.31
      2395922.37      7028810.83
#Sta/Elev= 30
    4757  623.15  4780.9  621.46  4816.1  622.09  4911.7  616.45  4966.5  613.19
  4980.3  611.14  4991.7  605.08    4992  604.58  4995.7  605.08  5008.1  607.85
  5016.1  607.68  5022.5  609.99  5030.5  605.55  5036.9  611.86  5051.3  611.03
  5060.2  612.37  5087.7  612.12  5171.6  613.04  5179.2   610.4  5197.4  611.81
  5200.1  611.81  5214.3  618.83    5221  618.04  5228.6  620.94  5235.2  620.31
  5242.8  624.19  5249.4  623.52    5257  626.09  5263.7  625.41  5272.8  627.24
#Mann= 7 ,-1 , 0
    4757     .05       0  4911.7    .075       0  4991.7     .07       0
  4995.7    .075       0  5060.2     .05       0  5087.7    .075       0
  5197.4      .1       0
Bank Sta=4991.7,4995.7
XS Rating Curve= 0 ,0
Exp/Cntr=0.3,0.1

Type RM Length L Ch R = 1 ,21145   ,214,214,214
BEGIN DESCRIPTION:
Jones Branch 49.0
END DESCRIPTION:
XS GIS Cut Line= 3
      2395694.21       7029193.7      2395863.62      7029144.01
      2395946.54      7028953.52
#Sta/Elev= 30
  4781.8   619.7  4797.2   619.1  4807.6  615.22  4859.7  614.61  4870.2  613.22
  4879.6  611.17  4884.8  610.77    4891  611.23  4901.4  610.48  4918.2  610.18
  4932.7  611.53  4947.2   611.8  4963.7  610.95  4973.6   609.1  4987.2  604.14
  4995.4  602.65  5005.1  602.62  5010.6  603.23  5026.2  601.13  5026.4  600.63
  5029.9  600.63  5030.2  601.13    5034  603.81    5050  606.86  5057.5  609.69
  5060.2   609.8  5109.8  610.96  5148.1  612.82  5165.8  612.93  5166.1  612.92
#Mann= 6 ,-1 , 0
  4781.8     .05       0  4947.2     .12       0  5026.2     .07       0
  5030.2     .12       0  5060.2     .05       0  5165.8    .075       0
Bank Sta=5026.2,5030.2
XS Rating Curve= 0 ,0
Exp/Cntr=0.3,0.1

Type RM Length L Ch R = 1 ,20931   ,159,159,159
BEGIN DESCRIPTION:
Jones Branch 48.5
END DESCRIPTION:
XS GIS Cut Line= 3
       2395759.7       7029232.1      2396084.98      7029238.88
      2396394.24      7029209.53
#Sta/Elev= 30
  4730.5  614.28  4749.8  614.07  4759.8  613.27  4769.8  610.41  4819.8   610.1
  4829.8  609.12  4839.8   610.4  4879.8   609.7  4909.8  607.35  4929.8  606.54
  4943.5  605.18  4959.9  602.97  4977.9   597.4  4978.1   596.9  4981.6   596.9
  4981.9   597.4  4989.9  600.47  4999.9  601.95  5009.9  607.86  5049.9  608.63
    5080  608.32  5110.1  611.03  5142.2  611.27  5150.3  611.08  5160.3  612.21
  5210.6   612.9  5230.7  613.84  5331.1  614.47  5361.2  613.69  5366.5  614.46
#Mann= 5 ,-1 , 0
  4730.5     .05       0  4943.5     .12       0  4977.9     .07       0
  4981.9     .12       0  5142.2     .05       0
Bank Sta=4977.9,4981.9
XS Rating Curve= 0 ,0
Exp/Cntr=0.3,0.1

Type RM Length L Ch R = 1 ,20772   ,437,437,437
BEGIN DESCRIPTION:
Jones Branch 48.0
END DESCRIPTION:
XS GIS Cut Line= 4
      2395777.83      7029378.92      2396053.36      7029392.48
      2396157.26      7029338.26      2396412.47      7029356.33
#Sta/Elev= 30
  4681.2  613.55  4684.3  613.55  4692.4  611.16  4752.5     611  4762.5  608.31
  4806.2   608.2  4822.5  607.51  4842.6  605.18  4882.6  604.87  4912.6  605.42
    4986   605.2  4998.9  601.75  5008.5  600.49  5013.3   595.5  5013.6     595
  5017.1     595  5017.3   595.5    5021  596.85  5031.1  595.76  5037.4   598.5
    5043  602.66  5053.7  603.81  5065.1  605.71  5072.4  606.14  5176.2  607.95
  5206.3  607.69  5246.4  608.92  5276.5  608.84  5286.5  609.78  5330.1  610.31
#Mann= 3 ,-1 , 0
  4681.2    .075       0  5013.3     .07       0  5017.3    .075       0
Bank Sta=5013.3,5017.3
XS Rating Curve= 0 ,0
Exp/Cntr=0.3,0.1

Type RM Length L Ch R = 1 ,20335   ,382,382,382
BEGIN DESCRIPTION:
Jones Branch 47.0
END DESCRIPTION:
XS GIS Cut Line= 3
      2395979.03        7029760.        2396229.        7029760.
       2396434.6      7029740.37
#Sta/Elev= 30
    4750  605.26    4770  604.59    4790  602.06    4800  601.49  4890.1  602.25
    4920  602.26    4931  600.32    4940  599.15    4960  593.73    4980  592.77
  4997.5  594.87  5002.5  594.87    5010  591.19  5018.1  590.33  5018.3  589.83
  5021.8  589.83  5022.1  590.33  5030.1  594.46  5040.2  595.41  5048.9  597.52
  5053.9  597.43  5060.2  598.58  5070.3  599.37  5090.4  602.06  5140.6  603.84
  5150.7  604.58  5156.7  605.96  5161.8  605.92  5170.7  607.42  5206.5  607.45
#Mann= 5 ,-1 , 0
    4750     .05       0  4890.1    .075       0    4931     .05       0
  5018.1    .033       0  5022.1     .05       0
Bank Sta=5018.1,5022.1
XS Rating Curve= 0 ,0
Exp/Cntr=0.3,0.1

Type RM Length L Ch R = 1 ,19953   ,286,286,286
BEGIN DESCRIPTION:
Jones Branch 46.0
END DESCRIPTION:
XS GIS Cut Line= 3
      2396003.63      7030174.02        2396329.        7030110.
      2396529.04      7030059.99
#Sta/Elev= 30
  4672.3  599.57  4716.2  599.54  4759.3  598.38  4800.1  597.84  4810.3  598.31
  4916.6   598.6  4921.7  598.72  4926.8  597.19  4932.6  593.46  4942.8  592.18
  4952.9  589.28  4963.1  589.22  4973.1     588  4978.2  586.22  4981.5   583.8
  4981.8   583.3  4985.3   583.3  4985.5   583.8  4993.7  592.06  5001.4  593.38
  5006.5  593.38  5014.2  595.11  5022.6  596.04  5045.1  597.99  5068.3  598.63
  5076.1  599.84  5117.3  601.08  5142.8  602.36  5168.8  603.04  5210.1  605.02
#Mann= 6 ,-1 , 0
  4672.3    .075       0  4916.6     .05       0  4981.5     .05       0
  4985.5     .05       0  5022.6     .12       0  5142.8     .05       0
Bank Sta=4981.5,4985.5
XS Rating Curve= 0 ,0
Exp/Cntr=0.3,0.1

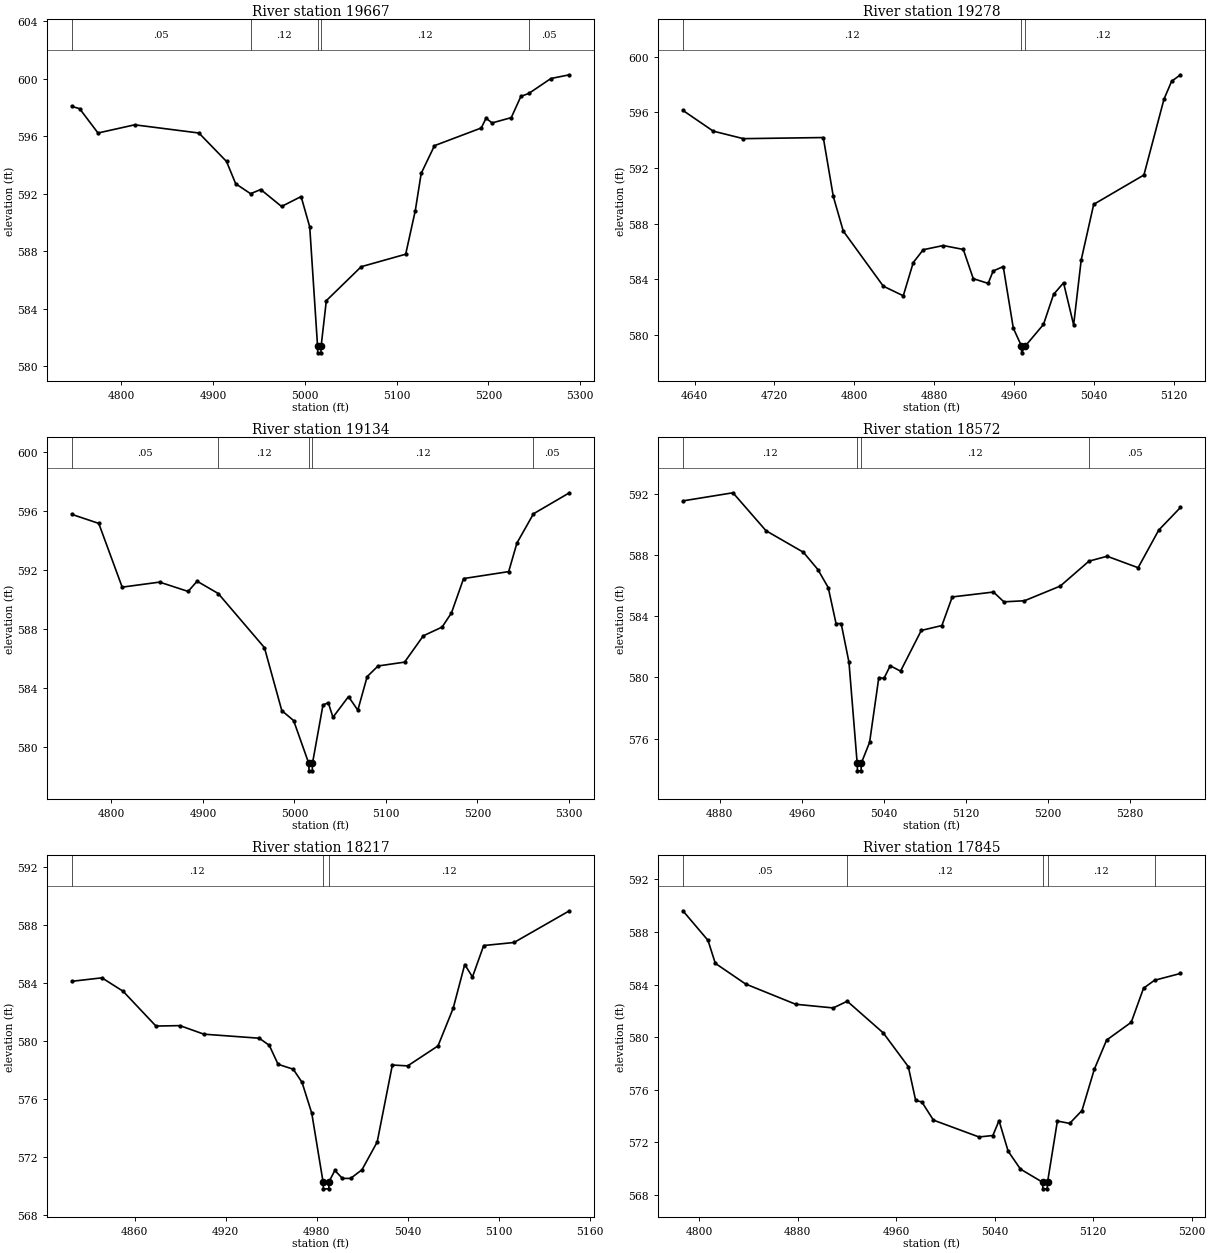
Type RM Length L Ch R = 1 ,19667   ,389,389,389
BEGIN DESCRIPTION:
Jones Branch 45.0
END DESCRIPTION:
XS GIS Cut Line= 3
      2395980.52      7030358.87      2396222.77      7030366.01
      2396509.59      7030277.93
#Sta/Elev= 30
  4745.9  598.07  4754.4  597.91  4774.4  596.22  4814.4  596.79  4884.4  596.22
  4914.5  594.24  4924.5  592.69  4940.7     592  4951.8  592.29  4974.5  591.11
  4995.8   591.8  5005.2  589.69  5013.7  581.43  5013.9  580.93  5017.4  580.93
  5017.7  581.43  5023.3  584.56  5061.3  586.92  5109.8  587.79  5120.3  590.83
  5126.7  593.41  5141.2  595.34  5192.2  596.57  5197.4  597.25    5204  596.92
  5224.9  597.29  5235.4  598.77    5244  598.97  5268.1  600.01  5288.3  600.27
#Mann= 5 ,-1 , 0
  4745.9     .05       0  4940.7     .12       0  5013.7     .07       0
  5017.7     .12       0    5244     .05       0
Bank Sta=5013.7,5017.7
XS Rating Curve= 0 ,0
Exp/Cntr=0.3,0.1

Type RM Length L Ch R = 1 ,19278   ,144,144,144
BEGIN DESCRIPTION:
Jones Branch 44.3
END DESCRIPTION:
XS GIS Cut Line= 3
      2396108.62      7030631.07       2396423.8      7030614.47
      2396605.37       7030594.3
#Sta/Elev= 30
  4628.3  596.14  4658.7  594.65  4688.8  594.11  4768.9  594.19  4778.9  589.96
  4788.9  587.47    4829  583.51    4849  582.82    4859  585.21    4869  586.13
    4889  586.43  4909.1  586.15  4919.1  584.05    4934  583.71    4939   584.6
  4949.1  584.92  4959.2  580.49  4967.3  579.22  4967.5  578.72  4971.3  579.22
  4989.4  580.76  4999.5  582.92  5009.5  583.75  5019.6  580.73  5027.2   585.4
  5039.7  589.39    5090   591.5  5110.1  596.95  5117.7  598.23  5126.6   598.7
#Mann= 3 ,-1 , 0
  4628.3     .12       0  4967.3     .07       0  4971.3     .12       0
Bank Sta=4967.3,4971.3
XS Rating Curve= 0 ,0
Exp/Cntr=0.3,0.1

Type RM Length L Ch R = 1 ,19134   ,562,562,562
BEGIN DESCRIPTION:
Jones Branch 44.0
END DESCRIPTION:
XS GIS Cut Line= 4
      2396175.31       7030761.3      2396380.88      7030716.12
      2396444.13      7030736.45      2396705.12       7030680.2
#Sta/Elev= 30
  4756.7  595.75  4786.1  595.14  4811.7  590.83  4852.6  591.17  4883.8  590.54
  4893.6  591.23  4916.7   590.4  4967.2  586.74  4986.2  582.48  4999.1  581.81
  5015.7  578.91    5016  578.41  5019.5  578.41  5019.7  578.91  5031.2  582.86
    5037  583.02  5042.1  582.03  5059.1  583.43  5069.3  582.51  5079.5  584.78
  5091.4   585.5  5120.4  585.76  5140.9  587.54  5161.4  588.13  5171.6  589.08
  5184.9  591.41  5234.2  591.88  5243.2  593.81  5261.3  595.79  5300.6  597.21
#Mann= 5 ,-1 , 0
  4756.7     .05       0  4916.7     .12       0  5015.7     .07       0
  5019.7     .12       0  5261.3     .05       0
Bank Sta=5015.7,5019.7
XS Rating Curve= 0 ,0
Exp/Cntr=0.3,0.1

Type RM Length L Ch R = 1 ,18572   ,355,355,355
BEGIN DESCRIPTION:
Jones Branch 43.0
END DESCRIPTION:
XS GIS Cut Line= 3
      2396328.92      7030987.17        2396479.        7031010.
      2396810.04      7030971.36
#Sta/Elev= 30
    4844  591.54  4892.8  592.07    4925  589.59  4961.5  588.18  4975.6  587.05
  4985.7  585.87  4993.3  583.52  4998.3  583.52  5005.9  580.99  5013.9  574.39
  5014.2  573.89  5017.7  573.89  5017.9  574.39    5026  575.75    5035  579.99
    5040  579.93  5046.1  580.76  5056.2  580.41  5076.4  583.07  5096.5  583.39
  5106.6  585.26  5146.8  585.58  5156.9  584.94    5177  585.01  5211.9  585.97
  5239.9   587.6  5257.6  587.92  5287.8  587.17  5307.9  589.63  5329.1  591.11
#Mann= 4 ,-1 , 0
    4844     .12       0  5013.9     .07       0  5017.9     .12       0
  5239.9     .05       0
Bank Sta=5013.9,5017.9
XS Rating Curve= 0 ,0
Exp/Cntr=0.3,0.1

Type RM Length L Ch R = 1 ,18217   ,372,372,372
BEGIN DESCRIPTION:
Jones Branch 42.0
END DESCRIPTION:
XS GIS Cut Line= 3
      2396371.85      7031219.82        2396529.        7031310.
      2396675.43      7031319.13
#Sta/Elev= 30
  4818.7  584.13  4838.5  584.37  4852.5  583.44  4874.1  581.04  4889.9  581.07
  4905.7  580.48  4942.2   580.2  4948.8  579.71  4954.6   578.4  4964.6  578.06
  4970.4  577.15  4976.8  575.02  4984.2   570.3  4984.5   569.8    4988   569.8
  4988.2   570.3    4992  571.07    4997  570.52  5002.4  570.52  5009.9  571.12
  5019.9  573.03  5029.9  578.35    5040  578.29    5060  579.67    5070  582.27
  5077.6  585.29  5082.7  584.43  5090.1   586.6  5110.1  586.81  5146.6     589
#Mann= 3 ,-1 , 0
  4818.7     .12       0  4984.2     .07       0  4988.2     .12       0
Bank Sta=4984.2,4988.2
XS Rating Curve= 0 ,0
Exp/Cntr=0.3,0.1

Type RM Length L Ch R = 1 ,17845   ,368,368,368
BEGIN DESCRIPTION:
Jones Branch 41.0
END DESCRIPTION:
XS GIS Cut Line= 3
      2396228.99        7031610.      2396466.72      7031565.42
      2396628.96        7031560.
#Sta/Elev= 30
  4786.7   589.6  4807.1  587.35    4813  585.61  4837.6  584.04  4878.3   582.5
  4908.8  582.22  4920.2  582.73  4949.5  580.32  4969.8  577.76  4975.8  575.19
  4980.8  575.08  4990.2   573.7  5027.2  572.42  5038.5  572.53  5043.5  573.66
  5050.9  571.34  5060.9  569.98  5078.9  568.98  5079.1  568.48  5082.6  568.48
  5082.9  568.98  5090.9  573.63  5100.9  573.45  5110.9  574.43  5120.9  577.56
  5130.9  579.78  5150.9  581.13  5160.9  583.72  5169.8  584.32  5190.9  584.84
#Mann= 5 ,-1 , 0
  4786.7     .05       0  4920.2     .12       0  5078.9     .07       0
  5082.9     .12       0  5169.8    .075       0
Bank Sta=5078.9,5082.9
XS Rating Curve= 0 ,0
Exp/Cntr=0.3,0.1

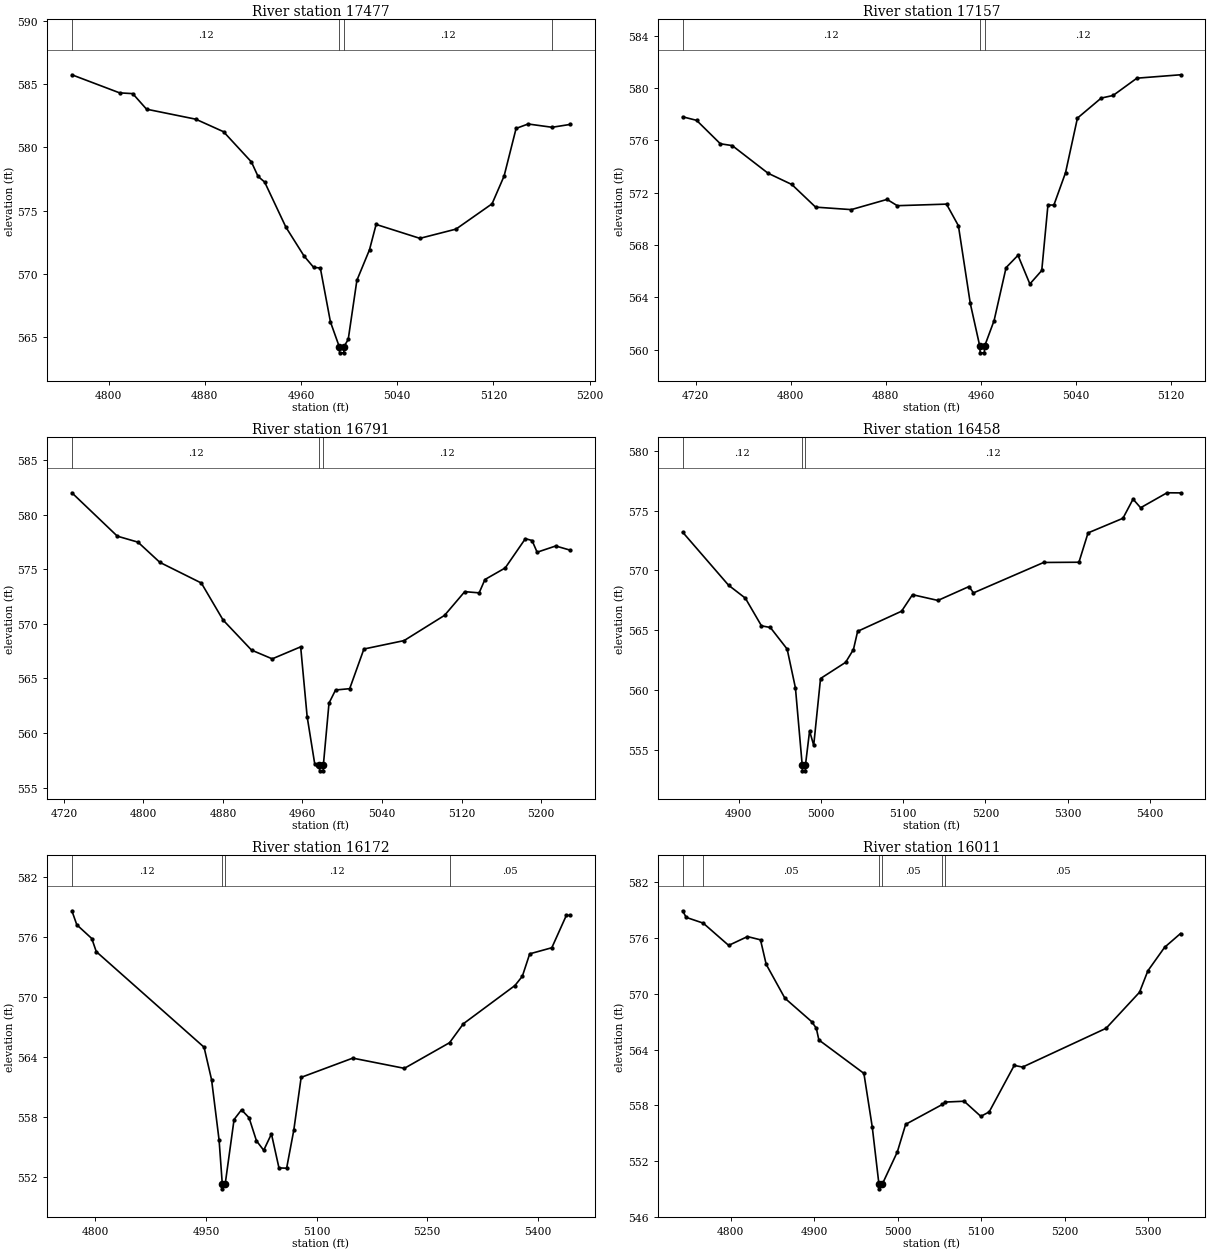
Type RM Length L Ch R = 1 ,17477   ,320,320,320
BEGIN DESCRIPTION:
Jones Branch 40.0
END DESCRIPTION:
XS GIS Cut Line= 3
      2396222.79      7031811.63      2396464.46      7031920.05
      2396613.57      7031917.79
#Sta/Elev= 30
  4769.5  585.73  4809.2   584.3  4820.1  584.24  4831.6  583.01  4872.5  582.22
  4895.6  581.23  4918.8  578.84  4924.3   577.7  4929.8  577.25  4947.5  573.68
  4962.6   571.4  4970.6   570.5  4976.1  570.46  4984.5   566.2  4991.8  564.25
  4992.1  563.75  4995.6  563.75  4995.8  564.25  4999.3  564.81  5006.5  569.48
    5017   571.9  5022.5   573.9  5058.9   572.8  5088.9  573.53  5118.9  575.53
  5128.9  577.72  5138.9  581.49  5148.9  581.84  5168.8  581.58  5183.5   581.8
#Mann= 4 ,-1 , 0
  4769.5     .12       0  4991.8     .07       0  4995.8     .12       0
  5168.8     .05       0
Bank Sta=4991.8,4995.8
XS Rating Curve= 0 ,0
Exp/Cntr=0.3,0.1

Type RM Length L Ch R = 1 ,17157   ,366,366,366
BEGIN DESCRIPTION:
Jones Branch 39.0
END DESCRIPTION:
XS GIS Cut Line= 3
      2396227.31      7032136.89      2396534.48      7032150.44
      2396645.71      7032150.44
#Sta/Elev= 30
  4709.2  577.79  4720.9  577.52  4740.9  575.73  4750.9  575.59    4781  573.48
    4801  572.62    4821  570.89    4851   570.7  4881.1  571.48  4889.7     571
  4931.1  571.12  4941.1  569.47  4951.1  563.53  4959.1  560.26  4959.4  559.76
  4962.9  559.76  4963.1  560.26  4971.1  562.22  4981.2  566.27  4991.2  567.21
  5001.2  565.02  5011.2  566.05  5016.4  571.05  5021.4  571.05  5031.2  573.52
  5041.2  577.69  5061.2  579.22  5071.2  579.42  5091.2  580.74  5127.9     581
#Mann= 3 ,-1 , 0
  4709.2     .12       0  4959.1     .07       0  4963.1     .12       0
Bank Sta=4959.1,4963.1
XS Rating Curve= 0 ,0
Exp/Cntr=0.3,0.1

Type RM Length L Ch R = 1 ,16791   ,333,333,333
BEGIN DESCRIPTION:
Jones Branch 38.0
END DESCRIPTION:
XS GIS Cut Line= 3
      2396150.46      7032254.32      2396387.66      7032457.63
      2396572.87      7032491.51
#Sta/Elev= 30
  4728.1  581.99  4773.8  578.02  4794.6  577.47  4816.6  575.62  4858.3  573.73
  4880.2  570.34  4908.8  567.59  4929.6  566.79  4958.2  567.89  4964.7  561.51
  4972.4  557.14    4977  557.04  4977.3  556.54  4980.8  556.54    4981  557.04
  4986.7  562.74  4993.3  563.94  5007.5  564.06  5021.8  567.69  5062.2  568.46
  5102.9  570.77  5123.2  572.94  5137.7  572.83  5143.5  574.05  5163.9  575.11
  5184.2  577.79  5190.9  577.62    5196  576.55  5214.7  577.12  5228.8  576.75
#Mann= 3 ,-1 , 0
  4728.1     .12       0    4977     .07       0    4981     .12       0
Bank Sta=4977,4981
XS Rating Curve= 0 ,0
Exp/Cntr=0.3,0.1

Type RM Length L Ch R = 1 ,16458   ,286,286,286
BEGIN DESCRIPTION:
Jones Branch 37.0
END DESCRIPTION:
XS GIS Cut Line= 3
      2396164.07      7032697.07       2396462.2      7032751.27
       2396744.3      7032642.95
#Sta/Elev= 30
  4831.9  573.19  4887.7  568.76  4908.1  567.68  4927.7  565.37  4938.5  565.23
  4958.9  563.43    4969  560.18  4977.2  553.76  4977.5  553.26    4981  553.26
  4981.2  553.76  4986.2  556.59  4991.2  555.39  4999.5  560.97    5030  562.32
  5039.5  563.39  5044.6  564.91    5098  566.59  5111.3  567.97  5142.2  567.49
    5180  568.65  5185.4  568.12  5270.7  570.66  5313.6  570.68  5324.7  573.13
  5367.1  574.35  5379.4  575.95  5388.6  575.23  5420.7  576.48  5437.1  576.47
#Mann= 3 ,-1 , 0
  4831.9     .12       0  4977.2     .07       0  4981.2     .12       0
Bank Sta=4977.2,4981.2
XS Rating Curve= 0 ,0
Exp/Cntr=0.3,0.1

Type RM Length L Ch R = 1 ,16172   ,161,161,161
BEGIN DESCRIPTION:
Jones Branch 36.0
END DESCRIPTION:
XS GIS Cut Line= 3
      2396062.37      7032959.08      2396344.74      7033008.77
      2396733.27      7033015.55
#Sta/Elev= 30
  4768.1  578.58  4774.8  577.18  4795.1  575.81  4801.2   574.5  4947.4  564.96
  4957.6  561.71  4967.8  555.68  4972.1  551.32  4972.3  550.82  4976.1  551.32
  4988.1  557.74  4998.2  558.71  5008.4  557.92  5018.5  555.61  5028.3  554.67
  5038.8   556.3    5049  552.91  5059.4  552.88  5069.1  556.67  5079.1  561.95
  5149.1  563.87  5219.1  562.85  5280.4  565.41  5299.1   567.3  5369.1  571.12
  5379.1  572.04  5389.1  574.28  5419.1  574.89  5438.8  578.12  5443.4  578.12
#Mann= 4 ,-1 , 0
  4768.1     .12       0  4972.1     .07       0  4976.1     .12       0
  5280.4     .05       0
Bank Sta=4972.1,4976.1
XS Rating Curve= 0 ,0
Exp/Cntr=0.3,0.1

Type RM Length L Ch R = 1 ,16011   ,439,439,439
BEGIN DESCRIPTION:
Jones Branch 35.5
END DESCRIPTION:
XS GIS Cut Line= 3
      2396039.84      7033083.33      2396186.63      7033157.85
       2396618.1       7033155.6
#Sta/Elev= 30
  4742.6  578.95  4746.8  578.24  4767.2  577.62  4797.7  575.22  4820.2  576.17
  4835.8  575.82  4842.6  573.18    4865  569.53    4897  567.01  4902.6   566.3
  4905.7  565.03  4959.6  561.43  4969.6  555.66  4977.6  549.49  4977.8  548.99
  4981.6  549.49  4999.6  552.96  5009.6  555.94  5053.7  558.09  5057.2  558.34
  5079.6  558.43  5099.6   556.8  5109.6  557.28  5139.6  562.29  5149.6  562.11
  5249.6  566.29  5289.6  570.17  5299.6  572.48  5319.6  575.01  5338.7   576.5
#Mann= 6 ,-1 , 0
  4742.6     .12       0  4767.2     .05       0  4977.6    .033       0
  4981.6     .05       0  5053.7     .12       0  5057.2     .05       0
Bank Sta=4977.6,4981.6
XS Rating Curve= 0 ,0
Exp/Cntr=0.3,0.1

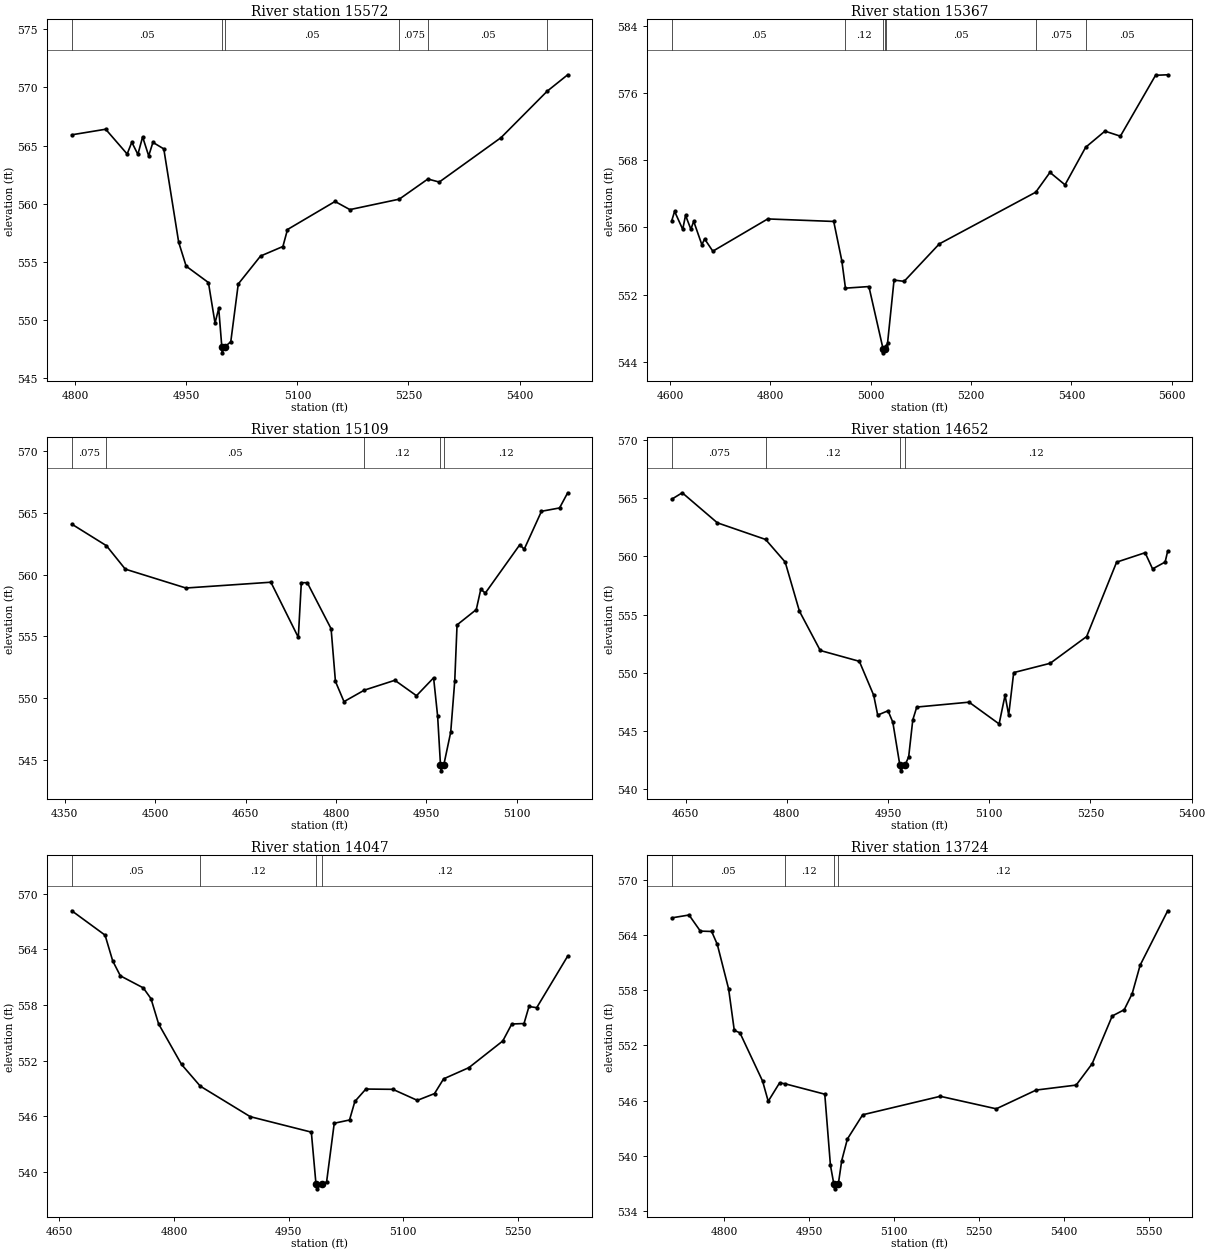
Type RM Length L Ch R = 1 ,15572   ,205,205,205
BEGIN DESCRIPTION:
Jones Branch 35.0
END DESCRIPTION:
XS GIS Cut Line= 3
      2395868.14      7033315.97       2395935.9      7033404.06
      2396491.58      7033345.33
#Sta/Elev= 30
  4795.2  565.92    4841   566.4    4870  564.27  4876.3  565.28  4884.5  564.24
  4890.9  565.74  4899.1  564.11  4904.8  565.27  4919.5  564.71  4939.6  556.69
  4949.7  554.63  4979.8  553.22  4988.7  549.74  4993.7     551  4997.9  547.68
  4998.2  547.18  5001.9  547.68    5010  548.14  5020.1   553.1  5050.2   555.5
  5080.4  556.32  5086.6  557.78  5150.8  560.19  5170.9  559.49  5237.6  560.39
  5276.2  562.12  5291.6  561.86  5375.1  565.68  5437.4  569.67  5465.1  571.08
#Mann= 6 ,-1 , 0
  4795.2     .05       0  4997.9     .05       0  5001.9     .05       0
  5237.6    .075       0  5276.2     .05       0  5437.4    .075       0
Bank Sta=4997.9,5001.9
XS Rating Curve= 0 ,0
Exp/Cntr=0.3,0.1

Type RM Length L Ch R = 1 ,15367   ,258,258,258
BEGIN DESCRIPTION:
Jones Branch 34.0
END DESCRIPTION:
XS GIS Cut Line= 4
       2395723.6      7033245.98      2395892.99      7033559.92
      2396026.26      7033568.95      2396523.15      7033537.33
#Sta/Elev= 30
  4603.5  560.81  4609.1  561.91  4625.3  559.77  4630.9  561.44  4641.5  559.79
  4647.2  560.72  4663.4  557.95    4669  558.62  4685.3  557.17  4794.7  561.01
  4926.2  560.71  4942.3  556.04  4949.6  552.77  4996.3  552.96  5024.4  545.57
  5024.6  545.07  5028.4  545.57  5030.7  545.86  5033.4  546.19  5046.4  553.73
  5066.5  553.58  5136.6  558.04  5328.7  564.19  5357.1  566.55  5387.1  565.07
  5428.2  569.54  5466.6  571.46  5497.4  570.86  5567.5  578.11  5591.7  578.17
#Mann= 7 ,-1 , 0
  4603.5     .05       0  4949.6     .12       0  5024.4     .07       0
  5028.4     .12       0  5030.7     .05       0  5328.7    .075       0
  5428.2     .05       0
Bank Sta=5024.4,5028.4
XS Rating Curve= 0 ,0
Exp/Cntr=0.3,0.1

Type RM Length L Ch R = 1 ,15109   ,457,457,457
BEGIN DESCRIPTION:
Jones Branch 33.0
END DESCRIPTION:
XS GIS Cut Line= 4
       2395210.8      7033648.01      2395634.47      7033599.23
        2395779.        7033760.      2395878.98      7033909.98
#Sta/Elev= 30
  4361.5  564.09    4419  562.34  4450.3  560.44  4550.9  558.91  4691.9  559.38
  4737.4  554.91  4742.4  559.34  4752.3  559.34  4791.8  555.61    4799  551.34
  4813.2   549.7  4846.9  550.63  4897.6  551.43  4933.5  550.18  4961.9  551.63
  4968.6  548.51  4973.3  544.59  4974.2  544.09  4978.9  544.59  4990.3  547.23
    4997  551.39  5000.8  555.92  5032.7  557.16  5040.2  558.81  5047.7   558.5
  5104.8  562.41  5112.3  562.06  5140.9  565.13  5170.9   565.4  5184.4  566.63
#Mann= 5 ,-1 , 0
  4361.5    .075       0    4419     .05       0  4846.9     .12       0
  4973.3     .07       0  4978.9     .12       0
Bank Sta=4973.3,4978.9
XS Rating Curve= 0 ,0
Exp/Cntr=0.3,0.1

Type RM Length L Ch R = 1 ,14652   ,605,605,605
BEGIN DESCRIPTION:
Jones Branch 32.0
END DESCRIPTION:
XS GIS Cut Line= 3
       2395120.5      7033657.05      2395463.82      7033869.37
      2395770.01      7033995.45
#Sta/Elev= 30
  4629.6  564.91  4645.1  565.46  4697.1  562.88  4768.6  561.45  4797.6  559.51
  4818.8  555.28  4849.6  551.91  4907.5  550.98  4928.8  548.06  4934.7  546.36
    4950  546.73  4957.1  545.75  4967.5  542.07  4968.7  541.57  4975.2  542.07
  4980.6  542.77  4986.7  545.95  4992.6  547.05  5070.1  547.47  5114.6   545.6
  5123.4  548.06  5128.8  546.37  5136.2  550.01  5190.3  550.81  5244.3  553.11
  5288.7   559.5  5330.9  560.31    5342  558.92  5360.6  559.51  5364.4  560.46
#Mann= 4 ,-1 , 0
  4629.6    .075       0  4768.6     .12       0  4967.5     .07       0
  4975.2     .12       0
Bank Sta=4967.5,4975.2
XS Rating Curve= 0 ,0
Exp/Cntr=0.3,0.1

Type RM Length L Ch R = 1 ,14047   ,323,323,323
BEGIN DESCRIPTION:
Jones Branch 31.0
END DESCRIPTION:
XS GIS Cut Line= 3
      2395145.37      7034138.16      2395518.03      7034144.94
      2395764.13      7034018.51
#Sta/Elev= 30
  4666.1  568.17  4709.7  565.54  4719.7  562.76  4729.7  561.15  4759.7  559.85
  4769.8  558.69  4779.8  555.96  4809.8  551.59  4834.4  549.24  4899.8  545.95
  4979.8  544.28  4985.9  538.66    4987  538.16  4993.7  538.66  4999.8  538.91
  5009.8  545.24  5029.8  545.59  5036.8  547.59  5051.2  548.93  5086.5   548.9
  5118.6  547.71  5141.1  548.44    5153  550.03  5186.1  551.24  5230.5  554.12
  5242.3  555.95  5258.3     556  5264.8  557.84  5274.9  557.71  5315.5  563.28
#Mann= 4 ,-1 , 0
  4666.1     .05       0  4834.4     .12       0  4985.9     .07       0
  4993.7     .12       0
Bank Sta=4985.9,4993.7
XS Rating Curve= 0 ,0
Exp/Cntr=0.3,0.1

Type RM Length L Ch R = 1 ,13724   ,395,395,395
BEGIN DESCRIPTION:
Jones Branch 30.0
END DESCRIPTION:
XS GIS Cut Line= 3
      2395138.54      7034409.22       2395536.1      7034415.99
      2395871.54       7034073.8
#Sta/Elev= 30
  4706.9  565.86  4737.4  566.17  4757.4  564.42  4777.4  564.38  4787.4  562.97
  4807.4  558.13  4817.4  553.63  4827.4  553.36  4867.4  548.12  4877.4  545.92
  4897.4  547.91  4906.6  547.83  4977.4  546.69  4987.4  538.96  4993.5   536.9
  4994.7   536.4  5001.3   536.9  5007.4  539.48  5017.4  541.82  5044.4  544.45
  5181.6  546.46  5280.6   545.1  5351.2  547.14  5421.9  547.68  5450.2  550.01
  5485.6  555.19  5506.8  555.87  5520.9  557.62    5535  560.72  5583.7  566.63
#Mann= 4 ,-1 , 0
  4706.9     .05       0  4906.6     .12       0  4993.5     .07       0
  5001.3     .12       0
Bank Sta=4993.5,5001.3
XS Rating Curve= 0 ,0
Exp/Cntr=0.3,0.1

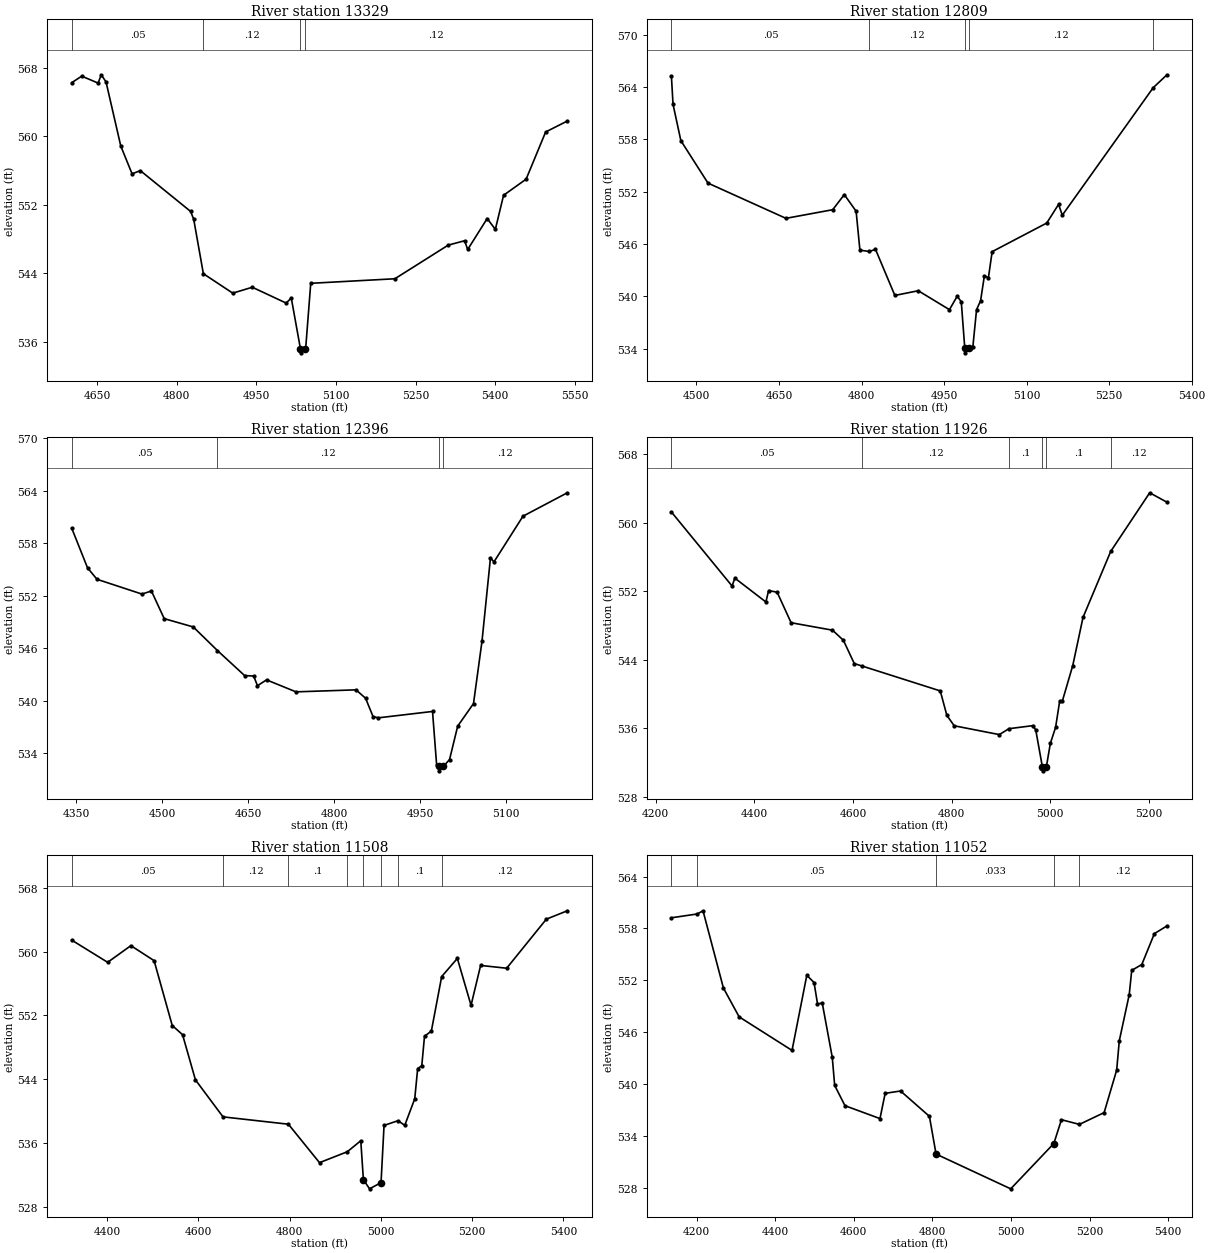
Type RM Length L Ch R = 1 ,13329   ,520,520,520
BEGIN DESCRIPTION:
Jones Branch 29.0
END DESCRIPTION:
XS GIS Cut Line= 3
      2395436.72      7034915.17      2395626.45      7034603.47
      2395924.32      7034118.32
#Sta/Elev= 30
    4602  566.28  4620.8  567.04  4651.7  566.23  4657.6   567.2  4666.6  566.37
  4694.4  558.88  4715.7  555.63  4731.2  556.01  4826.1  551.24  4831.9  550.32
  4850.1  543.97  4905.5   541.7  4942.3  542.39  5006.2  540.54  5015.8  541.14
    5033  535.23  5034.2  534.73  5041.1  535.23    5043  535.28  5052.5  542.85
  5211.1  543.38  5311.7  547.31  5342.5  547.82  5348.4   546.8  5385.1  550.41
  5400.5  549.15    5416  553.13  5458.5  555.01  5495.3  560.52  5536.2   561.8
#Mann= 4 ,-1 , 0
    4602     .05       0  4850.1     .12       0    5033     .07       0
  5041.1     .12       0
Bank Sta=5033,5041.1
XS Rating Curve= 0 ,0
Exp/Cntr=0.3,0.1

Type RM Length L Ch R = 1 ,12809   ,413,413,413
BEGIN DESCRIPTION:
Jones Branch 28.0
END DESCRIPTION:
XS GIS Cut Line= 3
      2395610.67      7034955.81        2395979.        7034560.
      2396224.52      7034296.82
#Sta/Elev= 30
  4454.4  565.28  4457.4  562.01  4471.6  557.85  4520.9  552.98  4662.6  548.94
  4747.6  549.93  4768.6  551.66  4790.1  549.76    4797  545.29  4814.3  545.14
  4825.3  545.39  4860.5   540.1    4903  540.64  4959.7  538.47  4973.8  540.01
  4981.2  539.38  4987.6  534.02  4988.8  533.52  4995.8  534.02  5002.2  534.18
    5009  538.48  5016.3  539.49  5023.2  542.36  5030.5  542.12  5037.3  545.12
  5136.5   548.4    5158  550.54  5164.8   549.3    5330  563.92    5355   565.4
#Mann= 5 ,-1 , 0
  4454.4     .05       0  4814.3     .12       0  4987.6     .07       0
  4995.8     .12       0    5330     .05       0
Bank Sta=4987.6,4995.8
XS Rating Curve= 0 ,0
Exp/Cntr=0.3,0.1

Type RM Length L Ch R = 1 ,12396   ,470,470,470
BEGIN DESCRIPTION:
Jones Branch 27.0
END DESCRIPTION:
XS GIS Cut Line= 3
       2395689.7      7035057.48       2396231.8      7034784.17
      2396379.77      7034573.44
#Sta/Elev= 30
  4341.9  559.69  4369.4  555.17  4385.9  553.86  4464.3  552.17  4480.9  552.52
  4503.2  549.36  4553.9  548.41  4596.1  545.71  4643.5  542.85  4659.3   542.8
  4665.9  541.69  4681.7  542.36  4733.1  540.99  4837.8  541.22  4854.5  540.26
  4867.5  538.17  4876.8  538.02  4971.3  538.75  4978.5  532.61    4982  532.46
  4983.2  531.96  4990.2  532.46    5001  533.25  5015.2  537.07  5042.8  539.65
  5057.6  546.77  5072.4  556.31  5078.5  555.85  5129.1  561.07  5206.5  563.75
#Mann= 4 ,-1 , 0
  4341.9     .05       0  4596.1     .12       0    4982     .07       0
  4990.2     .12       0
Bank Sta=4982,4990.2
XS Rating Curve= 0 ,0
Exp/Cntr=0.3,0.1

Type RM Length L Ch R = 1 ,11926   ,418,418,418
BEGIN DESCRIPTION:
Jones Branch 26.0
END DESCRIPTION:
XS GIS Cut Line= 3
      2395683.19      7035437.47      2396396.08      7035103.69
      2396527.92      7034930.65
#Sta/Elev= 30
  4231.9  561.25    4355   552.6  4360.5  553.53  4423.5  550.74    4429  552.08
  4446.3  551.88  4474.6  548.32  4558.5  547.45  4580.6  546.27  4602.7  543.55
  4618.3  543.27    4777  540.36  4790.4   537.5  4805.3  536.29  4896.7  535.26
  4916.2  535.95  4965.2  536.31  4970.7  535.77  4983.9  531.53  4985.1  531.03
  4992.2  531.53  5000.2  534.24  5010.8   536.1  5019.1  539.17  5024.5  539.17
  5045.6  543.32  5066.4  548.94  5122.6  556.65  5201.6  563.49  5236.6  562.39
#Mann= 6 ,-1 , 0
  4231.9     .05       0  4618.3     .12       0  4916.2      .1       0
  4983.9     .07       0  4992.2      .1       0  5122.6     .12       0
Bank Sta=4983.9,4992.2
XS Rating Curve= 0 ,0
Exp/Cntr=0.3,0.1

Type RM Length L Ch R = 1 ,11508   ,456,456,456
BEGIN DESCRIPTION:
Jones Branch 25.0
END DESCRIPTION:
XS GIS Cut Line= 3
      2395967.52      7035631.15      2396647.45      7035305.61
      2396923.51      7035120.19
#Sta/Elev= 30
  4322.3  561.44    4401  558.66  4451.9  560.75  4502.8  558.87  4542.6  550.74
  4565.2  549.59  4593.4  543.93  4653.9  539.29  4797.2  538.37  4865.4  533.55
  4926.4  534.92  4955.9   536.3  4961.6  531.43  4975.1  530.27  5000.3  531.05
  5006.9  538.22  5037.6  538.81  5052.3  538.23  5074.2  541.56  5080.6  545.34
  5089.6   545.7  5095.6  549.39  5110.6  550.04  5133.2  556.87  5167.6  559.15
  5197.6  553.27  5218.6  558.27  5275.7  557.92  5362.7  564.07  5408.7  565.12
#Mann= 8 ,-1 , 0
  4322.3     .05       0  4653.9     .12       0  4797.2      .1       0
  4926.4     .05       0  4961.6    .033       0  5000.3     .05       0
  5037.6      .1       0  5133.2     .12       0
Bank Sta=4961.6,5000.3
XS Rating Curve= 0 ,0
Exp/Cntr=0.3,0.1

Type RM Length L Ch R = 1 ,11052   ,454,454,454
BEGIN DESCRIPTION:
Jones Branch 24.0
END DESCRIPTION:
XS GIS Cut Line= 3
      2395942.75      7035857.81      2396701.02      7035618.79
      2397144.37      7035475.11
#Sta/Elev= 30
    4136  559.23  4201.7  559.67  4216.5  560.04  4268.4  551.11  4308.4  547.78
    4443   543.9  4480.6  552.58    4499  551.75  4507.8   549.3    4520  549.35
  4545.4   543.1  4551.5  539.86  4577.7  537.51  4666.8  536.02    4680  538.94
  4719.2  539.21  4792.6  536.28  4809.5  531.92  4999.5   527.9  5109.2  533.14
  5128.6  535.89  5174.3  535.35  5237.2  536.71  5269.1  541.62  5275.8  545.02
  5301.1  550.35  5307.4  553.15  5333.1  553.83  5365.1   557.4  5397.1  558.29
#Mann= 5 ,-1 , 0
    4136     .12       0  4201.7     .05       0  4809.5    .033       0
  5109.2     .05       0  5174.3     .12       0
Bank Sta=4809.5,5109.2
XS Rating Curve= 0 ,0
Exp/Cntr=0.3,0.1