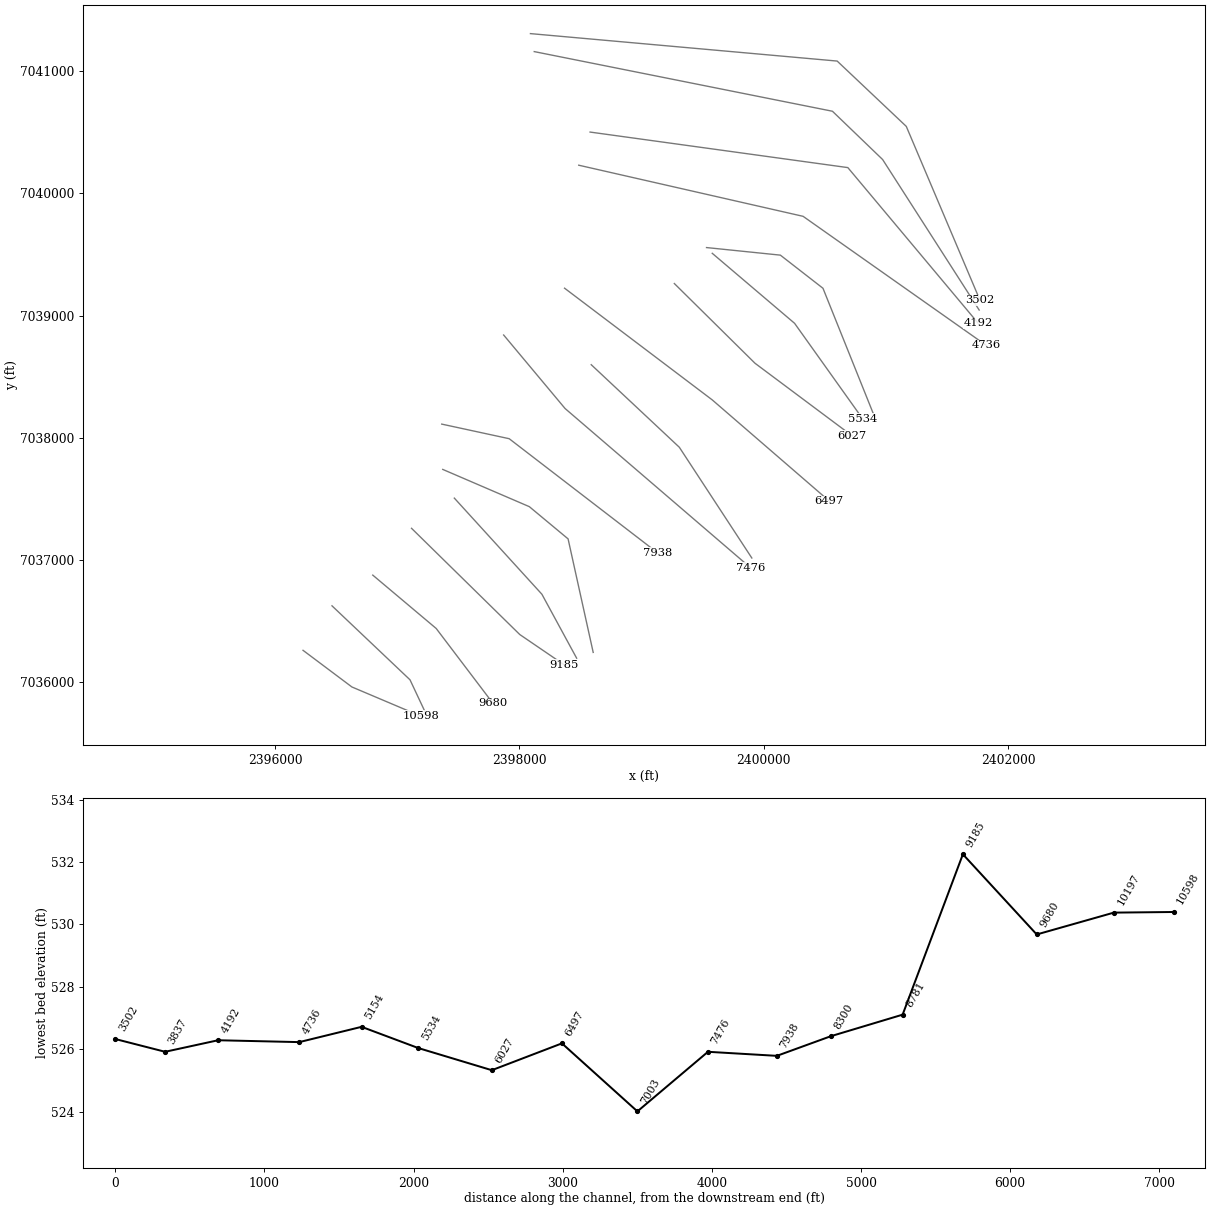
HEC-RAS study Jones Branch.prj: Jones Branch Base Level Engineering

--- Jones Branch.g01 (geometry) --- (continued)

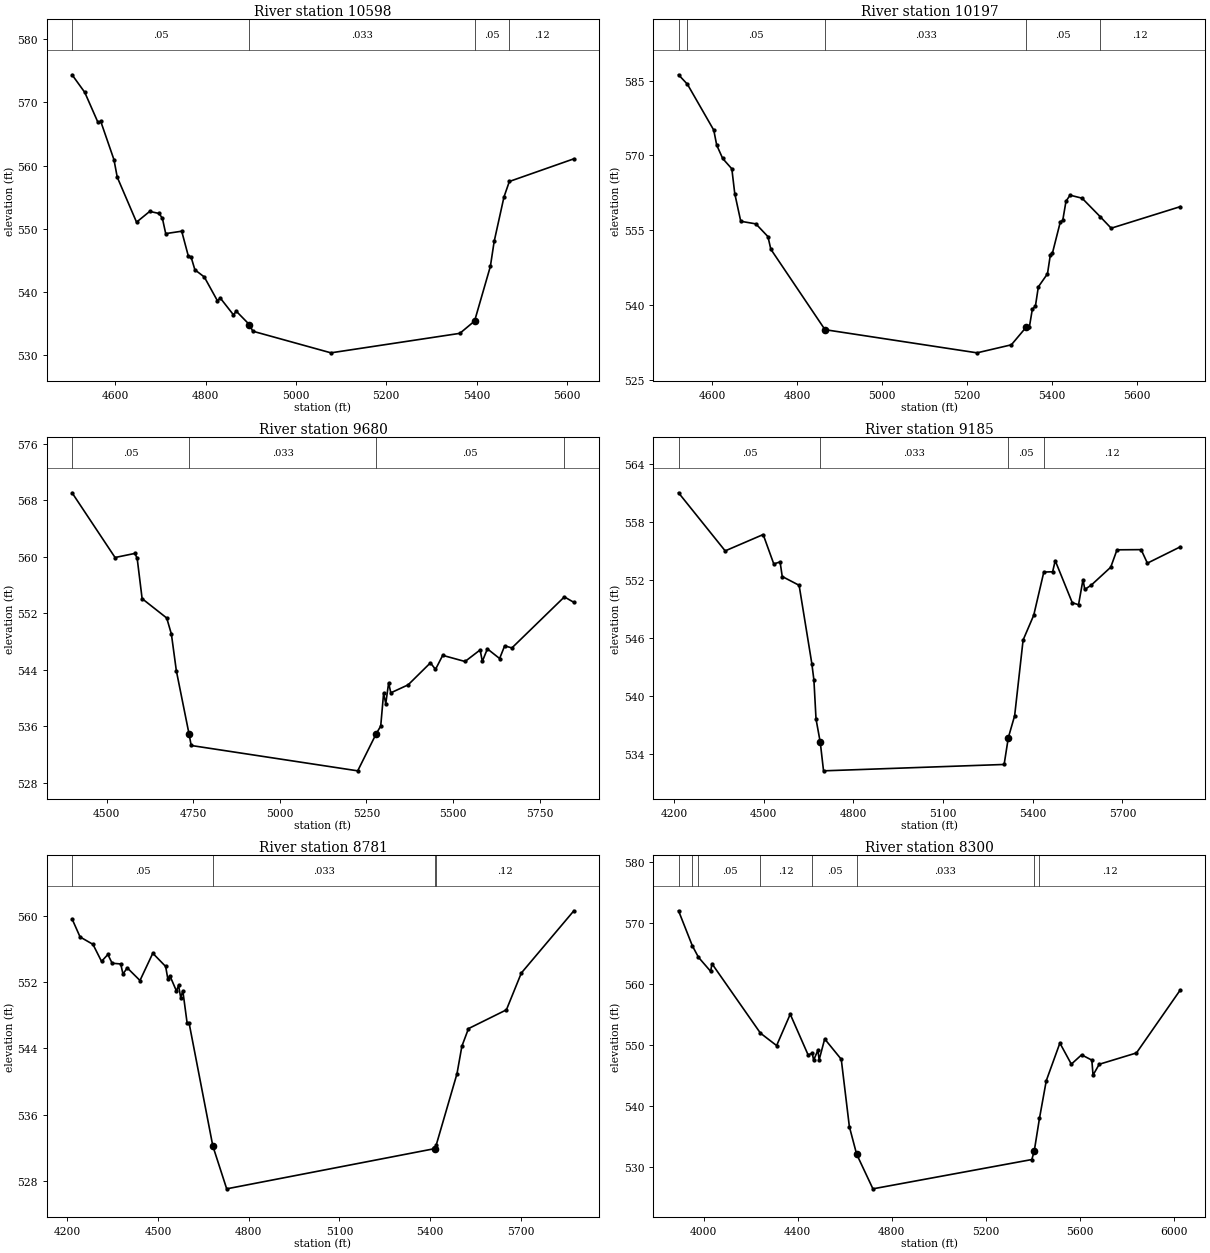
Type RM Length L Ch R = 1 ,10598   ,401,401,401
BEGIN DESCRIPTION:
Jones Branch 23.0
END DESCRIPTION:
XS GIS Cut Line= 3
        2396229.        7036260.        2396629.        7035960.
      2397191.44      7035721.79
#Sta/Elev= 30
  4504.4  574.34  4532.5  571.56  4561.7  566.82  4567.9  566.97  4597.1  560.93
  4604.4  558.16  4647.1  551.05  4676.3  552.75  4697.1  552.42  4704.4  551.64
  4711.7  549.24  4747.1  549.62  4761.7  545.71  4767.9  545.53  4776.3  543.52
  4797.1  542.39  4826.3  538.61  4832.5  539.06  4861.7   536.4  4867.9  536.98
  4897.1  534.85  4904.4  533.82  5077.4   530.4  5362.8  533.48  5395.4  535.42
  5430.4  544.07  5438.8  548.01  5460.5  555.03  5472.4  557.48  5615.2  561.06
#Mann= 4 ,-1 , 0
  4504.4     .05       0  4897.1    .033       0  5395.4     .05       0
  5472.4     .12       0
Bank Sta=4897.1,5395.4
XS Rating Curve= 0 ,0
Exp/Cntr=0.3,0.1

Type RM Length L Ch R = 1 ,10197   ,517,517,517
BEGIN DESCRIPTION:
Jones Branch 22.0
END DESCRIPTION:
XS GIS Cut Line= 3
      2396466.16      7036624.24      2397104.85      7036018.51
      2397232.59      7035746.56
#Sta/Elev= 30
  4521.2  586.18  4542.1  584.28  4604.1  575.07    4611  572.07  4625.1  569.38
  4646.6  567.31  4653.5  562.33  4667.6  556.78  4703.2  556.26  4731.5  553.71
  4738.4  551.17  4865.8  535.03  5223.6  530.38  5304.3  531.99  5339.5  535.56
  5346.8  535.61  5353.7  539.15  5360.9  539.73  5367.8  543.62  5389.3  546.24
  5396.1  550.06  5400.9  550.37  5419.7  556.71  5425.2  556.94  5432.9  560.81
  5442.5  562.02  5470.8  561.41  5513.5  557.69  5539.2  555.39  5701.9  559.72
#Mann= 5 ,-1 , 0
  4521.2    .075       0  4542.1     .05       0  4865.8    .033       0
  5339.5     .05       0  5513.5     .12       0
Bank Sta=4865.8,5339.5
XS Rating Curve= 0 ,0
Exp/Cntr=0.3,0.1

Type RM Length L Ch R = 1 ,9680    ,495,495,495
BEGIN DESCRIPTION:
Jones Branch 21.0
END DESCRIPTION:
XS GIS Cut Line= 3
       2396799.9      7036875.65      2397319.14      7036438.83
      2397784.34      7035825.42
#Sta/Elev= 30
  4400.3  569.07  4524.4   559.9  4581.6  560.48  4588.2  559.79  4602.5  554.07
  4673.5  551.33    4687  549.05  4701.3  543.85  4737.7  534.96  4744.2  533.27
  5224.8  529.68  5278.2  534.94  5291.2  536.02  5299.5  540.64  5305.8  539.21
  5314.1  542.15  5320.3  540.73  5370.3  541.86  5434.7  544.98  5449.3  544.05
  5470.1  546.04  5534.6  545.17  5578.2  546.81  5584.5  545.18  5599.1  546.96
  5634.4  545.59    5649  547.39  5669.8  547.09  5821.3  554.32  5848.7  553.55
#Mann= 4 ,-1 , 0
  4400.3     .05       0  4737.7    .033       0  5278.2     .05       0
  5821.3     .12       0
Bank Sta=4737.7,5278.2
XS Rating Curve= 0 ,0
Exp/Cntr=0.3,0.1

Type RM Length L Ch R = 1 ,9185    ,404,404,404
BEGIN DESCRIPTION:
Jones Branch 20.0
END DESCRIPTION:
XS GIS Cut Line= 3
      2397117.22      7037258.86      2398003.19      7036389.38
      2398364.88      7036142.78
#Sta/Elev= 30
  4214.6  561.01  4370.7     555  4497.8  556.69  4533.3  553.65  4554.4  553.86
  4561.6  552.35  4618.1  551.44  4660.6  543.35  4667.6  541.64  4674.7   537.6
  4688.9  535.19  4699.8  532.25  5304.1  532.91  5318.2  535.69  5339.3  537.95
  5367.6  545.78  5403.1  548.34  5436.9  552.81  5466.4  552.84  5475.1  553.99
  5532.1  549.64  5553.1  549.43    5568  552.02  5574.1  551.01  5596.1  551.47
  5660.8  553.31  5681.8  555.11  5762.5  555.13  5783.5  553.73  5893.7  555.42
#Mann= 4 ,-1 , 0
  4214.6     .05       0  4688.9    .033       0  5318.2     .05       0
  5436.9     .12       0
Bank Sta=4688.9,5318.2
XS Rating Curve= 0 ,0
Exp/Cntr=0.3,0.1

Type RM Length L Ch R = 1 ,8781    ,481,481,481
BEGIN DESCRIPTION:
Jones Branch 19.0
END DESCRIPTION:
XS GIS Cut Line= 3
       2397467.5       7037506.1       2398184.5      7036719.05
      2398468.85      7036195.68
#Sta/Elev= 30
  4215.5  559.59    4242  557.42  4284.6  556.53    4313  554.48  4333.9  555.31
  4348.1  554.26  4376.5  554.17  4383.9  552.96  4398.1   553.7  4440.2  552.18
  4482.6  555.46  4525.1  553.87  4532.5  552.35  4539.3  552.74  4560.9  550.91
  4567.7  551.59  4575.1  550.11  4581.9  550.95  4596.1  547.08  4602.8  547.04
  4681.2  532.27  4727.1  527.11  5415.7  531.95  5420.3  532.37  5489.1  540.96
  5505.3  544.27  5527.1  546.39  5652.6  548.65    5702  553.08  5875.8  560.57
#Mann= 4 ,-1 , 0
  4215.5     .05       0  4681.2    .033       0  5415.7     .05       0
  5420.3     .12       0
Bank Sta=4681.2,5415.7
XS Rating Curve= 0 ,0
Exp/Cntr=0.3,0.1

Type RM Length L Ch R = 1 ,8300    ,362,362,362
BEGIN DESCRIPTION:
Jones Branch 18.0
END DESCRIPTION:
XS GIS Cut Line= 4
      2397372.73      7037740.99      2398081.48      7037436.07
      2398398.79      7037172.33      2398604.42      7036242.87
#Sta/Elev= 30
  3892.8  572.07  3951.5  566.33  3977.6  564.44  4029.6  562.12  4035.1  563.38
  4241.5  551.98  4310.3  549.94  4368.3  555.09  4444.4  548.41    4462  548.68
  4467.9  547.54    4486  549.17  4491.4   547.6    4515  551.03  4585.5  547.69
    4620  536.63  4650.8  532.13  4720.3  526.42  5396.8  531.23  5407.1  532.64
  5429.3     538  5458.3  544.18  5516.2  550.35  5564.9  546.89  5608.6  548.42
  5652.2  547.55  5657.3  545.09  5683.6  546.87  5842.1  548.73  6028.9  559.08
#Mann= 8 ,-1 , 0
  3892.8     .05       0  3951.5     .12       0  3977.6     .05       0
  4241.5     .12       0    4462     .05       0  4650.8    .033       0
  5407.1     .05       0  5429.3     .12       0
Bank Sta=4650.8,5407.1
XS Rating Curve= 0 ,0
Exp/Cntr=0.3,0.1

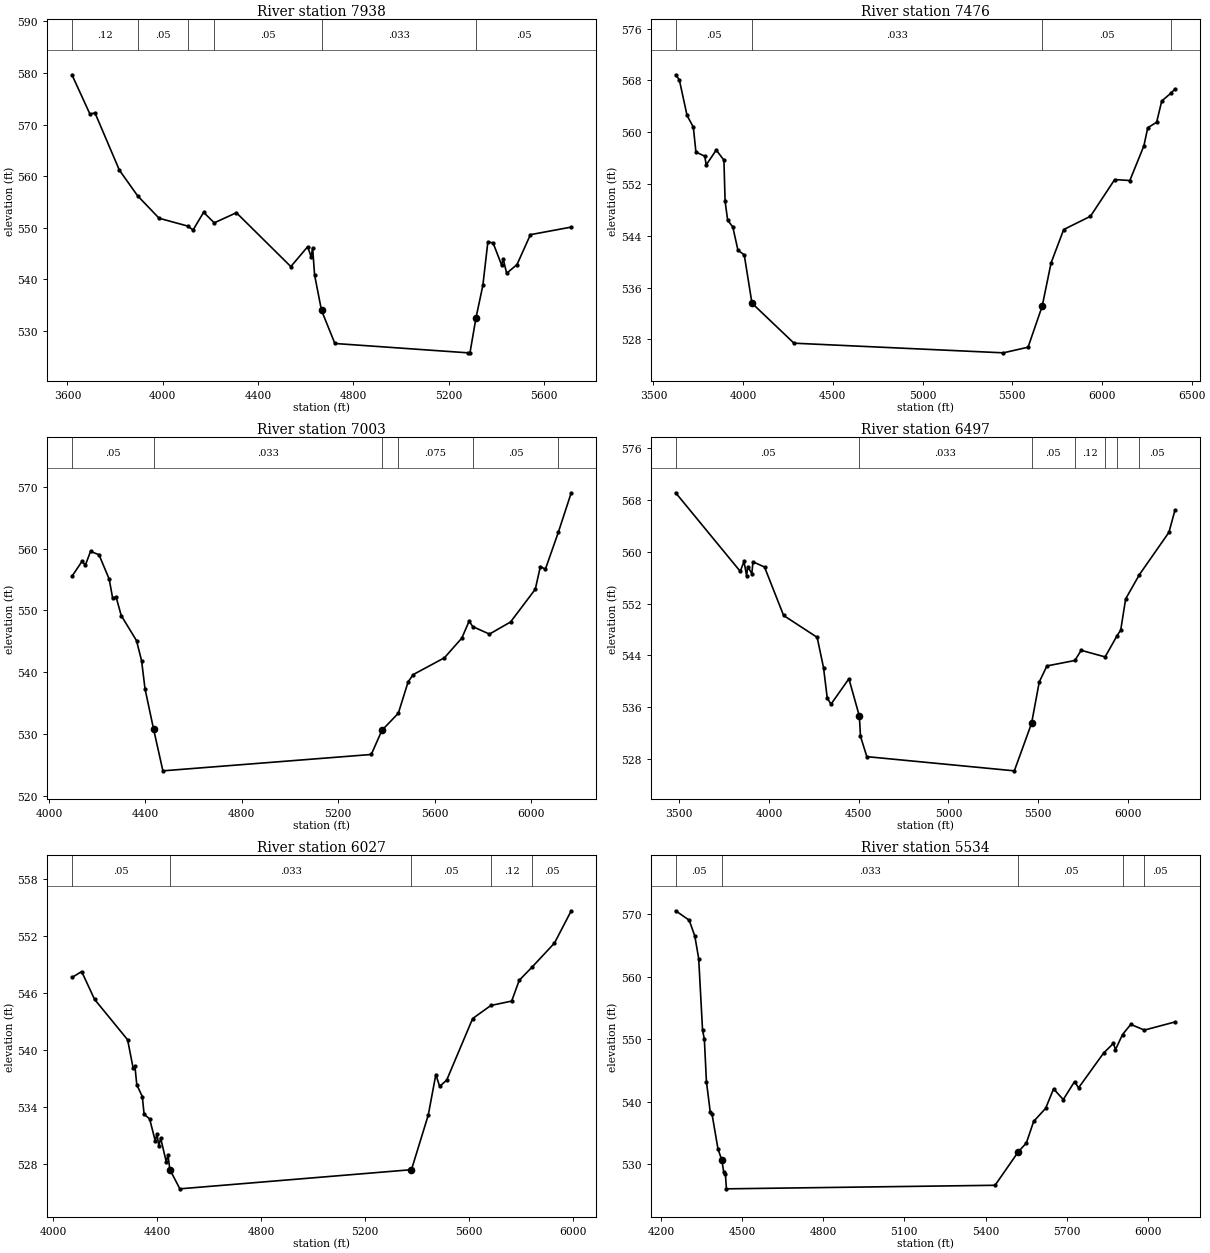
Type RM Length L Ch R = 1 ,7938    ,462,462,462
BEGIN DESCRIPTION:
Jones Branch 17.0
END DESCRIPTION:
XS GIS Cut Line= 3
      2397364.49      7038111.87      2397916.65      7037992.37
      2399129.03      7037059.97
#Sta/Elev= 30
  3619.1  579.63  3694.5  572.03  3715.8  572.25  3818.1  561.16  3894.7  556.19
  3984.7  551.85  4104.5  550.34  4127.3  549.58  4171.4     553    4216  550.96
  4308.9  552.92  4537.3  542.49  4607.9  546.34  4622.4  544.39  4628.7  546.14
  4636.9  540.86    4666     534  4722.1   527.6    5281  525.79  5288.7  525.79
  5313.8  532.54  5342.8  538.86  5363.7  547.25  5385.5  547.09  5421.7  542.76
    5428  543.98  5442.5  541.19    5486  542.88  5542.2  548.67  5713.5  550.14
#Mann= 6 ,-1 , 0
  3619.1     .12       0  3894.7     .05       0  4104.5     .12       0
    4216     .05       0    4666    .033       0  5313.8     .05       0
Bank Sta=4666,5313.8
XS Rating Curve= 0 ,0
Exp/Cntr=0.3,0.1

Type RM Length L Ch R = 1 ,7476    ,473,473,473
BEGIN DESCRIPTION:
Jones Branch 16.0
END DESCRIPTION:
XS GIS Cut Line= 3
      2397871.34      7038841.24      2398374.06      7038239.62
      2399890.49      7036937.47
#Sta/Elev= 30
  3624.2  568.86  3644.7  568.07  3687.6  562.58  3722.7  560.77  3737.1  556.92
  3786.5  556.29  3794.3  554.93  3850.3  557.24  3893.2  555.67  3899.7  549.32
    3914   546.4  3942.7  545.35  3971.3  541.77  4006.4  541.05  4049.4  533.59
  4283.6  527.41  5450.4  525.92  5588.2  526.79  5666.9  533.12  5716.5   539.8
  5786.8  544.96    5936  547.01    6071  552.68  6155.5  552.53  6233.7  557.88
  6255.4  560.68  6304.8  561.53  6333.3  564.81  6383.1  565.99    6407  566.67
#Mann= 4 ,-1 , 0
  3624.2     .05       0  4049.4    .033       0  5666.9     .05       0
  6383.1     .12       0
Bank Sta=4049.4,5666.9
XS Rating Curve= 0 ,0
Exp/Cntr=0.3,0.1

Type RM Length L Ch R = 1 ,7003    ,506,506,506
BEGIN DESCRIPTION:
Jones Branch 15.0
END DESCRIPTION:
XS GIS Cut Line= 3
      2398588.32      7038598.16      2399309.48      7037922.32
       2399902.9      7037015.71
#Sta/Elev= 30
  4095.3  555.52  4137.1  557.94  4151.1  557.33  4172.3  559.55  4207.5  559.02
    4250  555.05  4264.2  551.97  4278.3   552.2  4299.8  549.16  4363.3   545.1
  4384.3  541.84  4398.5   537.3  4434.1  530.76  4472.7  524.01  5337.4  526.66
  5381.6  530.57  5449.7  533.34  5490.2  538.41  5511.3   539.6  5640.9  542.32
  5713.3  545.52  5743.5  548.27  5758.6  547.37  5827.8  546.16  5915.3  548.12
  6017.9  553.42    6039  557.09  6060.1  556.69  6113.7  562.66  6167.2  569.05
#Mann= 6 ,-1 , 0
  4095.3     .05       0  4434.1    .033       0  5381.6     .05       0
  5449.7    .075       0  5758.6     .05       0  6113.7     .12       0
Bank Sta=4434.1,5381.6
XS Rating Curve= 0 ,0
Exp/Cntr=0.3,0.1

Type RM Length L Ch R = 1 ,6497    ,470,470,470
BEGIN DESCRIPTION:
Jones Branch 14.0
END DESCRIPTION:
XS GIS Cut Line= 3
      2398369.92      7039224.51        2399579.        7038310.
       2400537.5      7037481.38
#Sta/Elev= 30
  3479.4   569.1  3839.4  556.97  3860.3   558.5  3874.8  556.29  3881.1   557.7
  3903.9  556.62  3910.2  558.45  3974.7  557.64  4080.9  550.17  4268.1  546.79
  4303.5  542.11  4324.3  537.42  4345.1  536.47    4445   540.4  4503.2  534.64
  4509.5  531.53  4544.9  528.38  5367.1  526.19  5463.2  533.53    5506  539.91
  5548.7  542.38  5704.6  543.22  5739.6  544.79    5873  543.77  5940.1  547.06
    5960  547.91  5987.5  552.72    6064  556.46  6228.8     563  6262.4  566.42
#Mann= 7 ,-1 , 0
  3479.4     .05       0  4503.2    .033       0  5463.2     .05       0
  5704.6     .12       0    5873     .05       0  5940.1     .12       0
    6064     .05       0
Bank Sta=4503.2,5463.2
XS Rating Curve= 0 ,0
Exp/Cntr=0.3,0.1

Type RM Length L Ch R = 1 ,6027    ,493,493,493
BEGIN DESCRIPTION:
Jones Branch 13.0
END DESCRIPTION:
XS GIS Cut Line= 3
      2399268.68      7039262.58        2399929.        7038610.
       2400724.7      7038015.57
#Sta/Elev= 30
  4071.6  547.63    4109  548.26  4158.5  545.33  4285.8  541.06    4307  538.09
    4314  538.25  4321.2  536.31  4342.3  535.07  4349.4  533.19  4370.6  532.71
  4391.9  530.41  4398.9   531.1    4406  529.85    4413  530.68  4434.3  528.21
  4441.3  528.88  4448.4  527.37  4486.9  525.33  5378.3  527.35  5442.9  533.11
  5472.1  537.39  5486.7  536.14  5513.8   536.8  5613.8   543.3    5684  544.68
  5763.9  545.14  5793.1  547.34  5842.9  548.74  5928.6  551.26  5993.2  554.67
#Mann= 5 ,-1 , 0
  4071.6     .05       0  4448.4    .033       0  5378.3     .05       0
    5684     .12       0  5842.9     .05       0
Bank Sta=4448.4,5378.3
XS Rating Curve= 0 ,0
Exp/Cntr=0.3,0.1

Type RM Length L Ch R = 1 ,5534    ,380,380,380
BEGIN DESCRIPTION:
Jones Branch 12.0
END DESCRIPTION:
XS GIS Cut Line= 3
        2399579.        7039510.      2400252.91      7038937.09
      2400810.68      7038154.66
#Sta/Elev= 30
  4254.8  570.58  4304.8  569.07  4325.6  566.52  4339.9  562.93  4354.2  551.43
  4360.8  550.03  4368.5   543.2  4382.8  538.28  4389.3  537.98  4411.3   532.4
  4425.4  530.66  4432.2  528.77  4438.7  528.35  4442.4  526.04  5435.3  526.61
  5521.4  531.99  5550.9  533.38  5577.9  536.84  5622.2  538.94  5651.5  542.05
  5687.4  540.34  5729.1  543.22  5743.9  542.22  5836.1  547.77  5872.6  549.34
  5880.4  548.34  5906.4  550.76  5936.9  552.38  5987.1  551.47  6100.2  552.77
#Mann= 5 ,-1 , 0
  4254.8     .05       0  4425.4    .033       0  5521.4     .05       0
  5906.4      .1       0  5987.1     .05       0
Bank Sta=4425.4,5521.4
XS Rating Curve= 0 ,0
Exp/Cntr=0.3,0.1

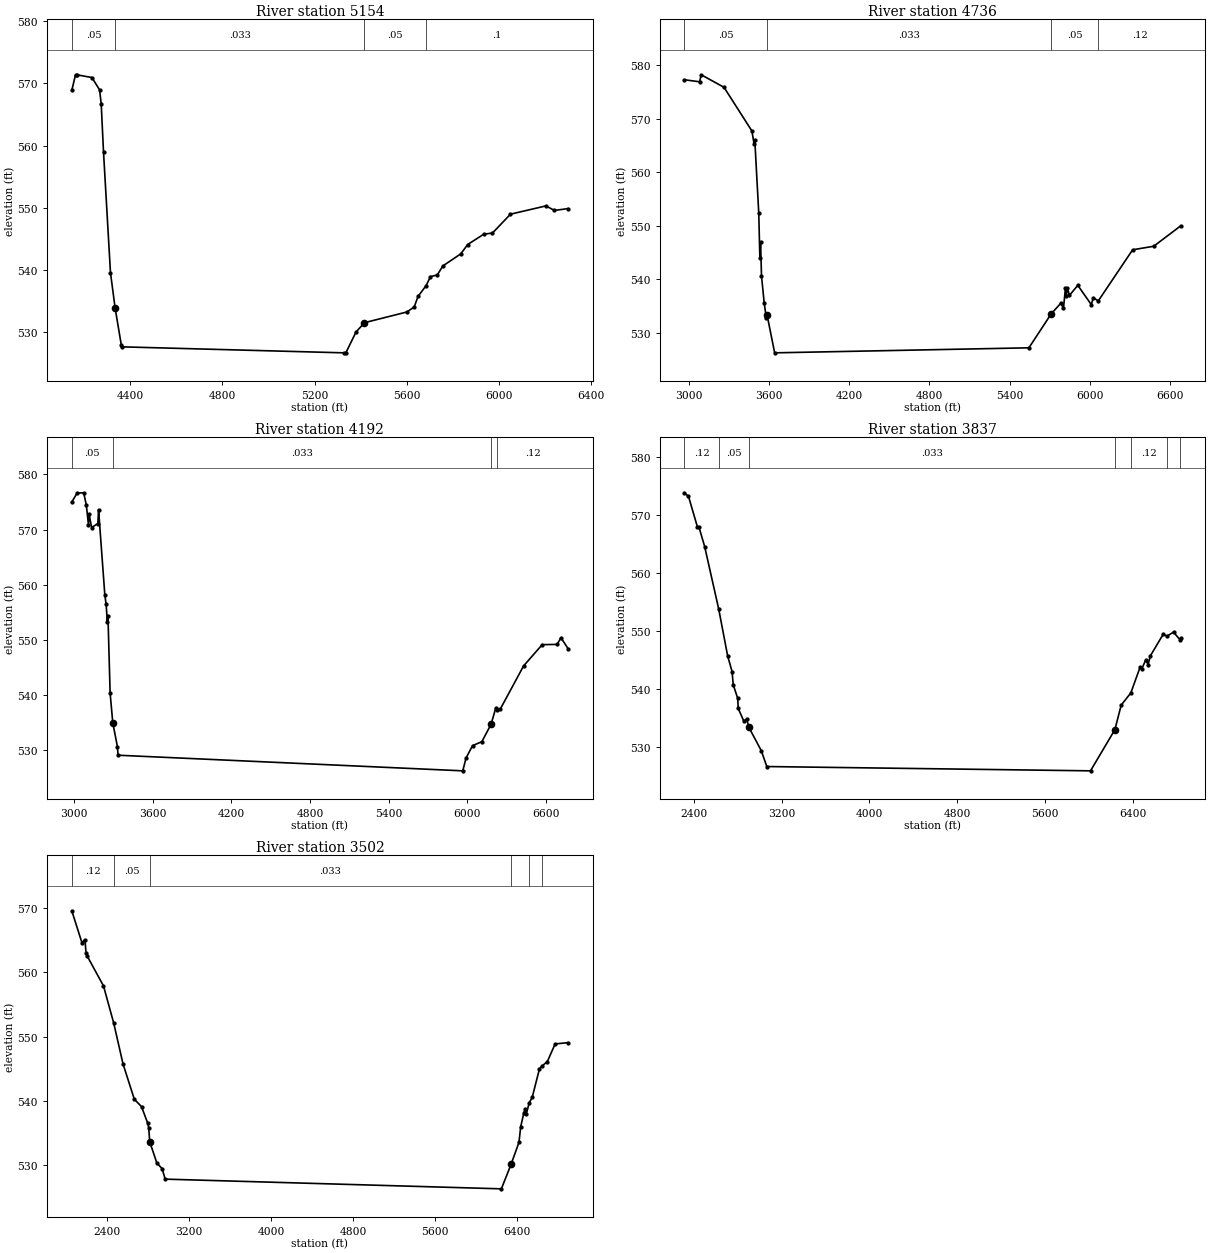
Type RM Length L Ch R = 1 ,5154    ,418,418,418
BEGIN DESCRIPTION:
Jones Branch 11.0
END DESCRIPTION:
XS GIS Cut Line= 4
      2399532.18      7039557.07      2400136.66      7039495.07
       2400485.4      7039223.83      2400896.14      7038200.87
#Sta/Elev= 30
  4147.4  568.85  4163.5  571.35  4168.5  571.36  4234.7  570.92  4267.8  568.94
  4274.9  566.72  4284.9  558.98  4315.1  539.59  4335.2  533.93    4362  527.99
  4367.1  527.68  5327.4  526.72  5335.5  526.72  5379.9  530.07  5416.5  531.56
  5600.4  533.28    5632  534.08  5648.8  535.78    5684  537.53  5702.5  538.96
  5732.1  539.22  5756.3  540.67  5834.3  542.62  5863.9  544.11  5933.8  545.77
  5971.4  545.95  6049.4  548.98  6203.2  550.31  6240.3  549.58  6299.2  549.88
#Mann= 4 ,-1 , 0
  4147.4     .05       0  4335.2    .033       0  5416.5     .05       0
    5684      .1       0
Bank Sta=4335.2,5416.5
XS Rating Curve= 0 ,0
Exp/Cntr=0.3,0.1

Type RM Length L Ch R = 1 ,4736    ,544,544,544
BEGIN DESCRIPTION:
Jones Branch 10.0
END DESCRIPTION:
XS GIS Cut Line= 3
      2398485.98       7040231.3      2400322.66      7039812.82
      2401818.36      7038758.85
#Sta/Elev= 30
  2965.9   577.3  3080.5  576.92  3092.1  578.23  3262.8  575.89  3471.6  567.72
  3488.2  565.24  3493.3  565.99  3522.8   552.4  3531.2  543.98  3536.3  547.02
  3543.4  540.62  3563.9  535.47  3579.3  532.78  3584.5  533.38  3641.9  526.23
  5544.4  527.17  5710.8  533.51  5782.2  535.49  5803.1  534.58  5817.9  538.36
    5824   536.9  5832.7  538.36  5847.5  536.97  5910.2  538.86  6011.2  535.24
    6026  536.54  6063.4  535.94  6320.4   545.5    6478  546.16  6679.4  549.96
#Mann= 4 ,-1 , 0
  2965.9     .05       0  3584.5    .033       0  5710.8     .05       0
  6063.4     .12       0
Bank Sta=3584.5,5710.8
XS Rating Curve= 0 ,0
Exp/Cntr=0.3,0.1

Type RM Length L Ch R = 1 ,4192    ,355,355,355
BEGIN DESCRIPTION:
Jones Branch 9.0
END DESCRIPTION:
XS GIS Cut Line= 3
      2398578.91      7040502.56      2400689.02      7040211.66
       2401755.2      7038938.49
#Sta/Elev= 30
  2980.9     575  3021.4  576.63  3071.8  576.68    3092  574.44  3108.3  570.86
  3113.4  572.77  3132.4  570.38  3180.3  571.11  3185.3  573.64  3233.4  558.11
  3243.4  556.45  3252.2  553.29  3257.2  554.34  3273.7  540.37  3293.9  535.02
  3329.2  530.69  3334.3  529.12  5967.3  526.29  5992.2  528.61  6041.7  530.85
  6113.2  531.58  6183.5  534.74  6219.9  537.72  6227.2  537.29  6255.1  537.54
    6432  545.31    6574  549.16  6688.3   549.2    6717  550.43  6771.6  548.43
#Mann= 4 ,-1 , 0
  2980.9     .05       0  3293.9    .033       0  6183.5     .05       0
  6227.2     .12       0
Bank Sta=3293.9,6183.5
XS Rating Curve= 0 ,0
Exp/Cntr=0.3,0.1

Type RM Length L Ch R = 1 ,3837    ,335,335,335
BEGIN DESCRIPTION:
Jones Branch 8.0
END DESCRIPTION:
XS GIS Cut Line= 4
       2398121.7      7041161.29       2400562.9      7040673.05
      2400973.64      7040277.81      2401764.04      7039045.71
#Sta/Elev= 30
  2313.1  573.76  2351.1  573.15  2432.7  567.87  2447.6  567.79  2498.6   564.5
  2626.7  553.74  2708.1  545.68  2748.4     543  2759.1  540.71  2799.4  538.41
  2804.5  536.66  2855.5  534.47  2881.4  534.82  2901.4  533.41    3014  529.41
    3065  526.66  6015.4  525.92  6237.4     533  6295.1  537.23    6383  539.33
  6467.5  543.77  6482.7  543.47  6519.1  545.01  6540.2   544.2  6561.4  545.72
    6677  549.39  6713.2  549.11    6772  549.78  6829.3  548.51  6836.5  548.74
#Mann= 7 ,-1 , 0
  2313.1     .12       0  2626.7     .05       0  2901.4    .033       0
  6237.4     .05       0    6383     .12       0  6713.2     .05       0
  6829.3     .12       0
Bank Sta=2901.4,6237.4
XS Rating Curve= 0 ,0
Exp/Cntr=0.3,0.1

Type RM Length L Ch R = 1 ,3502    ,0,0,0
BEGIN DESCRIPTION:
Jones Branch 7.0
END DESCRIPTION:
XS GIS Cut Line= 4
      2398090.69      7041308.53      2400601.65      7041083.79
      2401167.39      7040549.05      2401771.46      7039124.06
#Sta/Elev= 30
  2053.8   569.6  2152.5  564.65  2182.6  565.11  2192.7  563.04  2201.7  562.63
  2363.3  557.91  2462.2  552.19  2554.1  545.77  2664.5  540.27  2734.8  539.12
  2795.1  536.55  2805.1  535.85  2815.1  533.65  2885.4  530.31  2935.6  529.49
  2965.7  527.84  6249.6  526.33  6344.9  530.17  6421.4  533.57  6438.4  536.01
  6468.7  538.11  6481.8  538.79  6492.4  537.94  6521.7  539.72  6550.6  540.55
  6621.6  545.01  6643.5  545.41  6698.1  546.12  6774.5  548.88    6901  549.08
#Mann= 6 ,-1 , 0
  2053.8     .12       0  2462.2     .05       0  2815.1    .033       0
  6344.9     .05       0  6521.7     .12       0  6643.5     .05       0
Bank Sta=2815.1,6344.9
XS Rating Curve= 0 ,0
Exp/Cntr=0.3,0.1

Chan Stop Cuts=-1
Use User Specified Reach Order=0
Composite Channel Slope=5