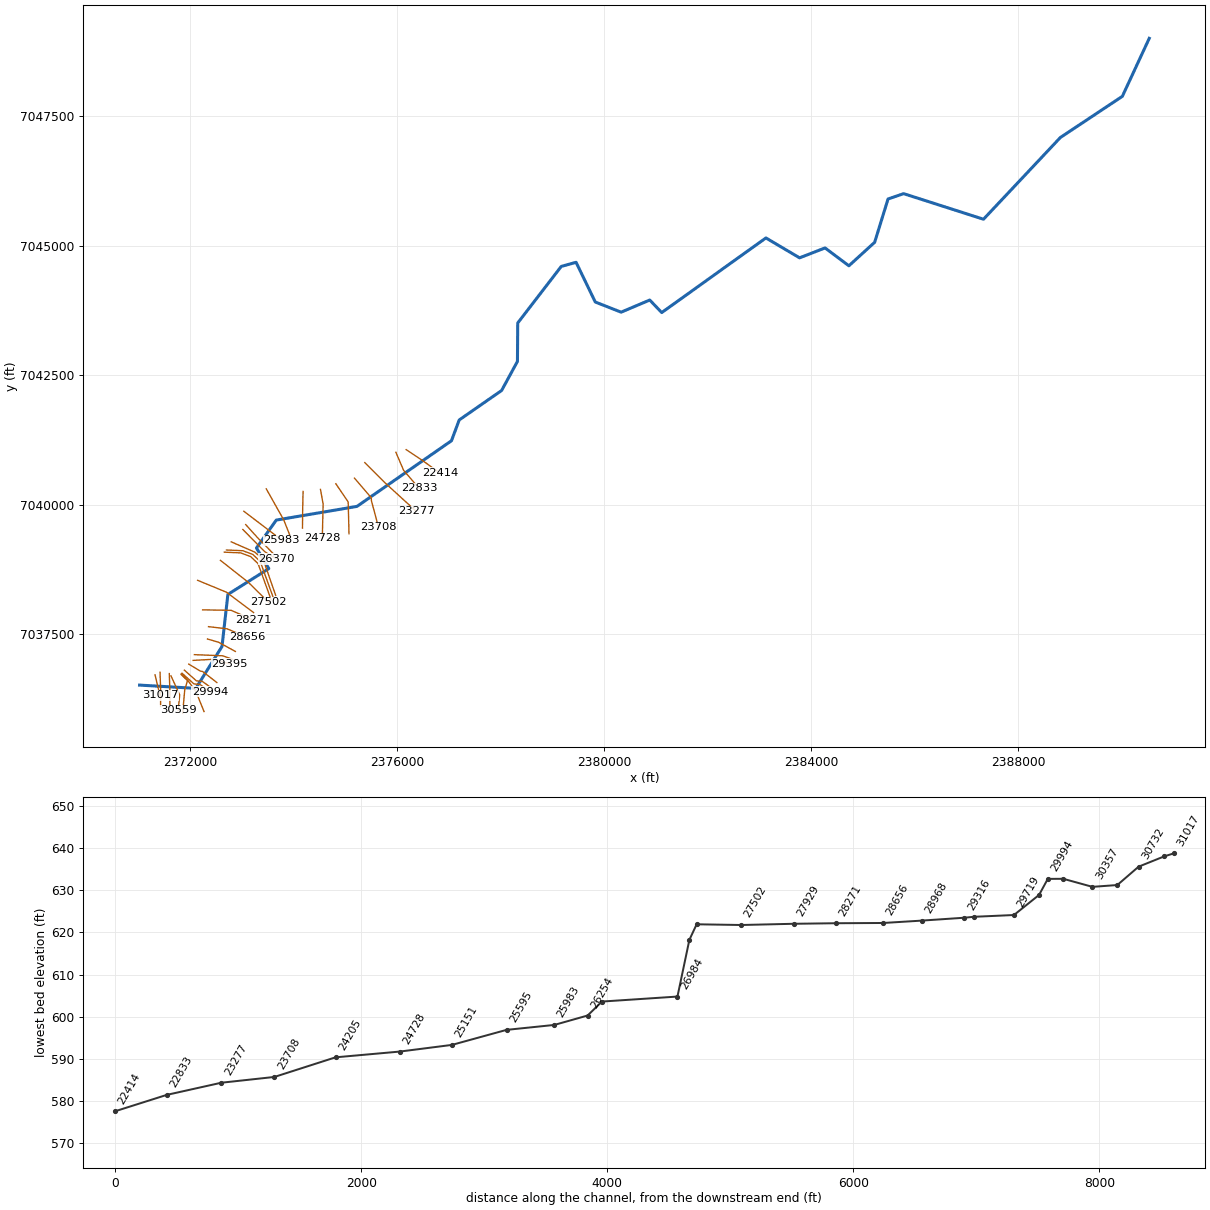
--- Kirkwood Branch.prj (project) ---

Proj Title=Kirkwood Branch Base Level Engineering
Current Plan=p01
Default Exp/Contr=0.3,0.1
English Units
Geom File=g01
Flow File=f01
Plan File=p01
Y Axis Title=Elevation
X Axis Title(PF)=Main Channel Distance
X Axis Title(XS)=Station
BEGIN DESCRIPTION:
Kirkwood Branch
END DESCRIPTION:
DSS Export Rating Curves= 0
DSS Export Rating Curve Sorted= 0
DSS Export Volume Flow Curves= 0
DXF OffsetX= 0
DXF OffsetY= 0
DXF ScaleX= 1
DXF ScaleY= 10

--- Kirkwood Branch.p01 (plan) ---

Plan Title=Multiple Run
Program Version=4.10
Short Identifier=Multiple
Geom File=g01
Flow File=f01
Subcritical Flow
K Sum by GR= 0
Std Step Tol= 0.01
Critical Tol= 0.01
Num of Std Step Trials= 20
Max Error Tol= 0.3
Flow Tol Ratio= 0.001
Split Flow NTrial= 30
Split Flow Tol= 0.02
Split Flow Ratio= 0.02
Log Output Level= 0
Friction Slope Method= 1
Unsteady Friction Slope Method= 2
Unsteady Bridges Friction Slope Method= 1
Parabolic Critical Depth
Global Vel Dist= 1 , 1 , 1
Global Log Level= 0
CheckData=True
Encroach Param=-1 ,0,0, 0
BEGIN DESCRIPTION:
Multiple Run
END DESCRIPTION:
Computation Interval=1HOUR
Output Interval=1HOUR
Run HTab= 0
Run UNet= 0
Run PostProcess= 0
Run WQNet= 0
UNET Theta= 1
UNET Theta Warmup= 1
UNET ZTol= 0.02
UNET ZSATol= 0.05
UNET MxIter= 20
UNET MaxInSteps= 0
UNET DtIC= 0
UNET DtMin= 0
UNET MaxCRTS= 20
UNET WFStab= 2
UNET SFStab= 1
UNET WFX= 1
UNET SFX= 1
UNET DSS MLevel= 4
UNET DZMax Abort= 100
UNET Convert EG Bridges= 0
UNET Use Existing IB Tables=-1
UNET Froude Reduction=False
UNET Froude Limit= 1
UNET Froude Power= 10
UNET Time Slicing=0,0, 5
UNET Junction Losses=0
Instantaneous Interval=1HOUR
Write IC File= 0
Write IC File at Sim End=0
Echo Input=False
Echo Parameters=False
Echo Output=False
Write Detailed= 0
WQ AD Non Conservative
WQ ULTIMATE=-1
WQ Max Comp Step=1HOUR
WQ Output Interval=15MIN
WQ Output Selected Increments= 0
WQ Output face flow=0
WQ Output face velocity=0
WQ Output face area=0
WQ Output face dispersion=0
WQ Output cell volume=0
WQ Output cell surface area=0
WQ Output cell continuity=0
WQ Output cumulative cell continuity=0
WQ Output face conc=0
WQ Output face dconc_dx=0
WQ Output face courant=0
WQ Output face peclet=0
WQ Output face adv mass=0
WQ Output face disp mass=0
WQ Output cell mass=0
WQ Output cell source sink temp=0
WQ Output cell source sink nsm=0
WQ Output MaxMinRange=-1
WQ Daily Max Min Mean=-1
WQ Daily Range=0
WQ Daily Time=0
WQ Create Restart=0
WQ Fixed Restart=0
WQ System Summary=0
WQ Use Fixed Temperature=0
Sorting and Armoring Iterations= 10
XS Update Threshold= 0.02
Hydraulics Update Threshold= 0.02
Energy Slope Method= 1
Volume Change Method= 0
XS Weighting Method= 0
Number of US Weighted Cross Sections= 1
Number of DS Weighted Cross Sections= 1
Upstream XS Weight=0.25
Main XS Weight=0.5
Downstream XS Weight=0.25
Number of DS XS's Weighted with US Boundary= 1
Upstream Boundary Weight= 1
Weight of XSs Associated with US Boundary= 0
Number of US XS's Weighted with DS Boundary= 1
Downstream Boundary Weight= 0.5
Weight of XSs Associated with DS Boundary= 0.5
Sediment Output Level= 4
Mass or Volume Output= 0
Output Increment Type= 1
Profile and TS Output Increment= 10
XS Output Flag= 0
XS Output Increment= 10
Disregard all LS=0
Disregard all Conn=0
Disregard all Breaches=0
Disregard all Pumps=0

--- Kirkwood Branch.f01 (steady flow) ---

Flow Title=Multiple
Number of Profiles=7
Profile Names=10-year,25-year,50-year,1pct_min,100-year,1pct_plu,500-year
River Rch & RM= Kirkwood Branch,Reach-1,31017
     655     903    1109     677    1351    2696    2001
River Rch & RM= Kirkwood Branch,Reach-1,30120
     910    1277    1587     978    1952    3895    2952
River Rch & RM= Kirkwood Branch,Reach-1,27929
    1113    1579    1977    1226    2447    4883    3749
River Rch & RM= Kirkwood Branch,Reach-1,25595
    1407    2020    2550    1593    3179    6342    4941
River Rch & RM= Kirkwood Branch,Reach-1,23708
    1402    2011    2535    1583    3158    6301    4900
River Rch & RM= Kirkwood Branch,Reach-1,23277
    2360    3477    4465    2833    5653   11279    9068
River Rch & RM= Kirkwood Branch,Reach-1,21563
    2664    3938    5066    3219    6423   12816   10332
River Rch & RM= Kirkwood Branch,Reach-1,17902
    2703    3988    5124    3251    6486   12941   10402
River Rch & RM= Kirkwood Branch,Reach-1,14636
    3310    4913    6337    4033    8047   16055   12986
River Rch & RM= Kirkwood Branch,Reach-1,9341
    3410    5065    6537    4162    8304   16568   13412
River Rch & RM= Kirkwood Branch,Reach-1,8500
    3786    5639    7290    4648    9273   18503   15018
River Rch & RM= Kirkwood Branch,Reach-1,6327
    3834    5709    7378    4700    9377   18709   15166
Boundary for River Rch & Prof#=Kirkwood Branch,Reach-1,1
Up Type=0
Dn Type=3
Dn Slope=0.002
Boundary for River Rch & Prof#=Kirkwood Branch,Reach-1,2
Up Type=0
Dn Type=3
Dn Slope=0.002
Boundary for River Rch & Prof#=Kirkwood Branch,Reach-1,3
Up Type=0
Dn Type=3
Dn Slope=0.002
Boundary for River Rch & Prof#=Kirkwood Branch,Reach-1,4
Up Type=0
Dn Type=3
Dn Slope=0.002
Boundary for River Rch & Prof#=Kirkwood Branch,Reach-1,5
Up Type=0
Dn Type=3
Dn Slope=0.002
Boundary for River Rch & Prof#=Kirkwood Branch,Reach-1,6
Up Type=0
Dn Type=3
Dn Slope=0.002
Boundary for River Rch & Prof#=Kirkwood Branch,Reach-1,7
Up Type=0
Dn Type=3
Dn Slope=0.002

--- Kirkwood Branch.g01 (geometry) ---

Geom Title=Existing Conditions
Program Version=4.10

River Reach=Kirkwood Branch ,Reach-1
Reach XY= 30
        2371029.        7036510.      2372115.38      7036446.73
      2372621.01      7037256.65      2372734.46      7038262.45
      2373525.26      7038761.56      2373286.31       7039159.9
      2373669.21      7039699.48      2375227.53      7039963.55
        2377053.      7041232.78      2377201.86      7041633.85
       2378021.2      7042203.79      2378326.94      7042765.85
      2378332.37      7043508.63      2379172.94      7044601.86
      2379459.38      7044681.08      2379830.22      7043913.43
      2380328.99      7043717.53      2380882.31      7043951.98
       2381113.3      7043709.64      2383125.58      7045152.21
      2383775.43      7044767.53      2384267.28      7044958.95
      2384727.56      7044613.58      2385225.49       7045067.8
      2385484.08      7045904.96      2385785.13      7046008.24
      2387327.42      7045513.82      2388812.33      7047093.35
      2390009.23      7047888.98        2390529.        7049010.

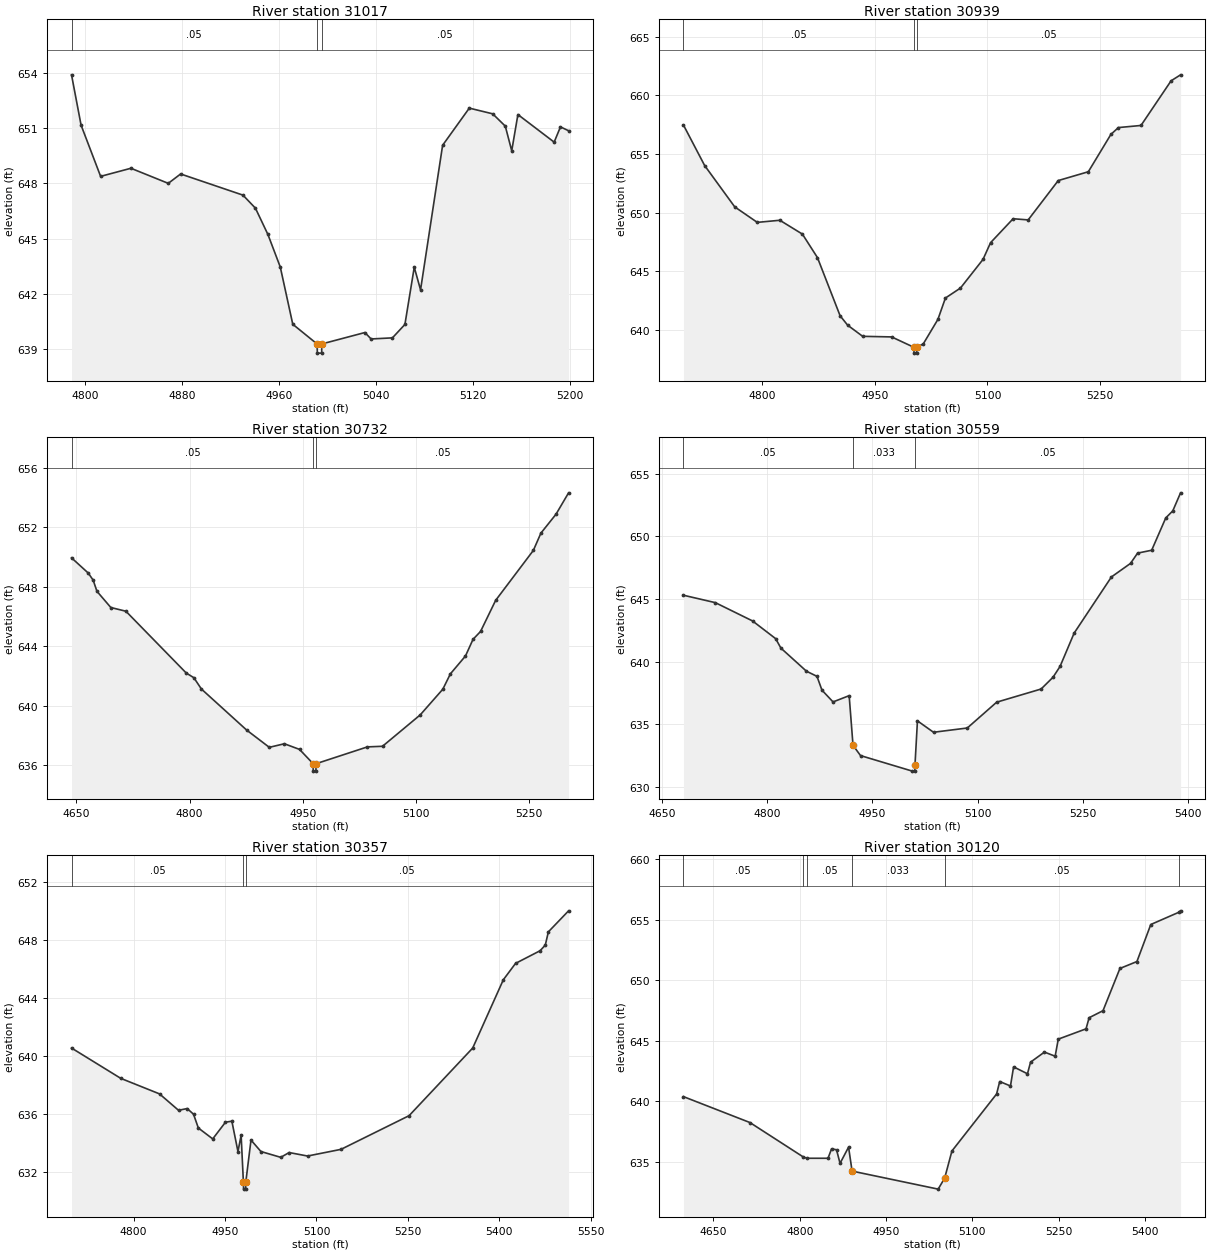
Type RM Length L Ch R = 1 ,31017   ,78,78,78
BEGIN DESCRIPTION:
Kirkwood Branch 65.0
END DESCRIPTION:
XS GIS Cut Line= 3
      2371328.37      7036707.69      2371386.35      7036459.02
      2371426.01      7036309.53
#Sta/Elev= 30
    4789   653.9  4796.9  651.16    4813  648.38    4838  648.82  4868.8     648
    4879  648.51  4930.4  647.36  4940.7  646.65    4951  645.22  4961.2  643.45
  4971.5  640.34  4991.5  639.27  4991.8  638.77  4995.3  638.77  4995.5  639.27
    5031  639.89  5036.1  639.54  5053.7   639.6    5064  640.33  5071.7  643.44
  5076.9  642.21  5095.1  650.07  5117.1  652.09  5136.4  651.78  5146.8  651.11
  5152.1  649.77  5157.2  651.74  5187.1  650.24  5192.3  651.07    5199  650.86
#Mann= 3 ,-1 , 0
    4789     .05       0  4991.5     .05       0  4995.5     .05       0
Bank Sta=4991.5,4995.5
XS Rating Curve= 0 ,0
Exp/Cntr=0.3,0.1

Type RM Length L Ch R = 1 ,30939   ,207,207,207
BEGIN DESCRIPTION:
Kirkwood Branch 64.5
END DESCRIPTION:
XS GIS Cut Line= 3
      2371424.48      7036758.05      2371435.16      7036443.76
      2371435.16      7036097.43
#Sta/Elev= 30
  4695.9  657.46    4724  654.02    4764   650.5    4794  649.18    4824  649.36
    4854  648.18    4874  646.18  4904.1  641.23  4914.1  640.43  4934.1  639.48
  4972.6  639.43  5002.1  638.55  5002.4  638.05  5005.9  638.05  5006.1  638.55
  5014.7  638.84  5034.1  640.92  5044.1  642.74  5064.1  643.59  5094.1  646.03
  5104.1  647.45  5134.1  649.49  5154.1  649.39  5194.1  652.74  5234.1  653.49
  5264.1  656.67  5274.1  657.25  5304.1  657.43  5344.1  661.23  5356.7  661.74
#Mann= 3 ,-1 , 0
  4695.9     .05       0  5002.1     .05       0  5006.1     .05       0
Bank Sta=5002.1,5006.1
XS Rating Curve= 0 ,0
Exp/Cntr=0.3,0.1

Type RM Length L Ch R = 1 ,30732   ,173,173,173
BEGIN DESCRIPTION:
Kirkwood Branch 64.0
END DESCRIPTION:
XS GIS Cut Line= 3
      2371602.97      7036732.08      2371613.65      7036417.83
      2371613.65      7036073.26
#Sta/Elev= 30
  4643.5  649.96  4665.6  648.94  4672.2  648.46  4677.2  647.71  4695.6  646.62
  4715.6  646.37  4795.7  642.21  4805.7   641.9  4815.7  641.14  4875.7  638.38
  4905.7  637.22  4925.7  637.46  4945.8  637.08  4963.8  636.12    4964  635.62
  4967.5  635.62  4967.8  636.12  5035.8  637.25  5055.8  637.29  5105.8   639.4
  5135.8  641.13  5145.8  642.16  5165.8  643.36  5175.8  644.48  5185.8  645.01
  5205.8   647.1  5255.8  650.46  5265.8  651.62  5285.8  652.89  5302.5  654.33
#Mann= 3 ,-1 , 0
  4643.5     .05       0  4963.8    .033       0  4967.8     .05       0
Bank Sta=4963.8,4967.8
XS Rating Curve= 0 ,0
Exp/Cntr=0.3,0.1

Type RM Length L Ch R = 1 ,30559   ,202,202,202
BEGIN DESCRIPTION:
Kirkwood Branch 63.6
END DESCRIPTION:
XS GIS Cut Line= 3
      2371635.02      7036689.36      2371804.34      7036321.72
      2371773.92        7036019.
#Sta/Elev= 30
  4680.5  645.29  4725.9   644.7    4779  643.24  4811.9  641.83  4819.5  641.07
  4855.9  639.23  4870.9  638.82    4878  637.72  4893.8  636.78  4916.8  637.28
  4922.3  633.32    4933   632.5  5006.9  631.26  5010.4  631.26  5010.7  631.76
  5014.2  635.27  5037.1  634.36  5085.3   634.7  5127.2  636.76  5190.6  637.81
  5207.6  638.75  5217.6  639.61  5237.7  642.27  5290.9  646.75  5318.1  647.83
  5328.2  648.65  5348.3  648.88  5368.4  651.46  5378.4  652.02  5389.5  653.46
#Mann= 3 ,-1 , 0
  4680.5     .05       0  4922.3    .033       0  5010.7     .05       0
Bank Sta=4922.3,5010.7
XS Rating Curve= 0 ,0
Exp/Cntr=0.3,0.1

Type RM Length L Ch R = 1 ,30357   ,237,237,237
BEGIN DESCRIPTION:
Kirkwood Branch 63.2
END DESCRIPTION:
XS GIS Cut Line= 4
      2371830.27      7036715.32      2371955.37      7036596.32
      2371901.98      7036425.46      2371860.93      7035963.35
#Sta/Elev= 30
  4698.1  640.55  4778.9  638.46  4842.5  637.39  4873.7  636.26  4887.9  636.38
  4898.3  635.99  4906.2  635.04  4929.8  634.29  4950.7  635.44  4961.2  635.51
  4971.2  633.42  4976.4  634.54  4980.1  631.33  4980.4  630.83  4983.9  630.83
  4984.1  631.33  4992.6  634.21  5008.9  633.42  5041.4  633.02  5055.2  633.35
  5085.4  633.11  5140.3  633.57    5252  635.89  5356.4  640.55  5406.6  645.25
  5426.7  646.38  5466.9  647.25  5475.5  647.64  5480.5  648.55  5513.7     650
#Mann= 3 ,-1 , 0
  4698.1     .05       0  4980.1    .033       0  4984.1     .05       0
Bank Sta=4980.1,4984.1
XS Rating Curve= 0 ,0
Exp/Cntr=0.3,0.1

Type RM Length L Ch R = 1 ,30120   ,126,126,126
BEGIN DESCRIPTION:
Kirkwood Branch 63.0
END DESCRIPTION:
XS GIS Cut Line= 4
      2371834.84      7036729.06        2371963.      7036599.37
       2372118.6      7036381.22      2372274.09      7035998.59
#Sta/Elev= 30
  4598.2  640.38  4713.6  638.24  4805.8  635.41  4812.5  635.29  4849.2  635.29
  4855.4  636.07    4864  635.99  4870.1  634.87  4884.9  636.21    4891  634.23
  5040.5  632.74  5051.8  633.65  5064.4  635.89    5142   640.6  5147.4  641.63
  5166.1  641.26  5171.5  642.84  5195.6  642.27    5201  643.23  5225.1  644.06
  5243.7  643.72  5249.1  645.13  5297.3  645.98  5302.7   646.9  5326.8  647.48
  5356.2  650.97  5385.7  651.54  5409.8   654.6    5458   655.6  5461.5  655.73
#Mann= 6 ,-1 , 0
  4598.2     .05       0  4805.8    .075       0  4812.5     .05       0
    4891    .033       0  5051.8     .05       0    5458     .12       0
Bank Sta=4891,5051.8
XS Rating Curve= 0 ,0
Exp/Cntr=0.3,0.1

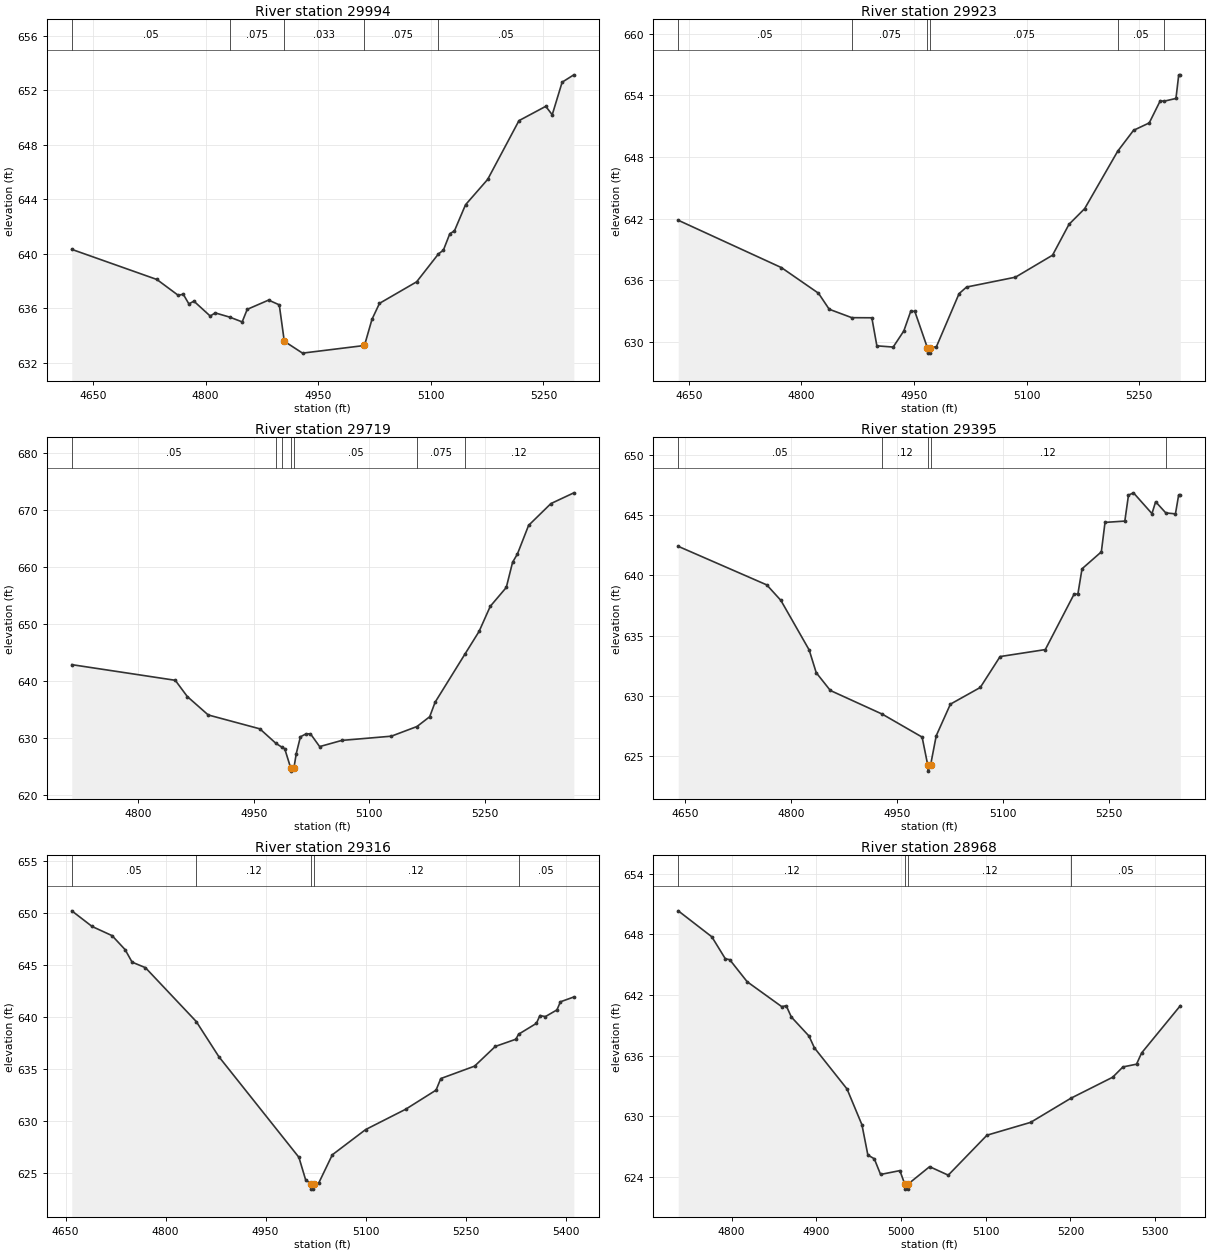
Type RM Length L Ch R = 1 ,29994   ,71,71,71
BEGIN DESCRIPTION:
Kirkwood Branch 62.2
END DESCRIPTION:
XS GIS Cut Line= 4
      2371848.56      7036739.74      2372080.47      7036532.24
      2372190.53      7036525.14      2372391.67      7036381.22
#Sta/Elev= 30
  4621.7  640.33  4735.1  638.12  4763.5  636.96  4770.2  637.04  4777.7  636.33
  4784.4  636.53  4806.1  635.44  4812.8  635.67  4832.1  635.36  4848.7  635.01
  4855.4  635.93  4883.9  636.61  4898.1  636.26  4904.8  633.59  4929.1  632.72
  5011.6  633.28  5021.6   635.2  5031.6  636.37  5081.1  637.95  5110.2     640
  5116.7  640.27  5125.3  641.48  5131.4  641.68  5146.2   643.6  5175.7  645.46
  5217.4  649.77  5253.1  650.82  5261.7   650.2  5274.9  652.59  5290.5  653.13
#Mann= 5 ,-1 , 0
  4621.7     .05       0  4832.1    .075       0  4904.8    .033       0
  5011.6    .075       0  5110.2     .05       0
Bank Sta=4904.8,5011.6
XS Rating Curve= 0 ,0
Exp/Cntr=0.3,0.1

Type RM Length L Ch R = 1 ,29923   ,204,204,204
BEGIN DESCRIPTION:
Kirkwood Branch 62.0
END DESCRIPTION:
XS GIS Cut Line= 4
      2371894.34      7036799.22      2372126.23      7036591.74
       2372236.3      7036584.64      2372437.45      7036440.71
#Sta/Elev= 30
  4635.9  641.84  4773.4  637.23  4822.7  634.74    4837  633.18  4867.1  632.36
  4893.8  632.35  4900.5  629.62  4922.2   629.5  4936.4  631.07  4945.6  632.98
    4951  632.98  4967.9  629.41  4968.1  628.91  4971.6  628.91  4971.9  629.41
  4979.9  629.55    5010   634.7    5020  635.34  5085.1   636.3  5134.5  638.44
  5156.4  641.44  5177.3  642.97  5221.3  648.56  5242.4  650.59  5263.3  651.31
    5278  653.47  5282.8  653.42  5298.9  653.69  5302.6  655.99  5304.7  655.99
#Mann= 6 ,-1 , 0
  4635.9     .05       0  4867.1    .075       0  4967.9     .07       0
  4971.9    .075       0  5221.3     .05       0  5282.8     .12       0
Bank Sta=4967.9,4971.9
XS Rating Curve= 0 ,0
Exp/Cntr=0.3,0.1

Type RM Length L Ch R = 1 ,29719   ,324,324,324
BEGIN DESCRIPTION:
Kirkwood Branch 61.0
END DESCRIPTION:
XS GIS Cut Line= 4
      2371979.79      7036915.15      2372199.46      7036782.43
      2372248.27      7036771.75      2372521.38      7036559.68
#Sta/Elev= 30
  4713.3  642.85  4847.8   640.1  4863.4  637.25  4890.6  634.01  4957.7  631.57
  4978.6  629.02  4986.5  628.33    4990  628.08  4997.9  624.64  4998.1  624.14
  5001.9  624.64    5005  627.22  5010.4  630.17  5017.7  630.69  5023.5  630.69
  5035.4  628.45  5064.3  629.54  5128.6  630.28  5161.9  631.98  5178.4   633.7
  5185.4  636.24  5223.9  644.64  5242.6   648.7  5257.1   653.1  5277.9  656.41
  5286.1  660.84  5292.4   662.3  5306.9  667.32  5335.9  671.15  5365.7  673.04
#Mann= 7 ,-1 , 0
  4713.3     .05       0  4978.6     .12       0  4986.5     .05       0
  4997.9    .033       0  5001.9     .05       0  5161.9    .075       0
  5223.9     .12       0
Bank Sta=4997.9,5001.9
XS Rating Curve= 0 ,0
Exp/Cntr=0.3,0.1

Type RM Length L Ch R = 1 ,29395   ,79,79,79
BEGIN DESCRIPTION:
Kirkwood Branch 60.2
END DESCRIPTION:
XS GIS Cut Line= 3
      2372063.59      7036987.47      2372471.35      7037009.66
      2372762.66      7036923.66
#Sta/Elev= 30
  4639.7  642.42  4765.3  639.21  4785.3  637.92  4825.4   633.8  4835.4  631.91
  4855.4  630.43  4929.1  628.46  4985.6  626.55  4993.6  624.22  4993.9  623.72
  4997.6  624.22  5005.6  626.66  5025.7  629.29  5068.1  630.68  5096.2  633.25
  5160.3  633.83  5201.3  638.46  5206.5  638.44  5212.4  640.55  5239.8  641.96
    5245  644.41  5273.1  644.52  5278.3  646.68  5285.4  646.87  5311.6  645.14
  5316.8  646.13  5331.2   645.2  5344.9  645.12  5349.4  646.67  5351.8  646.67
#Mann= 5 ,-1 , 0
  4639.7     .05       0  4929.1     .12       0  4993.6     .07       0
  4997.6     .12       0  5331.2     .05       0
Bank Sta=4993.6,4997.6
XS Rating Curve= 0 ,0
Exp/Cntr=0.3,0.1

Type RM Length L Ch R = 1 ,29316   ,348,348,348
BEGIN DESCRIPTION:
Kirkwood Branch 60.0
END DESCRIPTION:
XS GIS Cut Line= 3
      2372088.56      7037098.43      2372635.02      7037076.24
       2372829.2      7037006.89
#Sta/Elev= 30
  4659.4  650.18  4689.9  648.68  4719.9   647.8  4739.4  646.46  4749.9  645.26
  4769.9  644.73  4846.1  639.57    4880   636.2  5000.1  626.55  5010.1  624.41
  5018.1     624  5018.4   623.5  5021.9   623.5  5022.1     624  5030.1  624.12
  5050.2  626.79  5100.2  629.21  5160.3  631.16  5205.8  632.99  5212.9   634.1
  5263.6  635.29  5294.7  637.18  5325.5  637.87  5329.6  638.35  5356.3  639.39
  5361.6  640.14  5369.8  640.04  5387.1  640.68  5392.4  641.46  5412.5  641.92
#Mann= 5 ,-1 , 0
  4659.4     .05       0  4846.1     .12       0  5018.1     .07       0
  5022.1     .12       0  5329.6     .05       0
Bank Sta=5018.1,5022.1
XS Rating Curve= 0 ,0
Exp/Cntr=0.3,0.1

Type RM Length L Ch R = 1 ,28968   ,312,312,312
BEGIN DESCRIPTION:
Kirkwood Branch 59.0
END DESCRIPTION:
XS GIS Cut Line= 3
      2372340.95      7037400.82      2372557.34      7037337.01
      2372879.04      7037159.98
#Sta/Elev= 30
    4737  650.32  4776.7  647.75  4792.6  645.58  4797.8  645.49  4818.4  643.31
  4859.2  640.85  4864.5  640.94  4870.5  639.83  4891.4  637.94  4897.8  636.77
  4936.3  632.71  4953.9  629.17  4960.9  626.18  4968.5  625.81  4975.9  624.26
  4998.7  624.64  5004.4  623.31  5004.6  622.81  5008.1  622.81  5008.4  623.31
  5033.8  625.03  5055.8  624.19  5101.5  628.14  5153.1  629.41  5200.5  631.79
  5249.9  633.87  5262.1  634.89  5278.1  635.16  5284.1  636.27  5329.8  640.94
#Mann= 4 ,-1 , 0
    4737     .12       0  5004.4     .07       0  5008.4     .12       0
  5200.5     .05       0
Bank Sta=5004.4,5008.4
XS Rating Curve= 0 ,0
Exp/Cntr=0.3,0.1

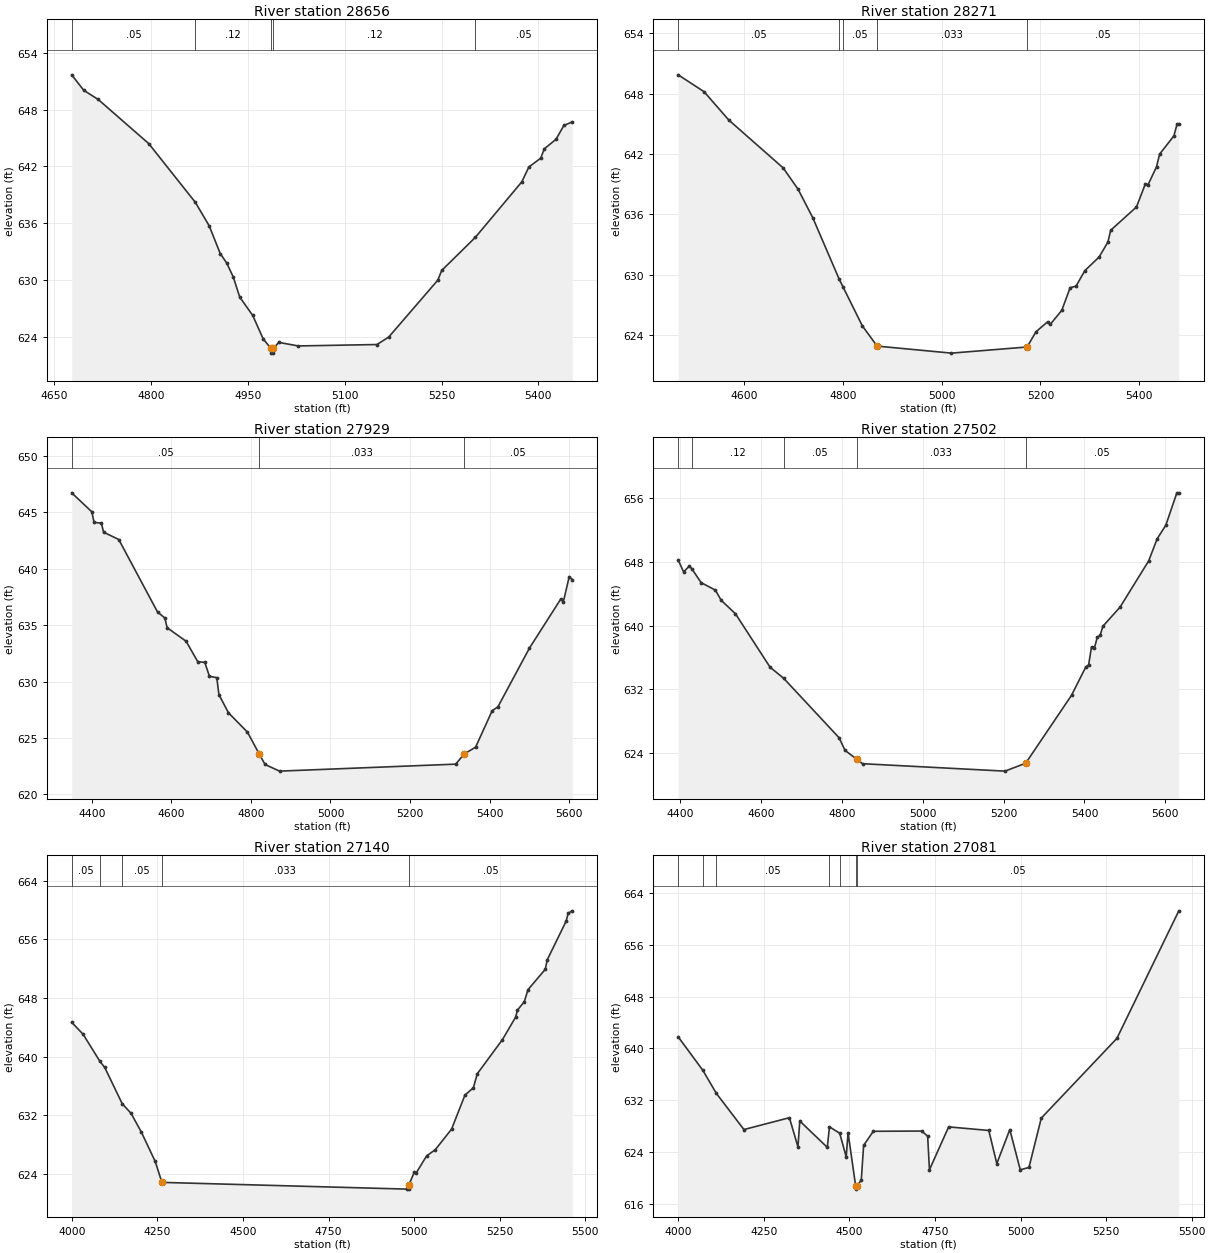
Type RM Length L Ch R = 1 ,28656   ,385,385,385
BEGIN DESCRIPTION:
Kirkwood Branch 58.0
END DESCRIPTION:
XS GIS Cut Line= 3
      2372360.43      7037639.38      2372718.24      7037597.77
      2373101.08      7037436.87
#Sta/Elev= 30
    4677   651.7  4695.7  650.06  4717.9   649.1  4796.4  644.42  4868.7  638.19
    4890  635.72  4907.1  632.79  4917.2  631.78  4927.2  630.32  4937.3  628.18
  4957.4  626.24  4973.6  623.76  4985.6  622.75  4985.9  622.25  4989.4  622.25
  4989.6  622.75  4997.7  623.39  5027.9  623.01  5149.8  623.16  5168.1  623.95
  5244.1  629.97  5250.2     631  5302.3   634.5  5374.3  640.38  5385.2  641.95
  5403.6  642.88    5409  643.86  5427.3  644.88  5439.4  646.34  5452.5  646.72
#Mann= 5 ,-1 , 0
    4677     .05       0  4868.7     .12       0  4985.6     .07       0
  4989.6     .12       0  5302.3     .05       0
Bank Sta=4985.6,4989.6
XS Rating Curve= 0 ,0
Exp/Cntr=0.3,0.1

Type RM Length L Ch R = 1 ,28271   ,342,342,342
BEGIN DESCRIPTION:
Kirkwood Branch 57.0
END DESCRIPTION:
XS GIS Cut Line= 3
      2372246.62      7037963.96      2372795.92      7037955.63
      2373220.34      7037769.77
#Sta/Elev= 30
  4467.2  649.87  4519.6  648.19  4569.6  645.37  4679.6  640.61  4709.6   638.5
  4739.6  635.64  4793.1  629.52  4801.2  628.72  4839.6  624.91  4869.6  622.89
    5020  622.19    5173   622.8  5190.9  624.31  5214.3   625.3  5219.7  625.04
  5243.1  626.44  5260.1   628.7    5272  628.85  5289.9   630.4  5318.7  631.75
  5336.5  633.24  5342.1  634.41  5394.3  636.73  5412.2  639.02  5417.7  638.94
  5434.8  640.72  5441.1  641.99  5469.9  643.79  5476.4  644.97  5479.9  644.97
#Mann= 5 ,-1 , 0
  4467.2     .05       0  4793.1     .12       0  4801.2     .05       0
  4869.6    .033       0    5173     .05       0
Bank Sta=4869.6,5173
XS Rating Curve= 0 ,0
Exp/Cntr=0.3,0.1

Type RM Length L Ch R = 1 ,27929   ,427,427,427
BEGIN DESCRIPTION:
Kirkwood Branch 56.0
END DESCRIPTION:
XS GIS Cut Line= 3
      2372149.56      7038535.42      2372707.15      7038305.17
      2373231.49      7037911.22
#Sta/Elev= 30
  4349.1  646.74  4399.9  645.05  4405.3  644.11  4423.8  644.06  4429.2  643.25
  4467.5   642.6    4565  636.17  4583.5  635.64    4589  634.78  4636.8  633.58
  4666.1  631.77  4683.9   631.7  4695.5  630.47    4714  630.35  4719.4  628.84
  4743.3  627.24  4791.1  625.52  4820.5   623.6  4835.4  622.65  4871.9  622.06
    5315  622.68  5335.9  623.57    5365  624.19  5406.7  627.42  5421.2  627.77
  5500.4  632.97  5579.5  637.34  5585.8  637.09  5600.4   639.3  5608.2  639.05
#Mann= 3 ,-1 , 0
  4349.1     .05       0  4820.5    .033       0  5335.9     .05       0
Bank Sta=4820.5,5335.9
XS Rating Curve= 0 ,0
Exp/Cntr=0.3,0.1

Type RM Length L Ch R = 1 ,27502   ,362,362,362
BEGIN DESCRIPTION:
Kirkwood Branch 55.0
END DESCRIPTION:
XS GIS Cut Line= 3
      2372590.61      7038921.04      2373128.81      7038496.58
      2373522.72      7038108.22
#Sta/Elev= 30
  4394.8   648.2  4408.2  646.71  4422.6  647.46  4429.1  647.06  4451.5  645.37
  4486.8  644.43  4501.2  643.15  4536.5  641.47    4622  634.79    4656  633.38
    4793  625.94  4807.5  624.37  4836.3  623.27  4850.8   622.7  5203.5  621.77
  5254.7  622.77  5367.9  631.26  5403.3  634.81  5410.3  635.08  5417.4  637.32
  5424.4  637.14  5431.6  638.52  5438.6  638.75  5445.6  639.91    5488   642.3
  5558.7  648.08    5580  650.87  5601.2  652.55  5628.6  656.61  5633.4  656.61
#Mann= 5 ,-1 , 0
  4394.8     .05       0  4429.1     .12       0    4656     .05       0
  4836.3    .033       0  5254.7     .05       0
Bank Sta=4836.3,5254.7
XS Rating Curve= 0 ,0
Exp/Cntr=0.3,0.1

Type RM Length L Ch R = 1 ,27140   ,59,59,59
BEGIN DESCRIPTION:
Kirkwood Branch 54.2
END DESCRIPTION:
XS GIS Cut Line= 5
      2372665.54      7039079.15      2372981.78      7039065.27
      2373173.79      7038993.85      2373317.45      7038857.22
      2373569.88      7038158.17
#Sta/Elev= 30
  3999.5  644.69    4033  643.05    4082  639.36  4096.1  638.53  4147.2  633.58
  4173.1  632.27  4203.2   629.7  4243.2  625.75  4263.2  622.86  4980.2  621.94
  4983.8  621.94  4984.2  622.44  5000.7  624.26    5006  624.14  5036.7  626.47
    5062  627.32  5109.6  630.12  5148.7  634.77  5173.4  635.77  5184.7  637.67
  5258.4  642.34  5296.8   645.4  5302.1  646.35  5322.1   647.5  5332.9  649.14
  5383.5  651.92  5388.8  653.18  5444.8  658.52  5450.1  659.56  5462.4  659.89
#Mann= 5 ,-1 , 0
  3999.5     .05       0    4082     .12       0  4147.2     .05       0
  4263.2    .033       0  4984.2     .05       0
Bank Sta=4263.2,4984.2
XS Rating Curve= 0 ,0
Exp/Cntr=0.3,0.1

Type RM Length L Ch R = 1 ,27081   ,97,97,97
BEGIN DESCRIPTION:
Kirkwood Branch 54.1
END DESCRIPTION:
XS GIS Cut Line= 5
      2372707.11      7039120.76      2373023.39      7039106.89
       2373215.4      7039035.46      2373359.06      7038898.83
      2373611.51      7038199.73
#Sta/Elev= 30
  3999.6  641.79  4071.7  636.61    4111  633.06  4191.7  627.46  4324.6  629.29
  4349.6  624.78  4354.9  628.78  4435.3  624.71  4441.7  627.88  4471.6  626.89
  4490.6  623.23    4496  626.98  4518.2  618.75  4518.5  618.25  4522.5  618.75
  4534.6  619.65  4541.5  625.01  4569.8  627.19  4711.3  627.23  4728.6  626.44
  4733.9  621.25    4790  627.87  4907.3  627.32  4930.7   622.2  4968.7  627.45
  4999.3  621.24  5024.7   621.6  5060.7  629.23  5281.6  641.55  5462.6  661.27
#Mann= 7 ,-1 , 0
  3999.6     .05       0  4071.7     .12       0    4111     .05       0
  4441.7     .12       0  4471.6     .05       0  4518.2    .033       0
  4522.5     .05       0
Bank Sta=4518.2,4522.5
XS Rating Curve= 0 ,0
Exp/Cntr=0.3,0.1

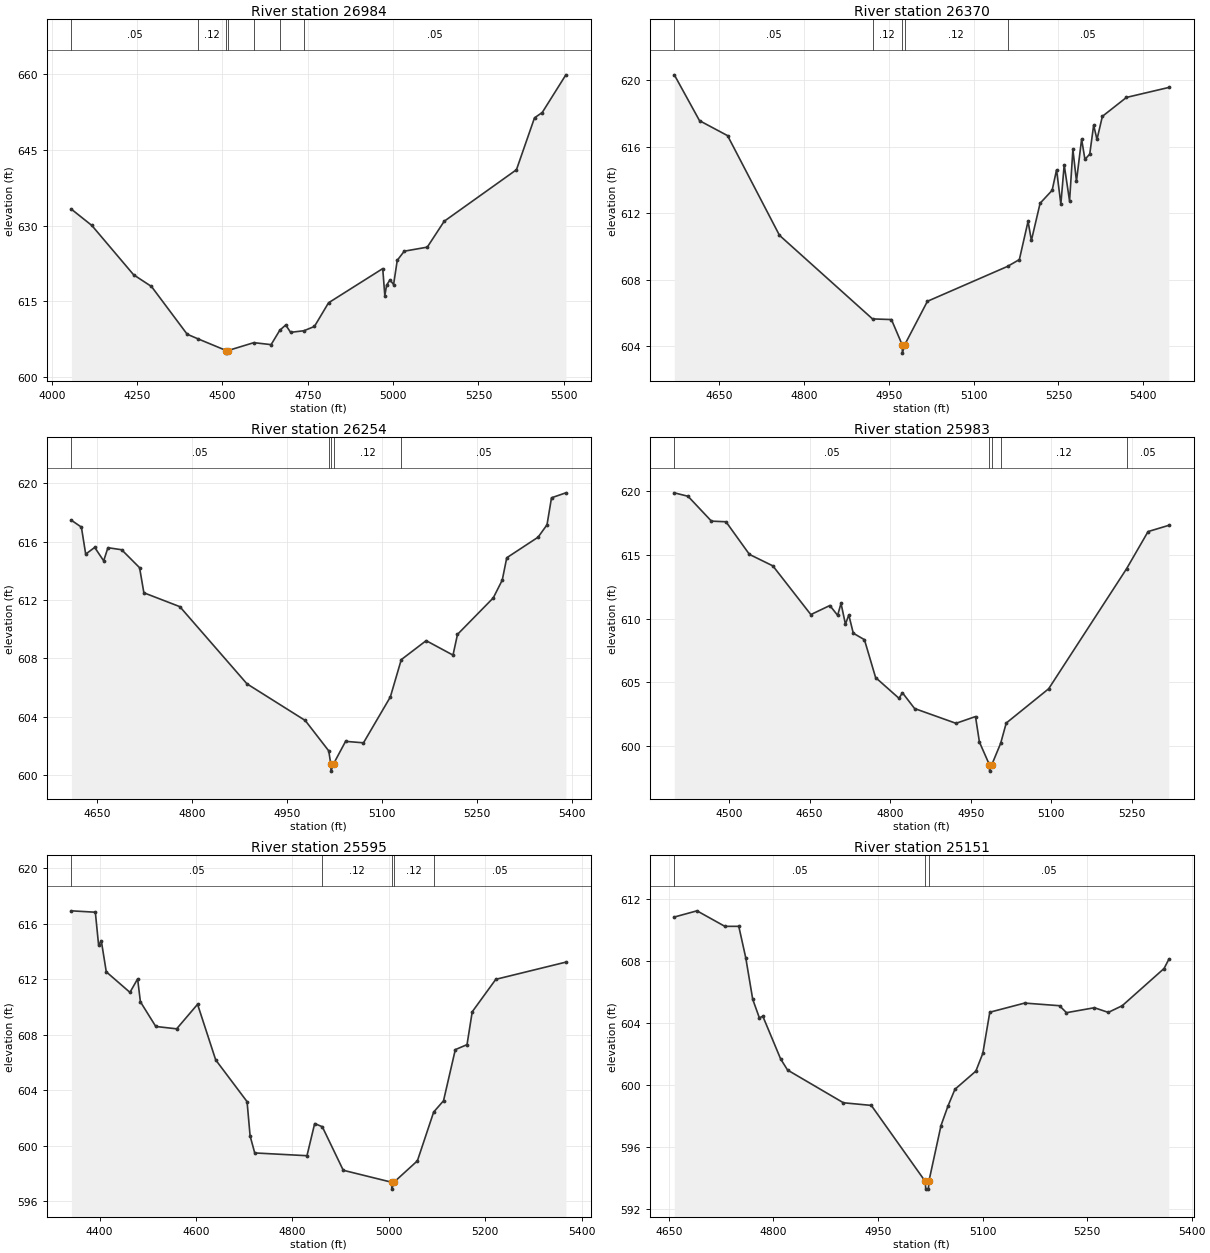
Type RM Length L Ch R = 1 ,26984   ,614,614,614
BEGIN DESCRIPTION:
Kirkwood Branch 54.0
END DESCRIPTION:
XS GIS Cut Line= 4
      2372798.71      7039278.87      2373254.24      7039079.85
      2373414.54      7038943.21      2373658.03      7038243.19
#Sta/Elev= 30
  4057.4  633.23  4117.4  630.01  4239.8  620.26  4292.1  617.95  4396.6  608.52
  4429.2  607.58  4511.5  605.28  4511.8  604.78  4515.8  605.28    4592  606.85
  4642.6  606.46    4668   609.3  4685.4  610.34  4699.7  608.89  4738.5   609.2
  4769.5  610.05  4810.9  614.73  4969.7  621.49  4975.8  616.13  4981.1  618.22
  4990.9  619.26  5001.5  618.33  5012.2  623.12  5032.7  624.93  5100.2  625.73
  5149.7  630.84  5361.5  641.03  5414.4  651.29    5437  652.34  5506.3  659.79
#Mann= 7 ,-1 , 0
  4057.4     .05       0  4429.2     .12       0  4511.5    .033       0
  4515.8     .12       0    4592     .05       0    4668     .12       0
  4738.5     .05       0
Bank Sta=4511.5,4515.8
XS Rating Curve= 0 ,0
Exp/Cntr=0.3,0.1

Type RM Length L Ch R = 1 ,26370   ,116,116,116
BEGIN DESCRIPTION:
Kirkwood Branch 53.3
END DESCRIPTION:
XS GIS Cut Line= 3
      2373023.37      7039517.47      2373447.83      7039087.47
      2373678.12      7038945.96
#Sta/Elev= 30
  4570.6  620.34  4615.2  617.58  4664.8  616.68  4756.6  610.68  4921.1  605.65
  4954.6  605.61  4973.6  604.09    4974  603.59    4978  604.09  5018.2  606.71
  5159.9  608.81  5180.8  609.22  5196.2  611.52  5202.1  610.37  5217.5  612.61
  5238.8  613.39  5246.6  614.62  5254.2  612.56  5260.1  614.92  5269.6  612.75
  5275.5  615.85  5281.8  613.94  5290.9  616.47  5296.8  615.25  5305.3  615.57
  5312.2  617.31  5318.1  616.45  5327.6  617.84  5370.2  618.98  5445.1  619.58
#Mann= 5 ,-1 , 0
  4570.6     .05       0  4921.1     .12       0  4973.6     .07       0
    4978     .12       0  5159.9     .05       0
Bank Sta=4973.6,4978
XS Rating Curve= 0 ,0
Exp/Cntr=0.3,0.1

Type RM Length L Ch R = 1 ,26254   ,271,271,271
BEGIN DESCRIPTION:
Kirkwood Branch 53.0
END DESCRIPTION:
XS GIS Cut Line= 3
      2373078.87      7039611.77        2373323.      7039342.69
      2373617.02      7039045.89
#Sta/Elev= 30
  4609.5  617.47  4625.3     617  4632.1  615.15  4646.3  615.61  4660.5  614.69
  4667.2  615.59  4688.9  615.45  4717.2  614.22    4724   612.5  4780.8  611.55
  4886.9  606.26  4978.9  603.75    5016  601.67  5019.2  600.78  5019.6  600.28
  5023.6  600.78  5042.6  602.32  5070.9  602.22  5113.3  605.36  5130.6  607.92
  5169.9  609.22  5212.3  608.23  5219.4  609.65  5275.9  612.15  5290.1  613.37
  5297.2   614.9  5346.7  616.31  5360.8  617.16  5367.9  619.01  5390.6  619.35
#Mann= 5 ,-1 , 0
  4609.5     .05       0    5016     .12       0  5019.2    .033       0
  5023.6     .12       0  5130.6     .05       0
Bank Sta=5019.2,5023.6
XS Rating Curve= 0 ,0
Exp/Cntr=0.3,0.1

Type RM Length L Ch R = 1 ,25983   ,388,388,388
BEGIN DESCRIPTION:
Kirkwood Branch 52.0
END DESCRIPTION:
XS GIS Cut Line= 3
      2373042.79      7039869.78      2373403.45      7039595.13
      2373775.33      7039312.03
#Sta/Elev= 30
  4398.2  619.87  4423.7   619.6  4467.3  617.65  4494.4   617.6  4538.1  615.04
  4581.7  614.14  4652.4  610.32  4687.8  611.03  4702.3  610.26  4708.6   611.2
  4716.8  609.57  4723.1  610.29  4731.4  608.86  4752.2  608.35    4773  605.38
  4816.6  603.75  4822.9  604.19  4845.6  602.95  4922.7  601.79    4959  602.32
  4966.3  600.32  4984.9  598.54  4985.3  598.04  4989.3  598.54  5005.9  600.23
  5016.2  601.81  5095.2   604.5  5240.2  613.91  5280.3  616.83  5318.9  617.32
#Mann= 5 ,-1 , 0
  4398.2     .05       0  4984.9    .033       0  4989.3     .05       0
  5005.9     .12       0  5240.2     .05       0
Bank Sta=4984.9,4989.3
XS Rating Curve= 0 ,0
Exp/Cntr=0.3,0.1

Type RM Length L Ch R = 1 ,25595   ,444,444,444
BEGIN DESCRIPTION:
Kirkwood Branch 51.0
END DESCRIPTION:
XS GIS Cut Line= 3
      2373475.88      7040303.32      2373815.78      7039697.75
       2373936.9       7039389.1
#Sta/Elev= 30
  4341.3  616.94    4391  616.84  4397.7  614.49  4403.5  614.75  4413.7  612.54
  4462.8  611.06  4478.7  612.03  4484.5  610.38  4516.4   608.6  4559.7  608.43
  4603.1   610.2  4640.7  606.19  4705.8  603.18  4712.1  600.71  4721.7  599.48
  4830.1  599.28  4846.1   601.6  4861.9  601.37  4905.4  598.23  5005.5  597.37
  5006.2  596.87  5010.6  597.37  5059.2  598.91    5093  602.43  5113.4  603.24
  5137.9  606.93  5162.2  607.29    5173  609.66  5221.9     612  5367.3  613.24
#Mann= 5 ,-1 , 0
  4341.3     .05       0  4861.9     .12       0  5005.5     .07       0
  5010.6     .12       0    5093     .05       0
Bank Sta=5005.5,5010.6
XS Rating Curve= 0 ,0
Exp/Cntr=0.3,0.1

Type RM Length L Ch R = 1 ,25151   ,423,423,423
BEGIN DESCRIPTION:
Kirkwood Branch 50.0
END DESCRIPTION:
XS GIS Cut Line= 3
      2374186.93       7040252.5        2374179.        7039910.
      2374175.22      7039543.21
#Sta/Elev= 30
  4657.8  610.85  4690.3  611.25  4730.3  610.25  4750.3  610.25  4760.3  608.22
  4770.3  605.54  4779.8  604.35  4784.8  604.45  4810.3   601.7  4820.3  600.98
  4900.4  598.87  4940.4   598.7  5017.8   593.8  5018.5   593.3  5022.3   593.3
    5023   593.8  5040.4   597.4  5050.4  598.66  5060.4  599.74  5090.4  600.91
  5100.4  602.06  5110.4  604.71  5160.4   605.3  5210.4  605.13  5220.4  604.68
  5260.4     605  5280.4   604.7  5300.4  605.13  5360.4  607.53  5367.2  608.12
#Mann= 3 ,-1 , 0
  4657.8     .05       0  5017.8    .033       0    5023     .05       0
Bank Sta=5017.8,5023
XS Rating Curve= 0 ,0
Exp/Cntr=0.3,0.1

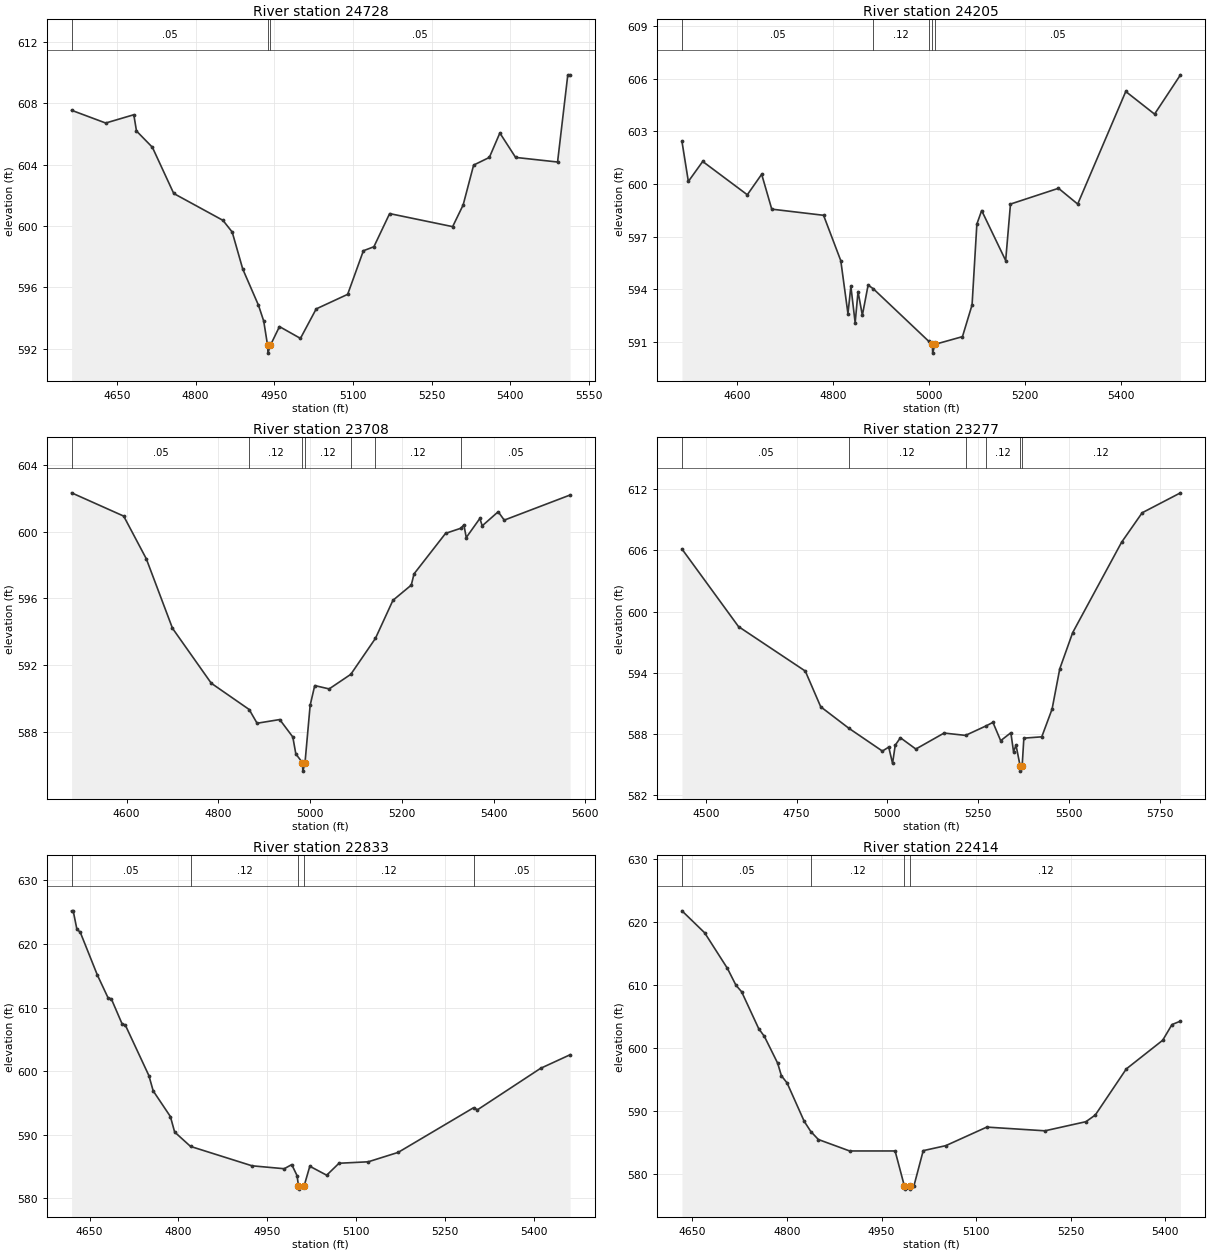
Type RM Length L Ch R = 1 ,24728   ,523,523,523
BEGIN DESCRIPTION:
Kirkwood Branch 49.0
END DESCRIPTION:
XS GIS Cut Line= 3
      2374522.91      7040291.59       2374573.7       7040010.3
      2374558.08      7039346.13
#Sta/Elev= 30
  4563.6  607.54  4628.6  606.71  4682.2  607.25  4687.3  606.19  4717.6  605.13
  4758.3  602.12  4852.1  600.37  4869.7  599.61  4889.8   597.2  4919.8  594.84
  4929.8  593.81  4937.2  592.22  4937.9  591.72  4942.4  592.22  4959.8  593.45
  4999.8  592.68  5029.8   594.6  5089.8  595.55  5119.8  598.39  5139.8  598.65
  5169.8  600.81  5289.9  599.96  5309.9  601.37  5329.9  603.97  5359.9  604.47
  5379.9  606.06  5409.9  604.47  5489.9  604.17  5509.4  609.85  5513.8  609.85
#Mann= 3 ,-1 , 0
  4563.6     .05       0  4937.2    .033       0  4942.4     .05       0
Bank Sta=4937.2,4942.4
XS Rating Curve= 0 ,0
Exp/Cntr=0.3,0.1

Type RM Length L Ch R = 1 ,24205   ,497,497,497
BEGIN DESCRIPTION:
Kirkwood Branch 48.0
END DESCRIPTION:
XS GIS Cut Line= 3
      2374819.85      7040400.96      2375058.15      7040049.37
      2375073.78      7039436.01
#Sta/Elev= 30
  4485.9  602.42  4499.2  600.14  4529.1  601.28    4622  599.38  4651.9  600.55
  4672.9  598.56  4780.8  598.21  4816.7  595.62  4831.6   592.6  4837.7  594.16
  4846.6  592.08  4852.6  593.86  4861.6  592.51  4873.6  594.23  4884.4  594.02
  4999.7  591.03  5007.3  590.85  5008.1  590.35  5012.7  590.85  5070.1  591.29
  5090.1   593.1  5100.1  597.71  5110.1  598.48  5160.1  595.63  5170.1  598.85
  5270.1  599.75  5310.1  598.85  5410.2  605.27  5470.2  603.98  5524.2  606.22
#Mann= 5 ,-1 , 0
  4485.9     .05       0  4884.4     .12       0  4999.7     .05       0
  5007.3    .033       0  5012.7     .05       0
Bank Sta=5007.3,5012.7
XS Rating Curve= 0 ,0
Exp/Cntr=0.3,0.1

Type RM Length L Ch R = 1 ,23708   ,431,431,431
BEGIN DESCRIPTION:
Kirkwood Branch 47.0
END DESCRIPTION:
XS GIS Cut Line= 4
      2375179.02      7040509.97      2375503.53      7040131.41
      2375506.71      7040072.56      2375644.09      7039561.34
#Sta/Elev= 30
  4479.9  602.31  4593.5  600.92  4642.8  598.37  4699.9  594.22  4784.4  590.94
  4867.1  589.37  4884.3  588.55  4933.7  588.77  4962.2  587.73  4968.8  586.72
  4983.3  586.19  4984.1  585.69  4988.8  586.19    5000  589.62    5010   590.8
  5041.4   590.6  5088.6  591.47  5142.4  593.62  5180.5  595.89  5220.5   596.8
  5226.5  597.47  5295.3  599.89  5328.1  600.19  5335.2  600.39  5340.4  599.64
    5370  600.78  5375.2  600.34    5410  601.18  5423.2  600.68  5566.8  602.18
#Mann= 7 ,-1 , 0
  4479.9     .05       0  4867.1     .12       0  4983.3     .07       0
  4988.8     .12       0  5088.6     .05       0  5142.4     .12       0
  5328.1     .05       0
Bank Sta=4983.3,4988.8
XS Rating Curve= 0 ,0
Exp/Cntr=0.3,0.1

Type RM Length L Ch R = 1 ,23277   ,444,444,444
BEGIN DESCRIPTION:
Kirkwood Branch 46.0
END DESCRIPTION:
XS GIS Cut Line= 3
      2375378.98      7040810.02        2375779.        7040410.
      2376374.35      7039866.11
#Sta/Elev= 30
  4434.5  606.14  4590.1  598.52  4773.9  594.15  4816.4  590.64  4893.5  588.54
  4986.1  586.29  5003.6  586.68  5014.1  585.08  5021.5  586.87  5035.7   587.6
  5078.2  586.49  5155.9  588.06  5214.9  587.83  5272.5  588.78  5290.4  589.11
  5311.7  587.31  5339.7  588.09  5347.1  586.23  5353.9  586.87  5365.3  584.82
  5366.1  584.32  5370.8  584.82  5375.5  587.56  5424.8  587.69  5453.2  590.42
  5474.3  594.37  5509.9  597.93  5644.4   606.8  5701.1   609.7  5806.6  611.66
#Mann= 6 ,-1 , 0
  4434.5     .05       0  4893.5     .12       0  5214.9     .05       0
  5272.5     .12       0  5365.3     .07       0  5370.8     .12       0
Bank Sta=5365.3,5370.8
XS Rating Curve= 0 ,0
Exp/Cntr=0.3,0.1

Type RM Length L Ch R = 1 ,22833   ,419,419,419
BEGIN DESCRIPTION:
Kirkwood Branch 45.0
END DESCRIPTION:
XS GIS Cut Line= 3
      2375979.02      7041009.96        2376129.        7040660.
      2376428.98      7040310.02
#Sta/Elev= 30
  4619.5  625.21  4622.2  625.21  4628.5  622.29    4634  621.87    4663  615.11
  4681.1  611.52  4686.6  611.36  4704.7  607.44  4710.1  607.26    4750  599.29
  4757.3  596.88  4786.3  592.85  4793.5  590.41  4820.3  588.15  4924.1   585.1
  4978.5  584.64  4991.2  585.29  5000.2  583.55  5002.6  581.93    5004  581.43
  5012.1  581.93  5021.7  585.03  5050.2  583.62    5071   585.5  5120.4  585.73
  5170.9  587.21  5298.1  594.23  5304.8  593.91  5411.3  600.43  5461.2  602.57
#Mann= 5 ,-1 , 0
  4619.5     .05       0  4820.3     .12       0  5002.6     .05       0
  5012.1     .12       0  5298.1     .05       0
Bank Sta=5002.6,5012.1
XS Rating Curve= 0 ,0
Exp/Cntr=0.3,0.1

Type RM Length L Ch R = 1 ,22414   ,373,373,373
BEGIN DESCRIPTION:
Kirkwood Branch 44.0
END DESCRIPTION:
XS GIS Cut Line= 3
      2376179.02      7041059.98        2376479.        7040860.
      2376828.96      7040610.03
#Sta/Elev= 30
  4633.5  621.74  4669.5  618.25  4705.6   612.6  4719.1  609.93  4728.1  608.89
  4755.2  603.03  4764.2   601.8  4785.2  597.56  4791.2  595.55  4800.2  594.41
  4827.3  588.33  4837.8   586.7  4849.8  585.43  4899.4  583.61  4971.5  583.61
  4986.2  578.05  4987.5  577.55  4994.5  577.55  4995.9  578.05  5001.4  578.08
  5016.1  583.66  5051.8  584.45  5116.9   587.4  5209.1  586.81  5274.2  588.26
    5289  589.32  5338.1  596.63  5395.9  601.19  5410.6  603.68  5424.1  604.23
#Mann= 4 ,-1 , 0
  4633.5     .05       0  4837.8     .12       0  4986.2     .05       0
  4995.9     .12       0
Bank Sta=4986.2,4995.9
XS Rating Curve= 0 ,0
Exp/Cntr=0.3,0.1