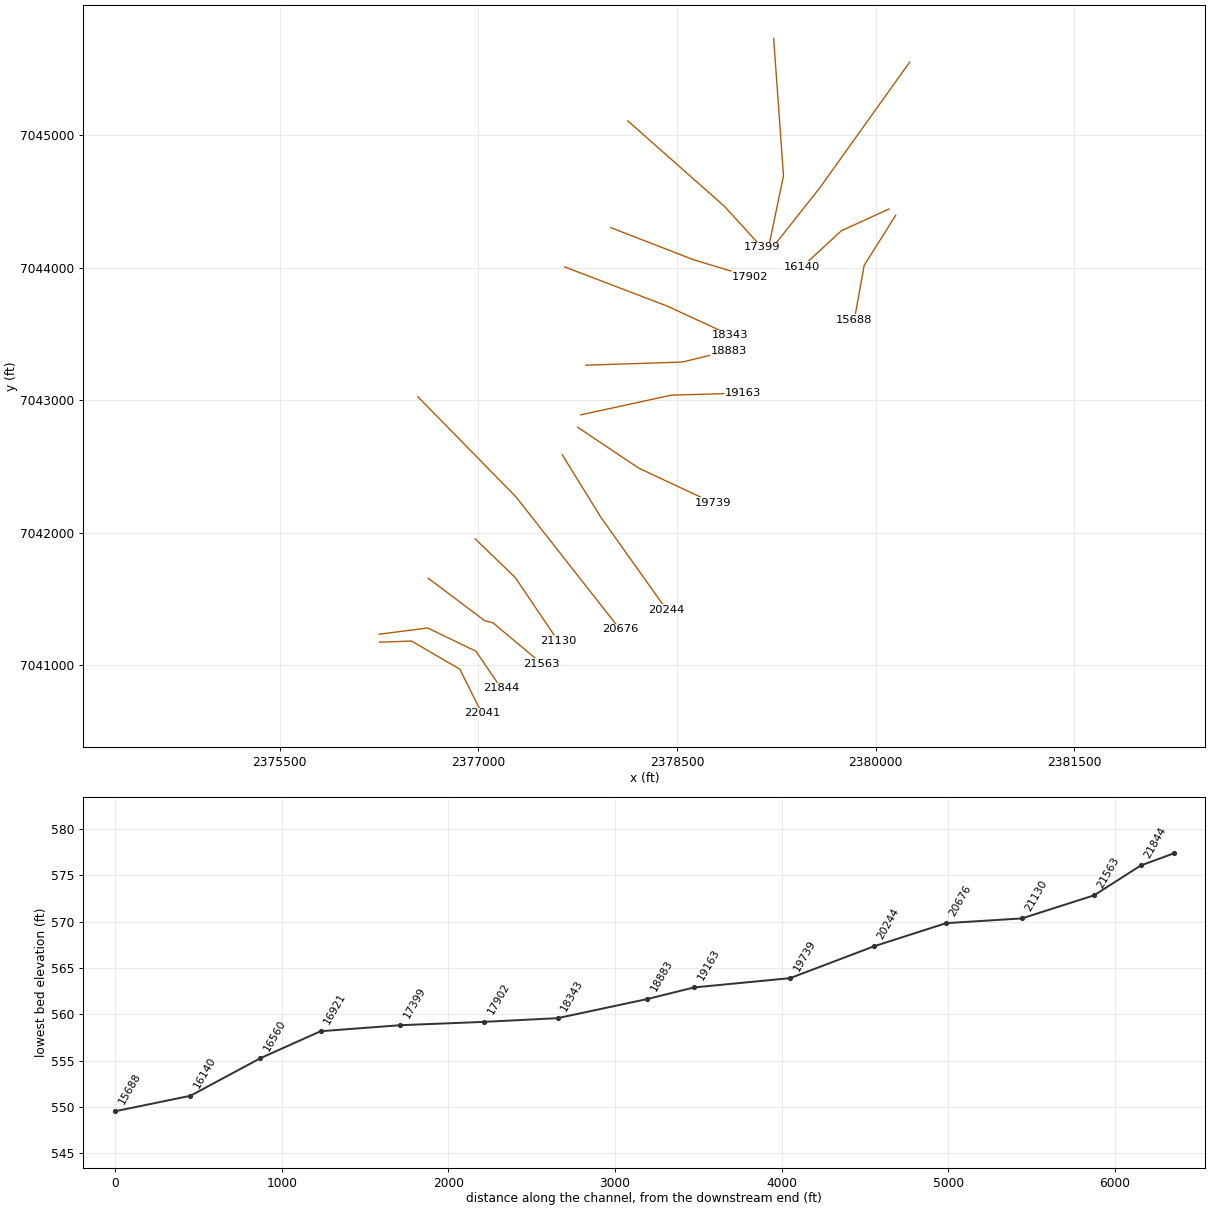
HEC-RAS study Kirkwood Branch.prj: Kirkwood Branch Base Level Engineering

--- Kirkwood Branch.g01 (geometry) --- (continued)

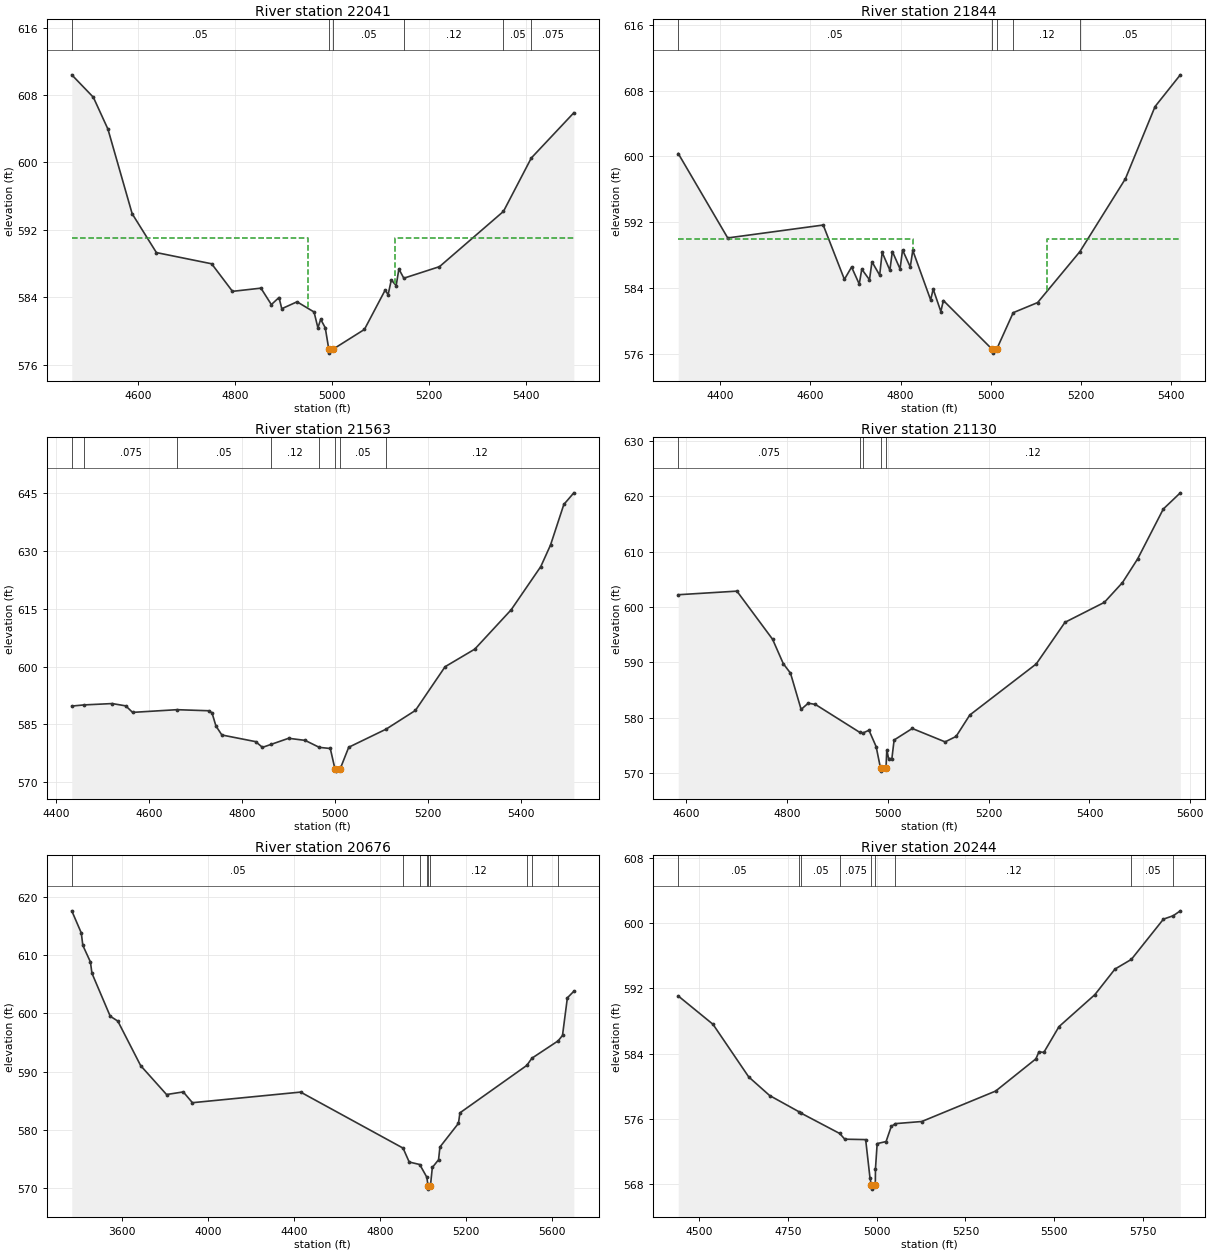
Type RM Length L Ch R = 1 ,22041   ,197,197,197
BEGIN DESCRIPTION:
Kirkwood Branch 43.0
END DESCRIPTION:
XS GIS Cut Line= 4
       2376254.5      7041172.03      2376494.79      7041180.61
      2376859.57      7040968.18      2377026.52      7040634.27
#Sta/Elev= 30
  4463.5   610.4    4508  607.74  4538.1  603.96  4588.1  593.92  4638.1  589.31
  4752.1  587.98  4795.1  584.71  4853.8  585.09  4875.3  583.14  4891.1  583.98
  4896.8  582.65  4928.3  583.47  4963.4  582.26  4971.3  580.39  4977.1  581.39
  4986.5  580.39  4993.7  577.88  4995.1  577.38  5003.5  577.88  5067.3  580.19
  5110.3  584.88  5116.1  584.29  5122.8  586.07  5132.8  585.39  5138.4  587.36
  5148.6  586.27  5222.2  587.64  5354.2   594.2  5411.6  600.53  5499.4   605.9
#Mann= 6 ,-1 , 0
  4463.5     .05       0  4993.7    .033       0  5003.5     .05       0
  5148.6     .12       0  5354.2     .05       0  5411.6    .075       0
#XS Ineff= 2 , 0
       0    4950     591    5130       0     591
Permanent Ineff=
       F       F
Bank Sta=4993.7,5003.5
XS Rating Curve= 0 ,0
Exp/Cntr=0.3,0.1

Type RM Length L Ch R = 1 ,21844   ,281,281,281
BEGIN DESCRIPTION:
Kirkwood Branch 42.8
END DESCRIPTION:
XS GIS Cut Line= 4
      2376250.19      7041232.11       2376617.1      7041279.32
      2376981.88      7041103.37      2377171.92      7040823.64
#Sta/Elev= 30
    4307  600.36  4416.7  590.09  4628.4  591.66  4675.4  585.05  4691.3  586.55
  4708.3  584.48  4713.9  586.29    4731     585  4736.5  587.19  4753.6  585.56
  4759.1  588.34  4776.2  586.16  4781.7  588.44  4798.8  586.32  4804.3  588.63
  4821.4  586.56    4827  588.57  4866.6  582.55  4872.2  583.87  4889.2  581.14
  4894.8  582.48  5002.4  576.58  5003.9  576.08  5013.2  576.58  5049.6     581
  5103.8  582.23  5197.5  588.43  5298.4  597.29  5364.1  606.07  5420.1  609.93
#Mann= 5 ,-1 , 0
    4307     .05       0  5002.4     .05       0  5013.2     .05       0
  5049.6     .12       0  5197.5     .05       0
#XS Ineff= 2 , 0
       0    4827     590    5125       0     590
Permanent Ineff=
       F       F
Bank Sta=5002.4,5013.2
XS Rating Curve= 0 ,0
Exp/Cntr=0.3,0.1

Type RM Length L Ch R = 1 ,21563   ,433,433,433
BEGIN DESCRIPTION:
Kirkwood Branch 42.0
END DESCRIPTION:
XS GIS Cut Line= 4
       2376621.4      7041654.82      2377046.25      7041335.11
      2377110.62      7041317.94      2377479.03      7041009.98
#Sta/Elev= 30
  4434.1  589.75  4460.4  590.05    4521   590.4  4550.1   589.8  4564.7  588.11
    4660  588.81  4729.2  588.53  4735.4  587.97  4743.8  584.57  4756.5  582.24
  4829.1  580.51  4843.7  579.02  4862.8  579.82  4899.9  581.38  4935.3  580.84
  4965.9  579.02  4989.4  578.73  4999.6  573.35  5001.1  572.85  5010.4  573.35
    5029  579.05  5109.4  583.76  5172.3  588.62    5236  599.97  5299.8  604.54
  5377.9  614.75  5441.6  625.99  5462.5  631.58  5491.1  642.12  5512.6  645.14
#Mann= 8 ,-1 , 0
  4434.1     .12       0  4460.4    .075       0    4660     .05       0
  4862.8     .12       0  4965.9     .05       0  4999.6    .033       0
  5010.4     .05       0  5109.4     .12       0
Bank Sta=4999.6,5010.4
XS Rating Curve= 0 ,0
Exp/Cntr=0.3,0.1

Type RM Length L Ch R = 1 ,21130   ,454,454,454
BEGIN DESCRIPTION:
Kirkwood Branch 41.0
END DESCRIPTION:
XS GIS Cut Line= 3
      2376976.44      7041951.96        2377279.        7041660.
      2377600.61      7041183.66
#Sta/Elev= 30
  4584.9  602.21  4701.2  602.86  4771.9  594.17  4793.2  589.75  4807.4  588.05
  4828.5   581.5  4842.6  582.63  4856.8   582.4  4944.5  577.37  4951.5  577.27
    4963  577.74  4977.2  574.78  4985.9  570.86  4987.4  570.36  4996.7  570.86
  4998.3  574.16  5001.9  572.63  5008.4  572.63  5012.8  575.98  5048.8  578.06
  5113.9  575.64  5135.7  576.63  5162.8  580.49  5294.6  589.72  5351.5  597.23
  5429.5  600.83  5465.5  604.41  5495.4  608.66  5546.4  617.69  5580.1  620.61
#Mann= 5 ,-1 , 0
  4584.9    .075       0  4944.5     .05       0  4951.5     .12       0
  4985.9     .07       0  4996.7     .12       0
Bank Sta=4985.9,4996.7
XS Rating Curve= 0 ,0
Exp/Cntr=0.3,0.1

Type RM Length L Ch R = 1 ,20676   ,432,432,432
BEGIN DESCRIPTION:
Kirkwood Branch 40.0
END DESCRIPTION:
XS GIS Cut Line= 3
      2376542.77      7043026.35      2377285.04      7042268.45
      2378070.29      7041268.33
#Sta/Elev= 30
  3367.4  617.57  3411.7  613.77  3418.7  611.65  3454.1   608.8  3461.1  606.87
    3546   599.5  3581.4  598.66  3687.4  591.03  3807.7  586.07  3885.4  586.52
  3927.9  584.67  4430.4  586.49  4906.5  576.88  4934.9   574.5  4983.9  574.07
    5017  571.88  5022.5  570.35    5024  569.85  5033.4  570.35  5042.4  573.56
  5071.3  574.89  5077.7  577.07  5163.7  581.13  5170.7  582.93  5481.1  591.06
    5505   592.3    5627  595.28  5647.1  596.21  5669.7  602.65  5699.8  603.78
#Mann= 9 ,-1 , 0
  3367.4     .05       0  4906.5     .12       0  4983.9     .05       0
    5017     .12       0  5022.5    .033       0  5033.4     .12       0
  5481.1     .05       0    5505     .12       0    5627     .05       0
Bank Sta=5022.5,5033.4
XS Rating Curve= 0 ,0
Exp/Cntr=0.3,0.1

Type RM Length L Ch R = 1 ,20244   ,505,505,505
BEGIN DESCRIPTION:
Kirkwood Branch 39.0
END DESCRIPTION:
XS GIS Cut Line= 3
      2377632.77      7042588.77        2377929.        7042110.
      2378421.91      7041416.79
#Sta/Elev= 30
  4441.4  591.07  4539.3  587.59  4639.9  581.13  4698.7  578.85  4780.8  576.87
  4787.1  576.69    4896  574.19  4910.3  573.49  4969.1  573.44  4981.3  568.73
  4985.3  567.86  4986.8  567.36  4996.3  567.86  4996.7  569.85  5001.5  572.95
  5026.6   573.2  5041.2  575.06    5053   575.4  5127.1  575.66  5335.2   579.4
  5448.4  583.35    5457  584.22  5470.7  584.14  5513.5  587.31  5614.4  591.23
    5671  594.37  5717.2  595.56  5807.5   600.5  5835.2  600.92    5855  601.52
#Mann= 9 ,-1 , 0
  4441.4     .05       0  4780.8    .075       0  4787.1     .05       0
    4896    .075       0  4985.3     .07       0  4996.3    .075       0
    5053     .12       0  5717.2     .05       0  5835.2    .075       0
Bank Sta=4985.3,4996.3
XS Rating Curve= 0 ,0
Exp/Cntr=0.3,0.1

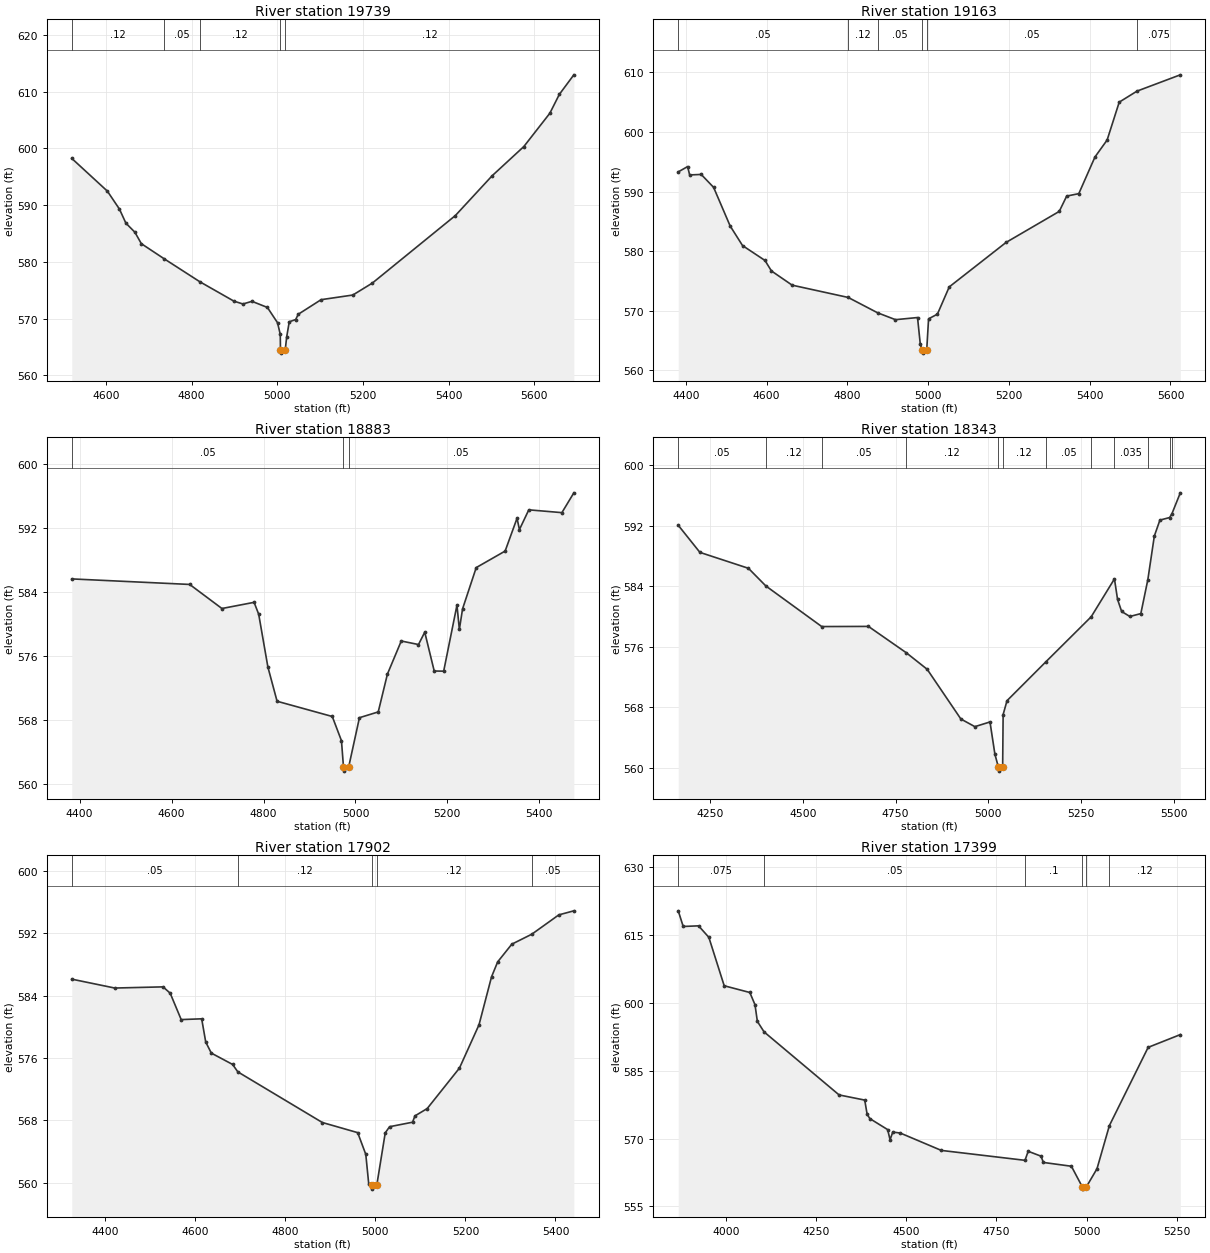
Type RM Length L Ch R = 1 ,19739   ,576,576,576
BEGIN DESCRIPTION:
Kirkwood Branch 38.0
END DESCRIPTION:
XS GIS Cut Line= 3
      2377749.93      7042795.89      2378210.96      7042487.23
      2378769.67      7042225.46
#Sta/Elev= 30
  4520.3  598.23  4603.4  592.46  4631.6  589.29  4646.6  586.82  4667.6  585.22
  4682.7   583.2  4735.3  580.57  4819.2  576.49  4898.8  573.07  4919.8  572.57
  4940.9  573.04  4976.9  571.96  5000.5  569.27  5006.9  567.23  5007.4  564.41
  5008.9  563.91  5018.4  564.41  5021.9  566.77  5027.9  569.43  5042.9  569.83
  5048.9  570.76  5102.2  573.33  5176.3  574.15  5221.9  576.26  5415.6  588.16
  5501.4  595.17  5575.4  600.32  5636.1  606.19  5658.2  609.51  5692.1  612.96
#Mann= 5 ,-1 , 0
  4520.3     .12       0  4735.3     .05       0  4819.2     .12       0
  5007.4     .07       0  5018.4     .12       0
Bank Sta=5007.4,5018.4
XS Rating Curve= 0 ,0
Exp/Cntr=0.3,0.1

Type RM Length L Ch R = 1 ,19163   ,280,280,280
BEGIN DESCRIPTION:
Kirkwood Branch 37.0
END DESCRIPTION:
XS GIS Cut Line= 3
      2377773.42      7042889.64      2378457.09      7043038.09
      2379000.16      7043053.72
#Sta/Elev= 30
  4381.5  593.31  4404.7   594.2  4409.8   592.8  4438.4  592.88  4469.1  590.71
    4510  584.24  4540.7  580.95  4596.1  578.46  4612.3  576.69  4663.5  574.31
  4802.2  572.25  4875.2  569.67  4919.3  568.52  4973.9  568.88  4980.7  564.41
  4985.4  563.41  4986.9  562.91  4996.6  563.41  5001.2  568.66  5023.1  569.45
  5052.4  574.02  5193.1  581.48  5324.7  586.68  5343.1  589.25  5373.1  589.66
  5413.1  595.81  5443.2  598.65  5473.2  605.01  5517.3  606.86  5624.4  609.59
#Mann= 6 ,-1 , 0
  4381.5     .05       0  4802.2     .12       0  4875.2     .05       0
  4985.4     .05       0  4996.6     .05       0  5517.3    .075       0
Bank Sta=4985.4,4996.6
XS Rating Curve= 0 ,0
Exp/Cntr=0.3,0.1

Type RM Length L Ch R = 1 ,18883   ,540,540,540
BEGIN DESCRIPTION:
Kirkwood Branch 36.0
END DESCRIPTION:
XS GIS Cut Line= 3
      2377812.51      7043264.69      2378539.14      7043288.13
       2378894.3      7043373.99
#Sta/Elev= 30
  4382.8  585.62  4639.4  584.93  4709.5  581.93  4779.5   582.7  4789.5  581.22
  4809.5  574.64  4829.5  570.37  4949.6  568.47  4969.6  565.45    4974  562.16
  4975.6  561.66  4985.2  562.16  5008.7  568.32  5049.6  569.04  5069.6  573.76
  5099.7  577.88  5137.2  577.44  5150.8  578.98  5171.4  574.14    5192  574.12
  5220.9  582.35  5226.1  579.32  5233.1  581.89  5262.8  587.03  5325.7  589.09
  5351.6  593.18  5356.8  591.77  5377.2  594.23  5449.2  593.88  5475.2  596.35
#Mann= 3 ,-1 , 0
  4382.8     .05       0    4974     .05       0  4985.2     .05       0
Bank Sta=4974,4985.2
XS Rating Curve= 0 ,0
Exp/Cntr=0.3,0.1

Type RM Length L Ch R = 1 ,18343   ,441,441,441
BEGIN DESCRIPTION:
Kirkwood Branch 35.0
END DESCRIPTION:
XS GIS Cut Line= 3
      2377652.32      7044006.97        2378429.        7043710.
      2378902.51      7043491.27
#Sta/Elev= 30
  4164.4  592.04  4222.8  588.46  4353.6  586.36  4400.5  584.03  4551.1  578.67
    4677  578.69  4778.8  575.22  4835.3  573.03  4926.1  566.47  4963.8  565.46
  5004.6  566.08  5017.9   561.8  5027.4  560.09    5029  559.59  5038.7  560.09
    5040  567.06  5050.5  568.89  5154.8     574  5277.3  579.96    5340  584.96
  5348.4  582.25  5359.4  580.66  5381.5     580  5411.1  580.38    5430  584.86
  5447.5  590.62  5462.5  592.72  5488.8  593.06  5494.9  593.56  5517.5  596.32
#Mann= 12 ,-1 , 0
  4164.4     .05       0  4400.5     .12       0  4551.1     .05       0
  4778.8     .12       0  5027.4     .07       0  5038.7     .12       0
  5154.8     .05       0  5277.3    .075       0    5340    .035       0
    5430     .05       0  5488.8    .075       0  5494.9     .05       0
Bank Sta=5027.4,5038.7
XS Rating Curve= 0 ,0
Exp/Cntr=0.3,0.1

Type RM Length L Ch R = 1 ,17902   ,503,503,503
BEGIN DESCRIPTION:
Kirkwood Branch 34.0
END DESCRIPTION:
XS GIS Cut Line= 3
      2377999.96      7044303.92        2378629.        7044060.
      2379050.96      7043932.75
#Sta/Elev= 30
  4325.4  586.14  4420.9     585  4528.2  585.15    4544  584.34  4568.5  580.95
    4614  581.05    4623  578.07  4635.4  576.65  4682.8  575.19  4694.3  574.24
  4882.1  567.74  4960.6  566.44  4978.6  563.65  4985.1  559.87  4991.7  559.69
  4993.3  559.19    5003  559.69  5021.8  566.41  5031.4   567.2  5082.5  567.78
  5087.8  568.59    5115  569.53  5186.7  574.73  5230.1  580.28  5257.9  586.43
  5271.6  588.36    5303  590.63  5347.4  591.91  5407.4  594.39  5440.8  594.91
#Mann= 5 ,-1 , 0
  4325.4     .05       0  4694.3     .12       0  4991.7     .07       0
    5003     .12       0  5347.4     .05       0
Bank Sta=4991.7,5003
XS Rating Curve= 0 ,0
Exp/Cntr=0.3,0.1

Type RM Length L Ch R = 1 ,17399   ,478,478,478
BEGIN DESCRIPTION:
Kirkwood Branch 33.0
END DESCRIPTION:
XS GIS Cut Line= 3
      2378129.03      7045109.98       2378859.5      7044464.09
      2379140.81      7044155.42
#Sta/Elev= 30
  3867.4  620.37  3881.2  616.91  3923.8  617.05  3952.3  614.51  3994.9   603.8
    4066  602.31  4080.3  599.61  4086.9  595.92  4105.5   593.6  4313.6  579.66
  4384.7  578.52  4391.4  575.37    4399  574.42  4448.3  571.99    4455  569.74
  4462.5  571.45  4483.4  571.23  4597.2  567.39  4829.3   565.2  4838.1   567.2
  4873.6  566.12  4880.3  564.73    4958  563.89  4988.2  559.33  4989.7  558.83
  4999.5  559.33    5029  563.34  5063.4  572.89  5170.9  590.18  5260.1     593
#Mann= 6 ,-1 , 0
  3867.4    .075       0  4105.5     .05       0  4829.3      .1       0
  4988.2     .07       0  4999.5      .1       0  5063.4     .12       0
Bank Sta=4988.2,4999.5
XS Rating Curve= 0 ,0
Exp/Cntr=0.3,0.1

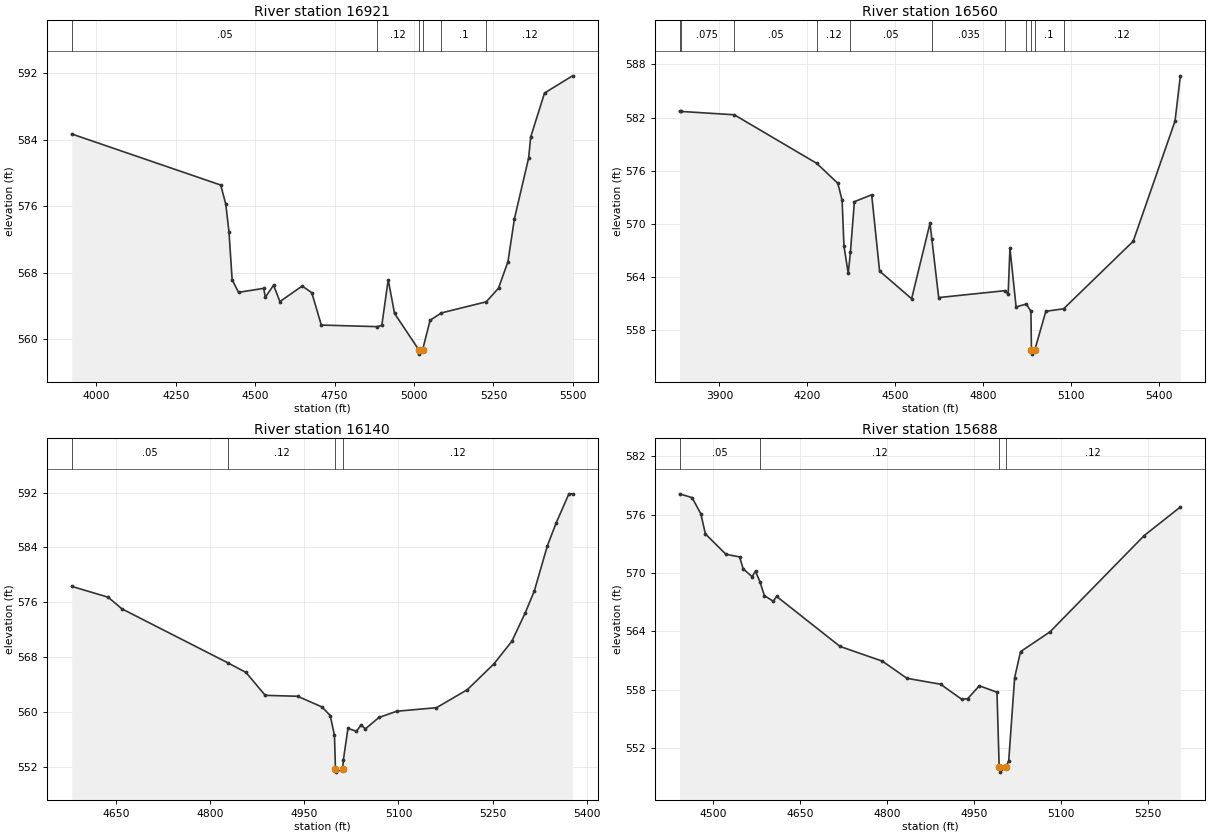
Type RM Length L Ch R = 1 ,16921   ,361,361,361
BEGIN DESCRIPTION:
Kirkwood Branch 32.0
END DESCRIPTION:
XS GIS Cut Line= 3
      2379230.64      7045733.84      2379304.87      7044694.59
      2379195.49       7044171.1
#Sta/Elev= 30
  3922.4  584.69  4391.5  578.54  4407.5  576.23  4417.5  572.91  4427.5  567.13
  4447.6  565.62  4526.9   566.1  4531.9  565.03  4557.9  566.48  4577.9  564.51
  4648.1  566.38  4678.2  565.58  4708.2  561.68  4883.4  561.49  4898.7  561.64
  4918.8  567.13  4938.8  563.08  5015.6  558.68  5017.2  558.18    5027  558.68
  5050.7  562.26  5086.1  563.14  5227.5  564.48  5266.1  566.12  5295.9  569.33
  5316.3   574.5    5361  581.81  5367.4  584.32    5411  589.62  5499.1  591.69
#Mann= 6 ,-1 , 0
  3922.4     .05       0  4883.4     .12       0  5015.6     .07       0
    5027     .12       0  5086.1      .1       0  5227.5     .12       0
Bank Sta=5015.6,5027
XS Rating Curve= 0 ,0
Exp/Cntr=0.3,0.1

Type RM Length L Ch R = 1 ,16560   ,420,420,420
BEGIN DESCRIPTION:
Kirkwood Branch 31.0
END DESCRIPTION:
XS GIS Cut Line= 3
      2380258.17      7045554.13      2379582.26      7044608.64
      2379243.21      7044179.95
#Sta/Elev= 30
  3764.1  582.69  3767.6  582.69  3950.8  582.31  4232.2  576.82  4304.1  574.57
  4318.8  572.63    4325  567.49  4339.7  564.38    4347  566.76  4360.6  572.49
  4419.6  573.27  4446.6  564.65  4555.9  561.53  4618.7  570.06    4625  568.25
  4648.2  561.66    4875  562.44  4885.3  562.03  4891.4  567.26  4912.4   560.6
  4947.2  560.93  4962.9  560.12  4964.8  555.77  4966.4  555.27  4976.3  555.77
  5013.9  560.11  5074.4  560.39  5311.9  568.02  5454.6  581.59  5472.9  586.71
#Mann= 11 ,-1 , 0
  3764.1     .05       0  3767.6    .075       0  3950.8     .05       0
  4232.2     .12       0    4347     .05       0    4625    .035       0
    4875     .12       0  4947.2      .1       0  4964.8     .07       0
  4976.3      .1       0  5074.4     .12       0
Bank Sta=4964.8,4976.3
XS Rating Curve= 0 ,0
Exp/Cntr=0.3,0.1

Type RM Length L Ch R = 1 ,16140   ,452,452,452
BEGIN DESCRIPTION:
Kirkwood Branch 30.0
END DESCRIPTION:
XS GIS Cut Line= 3
      2380101.88      7044444.56      2379742.44      7044280.47
      2379445.52      7044006.98
#Sta/Elev= 30
  4578.8  578.31  4636.9  576.73  4658.9  575.03  4827.5  567.17  4856.8  565.75
  4887.5  562.41  4939.1  562.28    4978  560.72  4991.1  559.47  4997.9  556.58
  4999.5  551.71  5001.1  551.21    5011  551.71  5012.1  552.98  5019.4  557.59
    5033  557.17  5040.4  558.09  5047.2  557.52  5068.8  559.18  5097.1  560.09
  5160.6  560.61    5210  563.25  5252.5  567.03  5280.9  570.31  5302.4  574.49
  5316.6  577.62  5337.6  584.26  5351.7   587.6  5371.8  591.81  5377.6  591.81
#Mann= 4 ,-1 , 0
  4578.8     .05       0  4827.5     .12       0  4999.5     .07       0
    5011     .12       0
Bank Sta=4999.5,5011
XS Rating Curve= 0 ,0
Exp/Cntr=0.3,0.1

Type RM Length L Ch R = 1 ,15688   ,451,451,451
BEGIN DESCRIPTION:
Kirkwood Branch 29.0
END DESCRIPTION:
XS GIS Cut Line= 3
      2380152.67       7044397.7      2379914.34      7044018.71
      2379840.11      7043608.47
#Sta/Elev= 30
  4441.5  578.13  4463.1  577.74  4478.3  576.07    4486  574.02  4521.5  571.92
  4545.1  571.65  4551.4  570.42  4566.7  569.62  4572.6  570.18  4580.2  569.11
  4587.9  567.68  4603.2  567.09  4609.1  567.59  4718.6  562.45  4791.6  560.94
    4834  559.18    4892  558.57  4928.5  557.03  4938.7  557.07    4959  558.41
  4989.5  557.75  4993.3  550.04  4994.8  549.54  5004.8  550.04  5009.8  550.73
    5020  559.25  5030.2  561.92    5081  563.95  5243.6  573.84  5306.1  576.78
#Mann= 4 ,-1 , 0
  4441.5     .05       0  4580.2     .12       0  4993.3     .07       0
  5004.8     .12       0
Bank Sta=4993.3,5004.8
XS Rating Curve= 0 ,0
Exp/Cntr=0.3,0.1