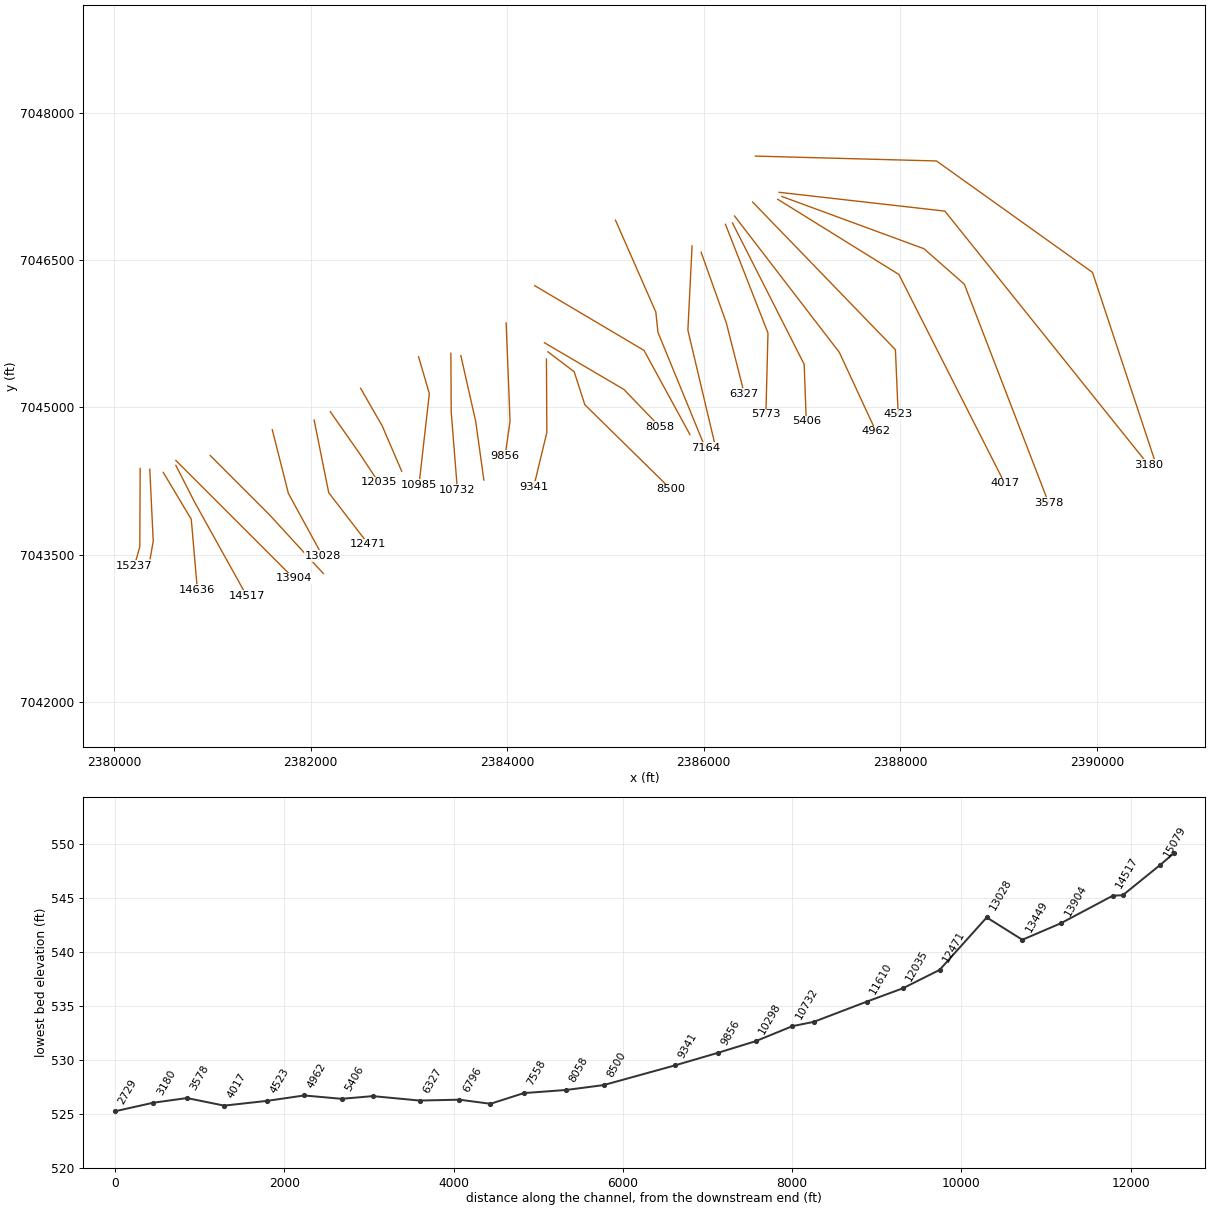
HEC-RAS study Kirkwood Branch.prj: Kirkwood Branch Base Level Engineering

--- Kirkwood Branch.g01 (geometry) --- (continued)

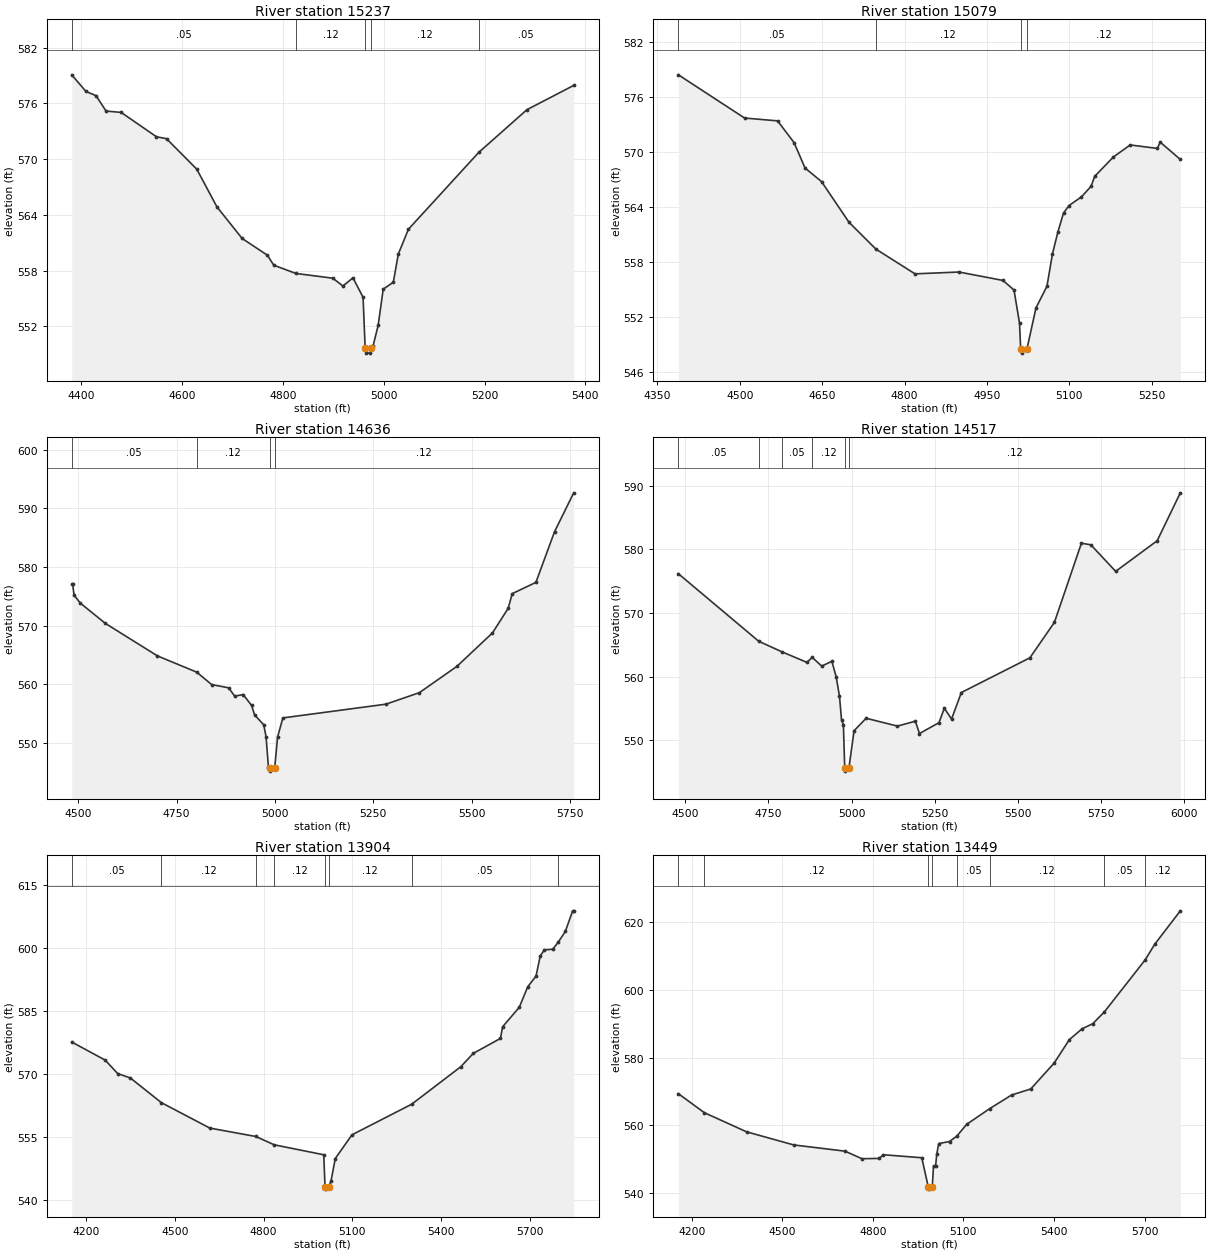
Type RM Length L Ch R = 1 ,15237   ,158,158,158
BEGIN DESCRIPTION:
Kirkwood Branch 28.5
END DESCRIPTION:
XS GIS Cut Line= 3
      2380265.95      7044378.09      2380262.05      7043581.14
      2380207.34      7043389.66
#Sta/Elev= 30
  4380.8  579.08  4408.9  577.29  4428.9  576.84  4448.9  575.18  4478.9  575.03
  4548.9  572.41  4568.9   572.2  4628.9  568.92  4668.9  564.86  4718.9  561.46
  4768.9  559.66  4781.7  558.58  4825.6  557.69  4898.9  557.18  4918.9  556.34
  4938.9  557.22  4958.9  555.12  4963.1  549.61  4964.7  549.11  4973.1  549.11
  4974.7  549.61  4978.9  549.91  4988.9  552.11  4998.9     556  5018.9  556.74
  5028.9  559.78  5048.9  562.45  5188.4  570.72    5284  575.32  5376.9  577.94
#Mann= 5 ,-1 , 0
  4380.8     .05       0  4825.6     .12       0  4963.1     .07       0
  4974.7     .12       0  5188.4     .05       0
Bank Sta=4963.1,4974.7
XS Rating Curve= 0 ,0
Exp/Cntr=0.3,0.1

Type RM Length L Ch R = 1 ,15079   ,443,443,443
BEGIN DESCRIPTION:
Kirkwood Branch 28.0
END DESCRIPTION:
XS GIS Cut Line= 3
      2380363.62      7044370.35      2380398.79      7043639.75
      2380367.53      7043459.99
#Sta/Elev= 30
  4388.1  578.45  4508.6  573.73  4568.7  573.42  4598.7  571.05  4618.7  568.27
  4648.7  566.79  4698.8  562.34  4747.8  559.41  4818.9  556.71    4899  556.91
  4979.1  555.99  4999.2  554.94  5009.2  551.33  5011.3  548.55  5012.9  548.05
  5022.9  548.55  5039.2  552.99  5059.2  555.36  5069.2  558.89  5079.2  561.31
  5089.3  563.35  5099.3  564.17    5122  565.12  5139.6  566.28  5146.1  567.36
  5180.2  569.48  5210.8  570.79  5260.3  570.41  5265.3   571.1    5302  569.21
#Mann= 4 ,-1 , 0
  4388.1     .05       0  4747.8     .12       0  5011.3     .07       0
  5022.9     .12       0
Bank Sta=5011.3,5022.9
XS Rating Curve= 0 ,0
Exp/Cntr=0.3,0.1

Type RM Length L Ch R = 1 ,14636   ,119,119,119
BEGIN DESCRIPTION:
Kirkwood Branch 27.0
END DESCRIPTION:
XS GIS Cut Line= 3
      2380500.38      7044339.05      2380785.56      7043862.43
      2380848.01      7043144.26
#Sta/Elev= 30
  4483.5  577.05  4485.8  577.05  4489.4  575.22    4505  573.86  4569.1  570.39
  4701.4  564.86    4801   562.1  4839.5  559.97  4882.3  559.43  4897.8  558.01
  4919.2  558.28  4940.6  556.45  4948.5  554.81  4971.7  553.12  4977.6  551.09
  4983.5  545.97  4986.8  545.74  4988.6  545.24  4999.5  545.74  5006.8  551.03
  5020.3   554.3  5282.3  556.64  5367.4   558.6  5462.9  563.08  5553.3  568.78
  5593.2  572.96  5603.5  575.46  5663.7  577.38  5711.2  586.02  5759.8  592.63
#Mann= 4 ,-1 , 0
  4483.5     .05       0    4801     .12       0  4986.8     .07       0
  4999.5     .12       0
Bank Sta=4986.8,4999.5
XS Rating Curve= 0 ,0
Exp/Cntr=0.3,0.1

Type RM Length L Ch R = 1 ,14517   ,613,613,613
BEGIN DESCRIPTION:
Kirkwood Branch 26.0
END DESCRIPTION:
XS GIS Cut Line= 3
      2380628.99      7044410.02      2380820.72      7044034.33
      2381348.14      7043084.99
#Sta/Elev= 30
  4479.7  576.18  4721.2  565.57  4790.8  563.92  4865.9  562.26  4881.6  563.05
  4910.2  561.68  4940.8  562.43  4953.7     560  4963.6  556.95  4969.7  553.28
  4975.4  552.45  4979.3  545.69  4981.1  545.19    4992  545.69  5007.4  551.53
  5043.7  553.49  5137.8  552.26  5191.6  553.03  5203.9  551.09  5262.5   552.8
  5278.6  555.06  5300.3  553.37  5329.7  557.53  5535.6  562.98  5609.2  568.54
  5690.4  580.97  5718.7  580.72  5793.3  576.55    5918  581.36  5987.5  588.88
#Mann= 6 ,-1 , 0
  4479.7     .05       0  4721.2     .12       0  4790.8     .05       0
  4881.6     .12       0  4979.3     .07       0    4992     .12       0
Bank Sta=4979.3,4992
XS Rating Curve= 0 ,0
Exp/Cntr=0.3,0.1

Type RM Length L Ch R = 1 ,13904   ,455,455,455
BEGIN DESCRIPTION:
Kirkwood Branch 25.0
END DESCRIPTION:
XS GIS Cut Line= 3
      2380629.02      7044459.98        2381229.        7043860.
      2381828.98      7043260.02
#Sta/Elev= 30
  4151.7  577.67  4264.8  573.36  4307.2  570.14  4349.7  569.12  4454.7  563.23
  4618.4  557.18  4773.5  555.18    4836   553.2  5003.7  550.82    5008  543.14
  5009.8  542.64  5020.7  543.14  5028.5  544.67  5042.6  549.92  5099.2  555.58
    5301  562.86  5466.9  571.78  5509.3  574.97  5601.2  578.53  5608.3  581.29
  5664.9  585.95  5693.2  590.81  5721.4  593.37  5735.6  598.17  5749.7  599.62
    5778  599.76  5795.8  601.38  5820.4  603.99  5845.2  608.91  5848.7  608.91
#Mann= 8 ,-1 , 0
  4151.7     .05       0  4454.7     .12       0  4773.5     .05       0
    4836     .12       0    5008     .07       0  5020.7     .12       0
    5301     .05       0  5795.8     .12       0
Bank Sta=5008,5020.7
XS Rating Curve= 0 ,0
Exp/Cntr=0.3,0.1

Type RM Length L Ch R = 1 ,13449   ,421,421,421
BEGIN DESCRIPTION:
Kirkwood Branch 24.0
END DESCRIPTION:
XS GIS Cut Line= 3
      2380978.97      7044510.03        2381579.        7043910.
      2382128.99      7043310.01
#Sta/Elev= 30
    4156  569.33    4242  563.71  4382.3  558.04  4537.9  554.18  4707.6  552.34
  4764.2   550.1  4820.7  550.19  4834.9  551.28  4962.1  550.39  4984.1  541.61
  4985.8  541.11  4996.8  541.61    5001  548.01    5008  548.01  5011.7  551.45
  5018.4  554.58  5054.2  555.19  5078.3  556.79  5110.9  560.27  5187.4  564.93
  5259.5  568.93  5323.1  570.73  5400.8   578.4  5450.7  585.29  5492.9  588.51
  5528.4  590.02  5566.7  593.49  5702.1   608.9  5733.7  613.51  5818.5   623.4
#Mann= 8 ,-1 , 0
    4156     .05       0    4242     .12       0  4984.1     .07       0
  4996.8     .12       0  5078.3     .05       0  5187.4     .12       0
  5566.7     .05       0  5702.1     .12       0
Bank Sta=4984.1,4996.8
XS Rating Curve= 0 ,0
Exp/Cntr=0.3,0.1

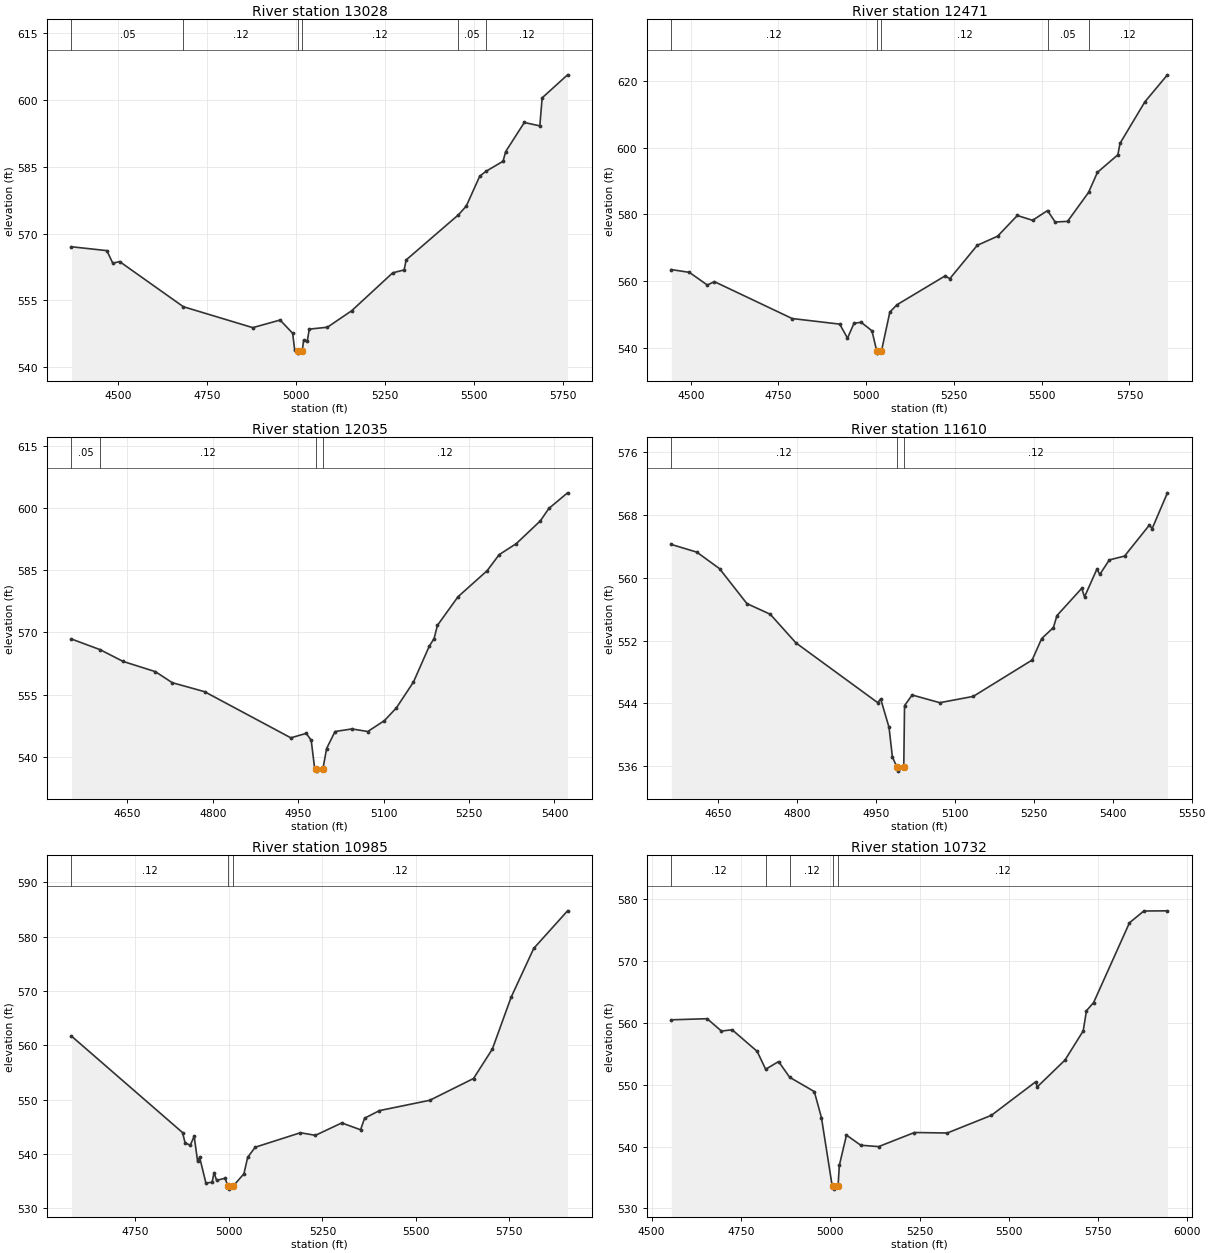
Type RM Length L Ch R = 1 ,13028   ,557,557,557
BEGIN DESCRIPTION:
Kirkwood Branch 23.0
END DESCRIPTION:
XS GIS Cut Line= 3
      2381609.92      7044772.68      2381773.99      7044124.19
      2382121.71      7043487.36
#Sta/Elev= 30
  4368.1  567.06  4467.6  566.19  4484.3  563.36  4503.4  563.74  4682.6   553.6
  4877.7   548.9  4954.6  550.61  4989.8  547.64  4995.6  543.88    5004  543.68
  5005.8  543.18  5016.8  543.68  5020.7  546.08    5031   545.9  5036.6  548.57
  5087.4  548.99  5155.7  552.69    5271   561.2  5303.2  561.86  5308.9   564.1
  5455.8  574.23  5477.8  576.18  5515.8  582.91  5533.3     584  5581.3  586.26
  5588.7  588.43  5641.1  594.96  5684.7   594.2  5691.2  600.49  5762.6  605.66
#Mann= 6 ,-1 , 0
  4368.1     .05       0  4682.6     .12       0    5004     .07       0
  5016.8     .12       0  5455.8     .05       0  5533.3     .12       0
Bank Sta=5004,5016.8
XS Rating Curve= 0 ,0
Exp/Cntr=0.3,0.1

Type RM Length L Ch R = 1 ,12471   ,436,436,436
BEGIN DESCRIPTION:
Kirkwood Branch 22.0
END DESCRIPTION:
XS GIS Cut Line= 3
      2382035.75      7044870.39      2382184.21      7044132.01
      2382586.63      7043608.46
#Sta/Elev= 30
  4444.7  563.38  4496.1  562.55  4547.1  558.76  4567.5  559.76  4788.9   548.7
  4924.5  547.02  4946.6  542.82  4965.3   547.3  4985.7  547.56  5016.3  545.02
  5030.3  538.82  5032.1  538.32  5043.1  538.82  5067.3  550.64  5087.7  552.84
  5224.8  561.49  5238.2  560.66  5316.3  570.66  5374.3  573.39  5430.5  579.61
    5474  578.17  5516.6  581.09  5538.4  577.65  5573.7  577.85  5633.5  586.54
  5658.9  592.57  5716.9  597.81  5723.2  601.27  5793.9   613.7  5858.2  621.81
#Mann= 5 ,-1 , 0
  4444.7     .12       0  5030.3     .07       0  5043.1     .12       0
  5516.6     .05       0  5633.5     .12       0
Bank Sta=5030.3,5043.1
XS Rating Curve= 0 ,0
Exp/Cntr=0.3,0.1

Type RM Length L Ch R = 1 ,12035   ,425,425,425
BEGIN DESCRIPTION:
Kirkwood Branch 21.0
END DESCRIPTION:
XS GIS Cut Line= 3
      2382199.85      7044956.32      2382492.85      7044538.32
       2382692.1      7044237.48
#Sta/Elev= 30
  4551.7  568.43  4601.9  565.87  4642.4  563.03  4699.1  560.57  4728.7  557.91
  4785.4  555.75    4937  544.63  4964.1  545.71  4972.8  544.02  4978.9  537.16
  4980.4  537.11  4982.2  536.61  4993.3  537.11  4999.8  542.05  5014.6  546.15
  5044.3  546.77  5072.1  546.15  5101.3  548.77  5122.3  551.83  5152.4  558.08
  5180.1   566.7  5188.6  568.55  5194.5  571.73  5230.6  578.61  5281.8  584.89
  5302.9  588.75    5333  591.41  5375.1  596.87  5390.1  599.87    5423  603.64
#Mann= 4 ,-1 , 0
  4551.7     .05       0  4601.9     .12       0  4980.4     .07       0
  4993.3     .12       0
Bank Sta=4980.4,4993.3
XS Rating Curve= 0 ,0
Exp/Cntr=0.3,0.1

Type RM Length L Ch R = 1 ,11610   ,625,625,625
BEGIN DESCRIPTION:
Kirkwood Branch 20.0
END DESCRIPTION:
XS GIS Cut Line= 3
       2382508.5      7045194.63        2382729.        7044810.
      2382926.49      7044350.82
#Sta/Elev= 30
  4560.7  564.23  4609.2  563.25  4652.3  561.15  4704.4   556.7  4748.7  555.35
  4797.6   551.7    4953   544.1  4958.7  544.57  4974.6  540.95    4981  537.18
  4989.7  535.88  4991.5  535.38  5002.6  535.88  5004.1  543.72  5018.5  545.07
  5071.1  544.09  5134.7  544.89  5246.7  549.52  5264.8  552.25  5287.1  553.65
  5293.8  555.17  5340.9  558.64  5346.3  557.56  5369.9   561.1  5375.3  560.41
  5393.4  562.26  5422.4  562.75  5469.5  566.69  5474.9  566.25  5503.9   570.8
#Mann= 3 ,-1 , 0
  4560.7     .12       0  4989.7     .07       0  5002.6     .12       0
Bank Sta=4989.7,5002.6
XS Rating Curve= 0 ,0
Exp/Cntr=0.3,0.1

Type RM Length L Ch R = 1 ,10985   ,253,253,253
BEGIN DESCRIPTION:
Kirkwood Branch 19.0
END DESCRIPTION:
XS GIS Cut Line= 3
      2383098.42      7045514.99       2383207.8      7045139.97
      2383102.32      7044210.18
#Sta/Elev= 30
  4579.1  561.69    4876  543.93    4883  542.02  4896.8   541.6  4907.2  543.26
  4916.4   538.6  4921.7   539.4  4938.5  534.64  4955.1  534.77  4960.3  536.55
  4967.1  535.13  4989.8  535.51  4997.7  534.01  4999.5  533.51  5010.6  534.01
  5040.2  536.34  5050.2  539.36  5070.4  541.23  5191.1  543.89  5231.4  543.42
  5301.8   545.7  5352.1  544.44  5362.8  546.57  5402.5  547.97    5537  549.87
  5654.1  553.88  5704.4   559.3  5754.7  568.86  5815.1  577.84  5905.5  584.76
#Mann= 3 ,-1 , 0
  4579.1     .12       0  4997.7     .07       0  5010.6     .12       0
Bank Sta=4997.7,5010.6
XS Rating Curve= 0 ,0
Exp/Cntr=0.3,0.1

Type RM Length L Ch R = 1 ,10732   ,434,434,434
BEGIN DESCRIPTION:
Kirkwood Branch 18.0
END DESCRIPTION:
XS GIS Cut Line= 3
      2383426.58      7045550.23      2383430.49      7044952.44
      2383492.93      7044164.11
#Sta/Elev= 30
  4555.3   560.5  4655.5  560.68  4695.5  558.68  4725.5  558.89  4795.5   555.4
  4819.3   552.5  4855.5  553.75  4886.6   551.2  4955.5  548.89  4975.5  544.66
  5005.5  533.64  5009.1  533.61  5010.9  533.11    5022  533.61  5025.5  536.94
  5045.5  541.85  5085.5  540.21  5135.5  539.99  5235.8  542.27  5327.7  542.19
  5451.2  545.05  5574.7  550.45  5579.7  549.66  5657.1  553.98  5708.2  558.71
  5717.3  561.97  5737.4   563.3  5837.7   576.2  5877.8   578.1  5943.9  578.13
#Mann= 5 ,-1 , 0
  4555.3     .12       0  4819.3     .05       0  4886.6     .12       0
  5009.1     .07       0    5022     .12       0
Bank Sta=5009.1,5022
XS Rating Curve= 0 ,0
Exp/Cntr=0.3,0.1

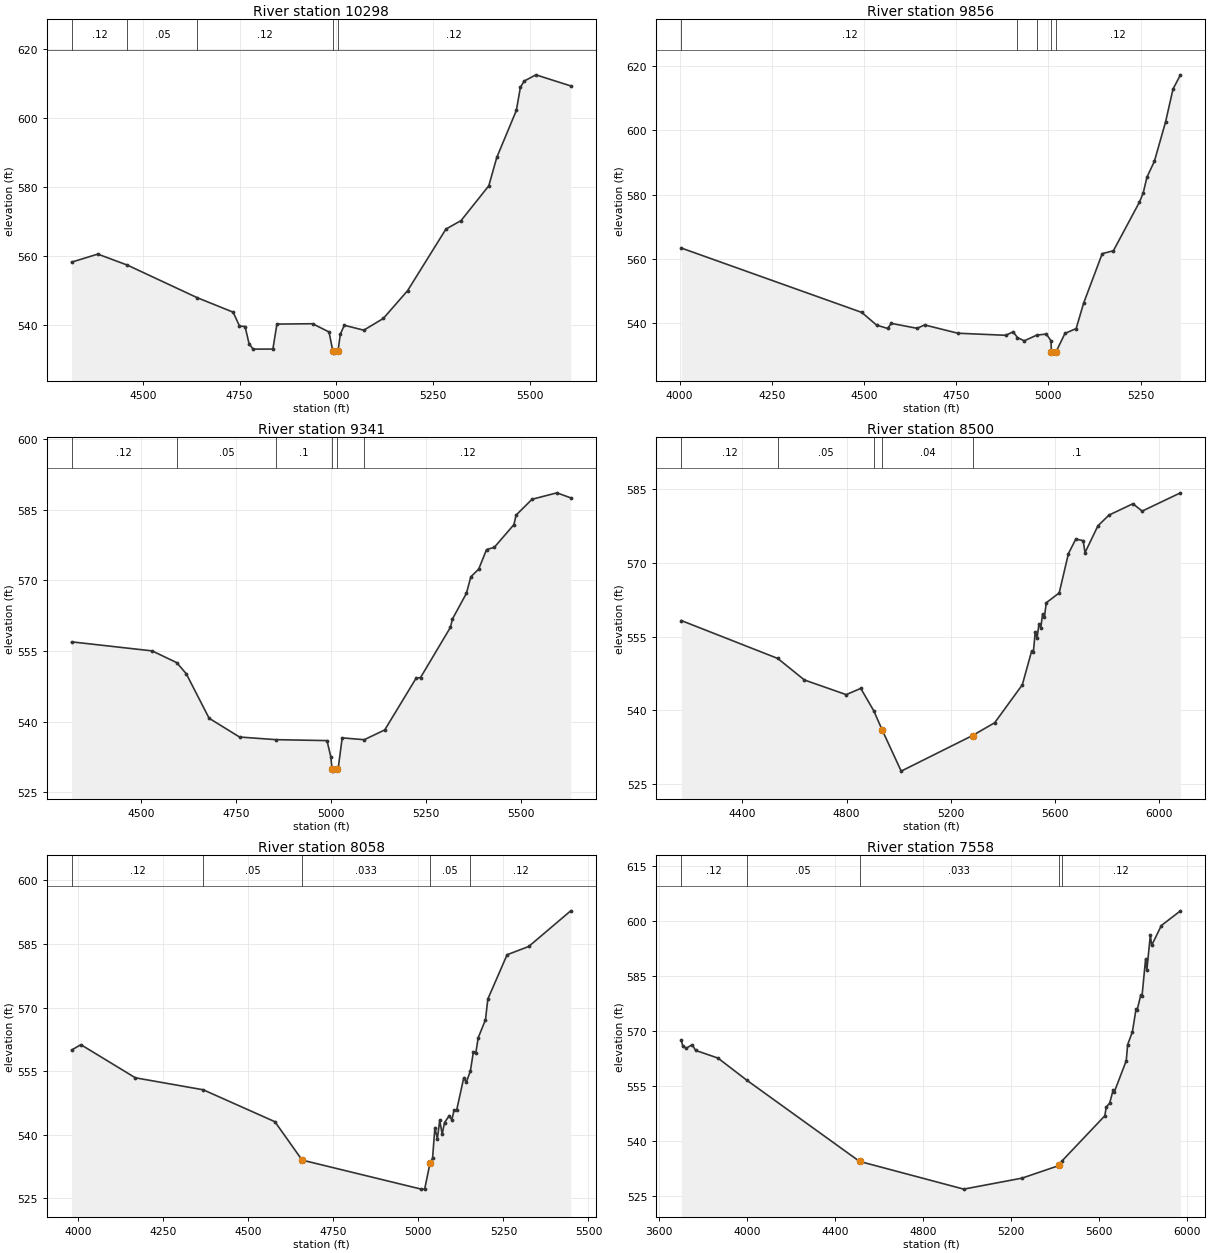
Type RM Length L Ch R = 1 ,10298   ,442,442,442
BEGIN DESCRIPTION:
Kirkwood Branch 17.0
END DESCRIPTION:
XS GIS Cut Line= 3
      2383528.15      7045526.76        2383679.        7044860.
      2383762.57      7044260.91
#Sta/Elev= 30
  4316.5  558.15  4384.1  560.49  4460.7  557.28  4640.9  547.82  4733.5  543.62
  4749.9  539.59  4764.3  539.45  4774.5   534.5  4784.8  532.89  4836.1   532.9
  4846.5  540.16  4938.6  540.26  4981.1  537.87    4991  532.22  4992.9  531.72
    5004  532.22  5010.2  537.18  5020.3  539.81  5070.8  538.39  5121.3   541.8
    5184  549.89  5282.8  567.75    5322  570.24  5393.5  580.33  5414.1  588.56
  5464.6  602.21  5475.1  608.95  5484.8  610.75    5515  612.57    5605  609.35
#Mann= 5 ,-1 , 0
  4316.5     .12       0  4460.7     .05       0  4640.9     .12       0
    4991     .07       0    5004     .12       0
Bank Sta=4991,5004
XS Rating Curve= 0 ,0
Exp/Cntr=0.3,0.1

Type RM Length L Ch R = 1 ,9856    ,515,515,515
BEGIN DESCRIPTION:
Kirkwood Branch 16.0
END DESCRIPTION:
XS GIS Cut Line= 3
      2383989.16      7045858.79        2384029.        7044860.
      2383979.01      7044510.04
#Sta/Elev= 30
  4004.9  563.36  4494.1  543.32  4534.1  539.39  4564.1  538.33  4574.1  539.91
  4644.2  538.37  4664.2  539.43  4754.3  536.85  4884.4   536.2  4904.4  537.29
  4916.1   535.5  4934.4  534.48  4968.5  536.26  4994.5  536.59    5007  534.48
  5008.1  531.15  5009.9  530.65  5021.1  531.15  5044.9   536.8  5075.2  538.29
  5095.4  546.19  5145.9  561.62  5176.2  562.52  5246.9  577.69    5257  580.51
  5267.1  585.41  5287.3  590.37  5317.6  602.62  5337.8  612.86    5358  617.29
#Mann= 5 ,-1 , 0
  4004.9     .12       0  4916.1      .1       0  4968.5     .12       0
  5008.1     .07       0  5021.1     .12       0
Bank Sta=5008.1,5021.1
XS Rating Curve= 0 ,0
Exp/Cntr=0.3,0.1

Type RM Length L Ch R = 1 ,9341    ,841,841,841
BEGIN DESCRIPTION:
Kirkwood Branch 15.0
END DESCRIPTION:
XS GIS Cut Line= 3
      2384399.38      7045491.55      2384403.29      7044745.38
      2384270.51      7044194.74
#Sta/Elev= 30
  4318.2  556.95  4529.8  555.03  4594.7  552.53  4619.8  550.16  4679.8  540.71
  4759.8  536.72  4855.6  536.16  4989.8  535.96  4999.8  532.54  5003.1  529.97
    5005  529.47  5016.4  529.97  5019.8  530.39  5029.8  536.54  5087.8  536.15
  5141.7  538.23  5224.2  549.23  5235.8  549.36  5314.5  560.04  5319.6  561.79
  5356.4  567.25  5368.2  570.79  5388.8  572.41  5409.4  576.56  5429.9  577.05
  5481.4  581.87  5487.2   583.9  5529.1  587.26  5594.5  588.63  5630.8  587.56
#Mann= 6 ,-1 , 0
  4318.2     .12       0  4594.7     .05       0  4855.6      .1       0
  5003.1     .07       0  5016.4      .1       0  5087.8     .12       0
Bank Sta=5003.1,5016.4
XS Rating Curve= 0 ,0
Exp/Cntr=0.3,0.1

Type RM Length L Ch R = 1 ,8500    ,442,442,442
BEGIN DESCRIPTION:
Kirkwood Branch 14.0
END DESCRIPTION:
XS GIS Cut Line= 4
      2384414.07      7045565.73      2384681.72      7045362.26
       2384789.6      7045027.26      2385664.61      7044167.74
#Sta/Elev= 30
  4165.8  558.29  4535.7  550.58  4637.8   546.2  4798.2  543.22    4854  544.49
  4903.9  539.93  4936.5  535.99  5009.1  527.65    5283   534.9  5367.8   537.5
  5473.8  545.22  5509.3  552.03  5516.3  551.92  5523.4  555.95  5530.4  554.74
  5537.6  557.59  5544.6  556.82  5551.7  559.67  5558.7  559.09  5565.8  561.92
  5615.3  563.92  5650.7  571.92    5679  574.88  5707.3  574.56  5714.3  572.11
  5763.9  577.58  5806.3  579.76  5898.2  582.07  5933.5  580.57  6080.5  584.29
#Mann= 5 ,-1 , 0
  4165.8     .12       0  4535.7     .05       0  4903.9      .1       0
  4936.5     .04       0    5283      .1       0
Bank Sta=4936.5,5283
XS Rating Curve= 0 ,0
Exp/Cntr=0.3,0.1

Type RM Length L Ch R = 1 ,8058    ,500,500,500
BEGIN DESCRIPTION:
Kirkwood Branch 13.0
END DESCRIPTION:
XS GIS Cut Line= 3
      2384378.71       7045657.8      2385186.36      7045183.13
       2385554.4      7044800.94
#Sta/Elev= 30
  3980.4  560.01  4007.7  561.27  4167.8  553.46  4367.4  550.63  4578.1   543.1
  4658.1  534.05  5008.2   527.2  5018.4   527.2  5034.4  533.47  5041.6   534.5
  5048.5   541.7  5055.7  539.09  5062.7  543.43  5069.9  540.17  5076.8  542.91
    5091  544.55  5098.2  543.51  5105.1   545.9  5112.3  545.79  5133.4  553.48
  5140.6  552.39  5152.6  554.99  5161.7  559.57  5168.9  559.37  5175.8  562.91
  5197.2  567.14  5204.1  572.03  5260.7  582.48  5324.3  584.43  5447.8  592.84
#Mann= 5 ,-1 , 0
  3980.4     .12       0  4367.4     .05       0  4658.1    .033       0
  5034.4     .05       0  5152.6     .12       0
Bank Sta=4658.1,5034.4
XS Rating Curve= 0 ,0
Exp/Cntr=0.3,0.1

Type RM Length L Ch R = 1 ,7558    ,394,394,394
BEGIN DESCRIPTION:
Kirkwood Branch 12.0
END DESCRIPTION:
XS GIS Cut Line= 3
      2384279.49      7046238.79      2385391.82      7045579.89
      2385858.78       7044723.8
#Sta/Elev= 30
  3701.6  567.49  3707.9  565.95  3723.6  565.37  3750.8  566.31  3766.4  564.77
  3867.8  562.68  3998.4  556.66  4511.2  534.48  4984.8  526.91  5250.1  529.92
  5419.1  533.38  5430.9  534.58    5626  546.93  5632.2  549.32  5647.8  550.35
    5664  554.02  5669.7  553.54  5723.3  561.96  5729.5  566.31  5751.3  569.88
  5767.4  575.94  5773.1  575.88  5789.3  579.88    5795  579.68  5811.1  589.65
  5816.8  586.72  5832.9  596.25  5838.6  593.43  5882.8  598.85  5969.6  602.86
#Mann= 5 ,-1 , 0
  3701.6     .12       0  3998.4     .05       0  4511.2    .033       0
  5419.1     .05       0  5430.9     .12       0
Bank Sta=4511.2,5419.1
XS Rating Curve= 0 ,0
Exp/Cntr=0.3,0.1

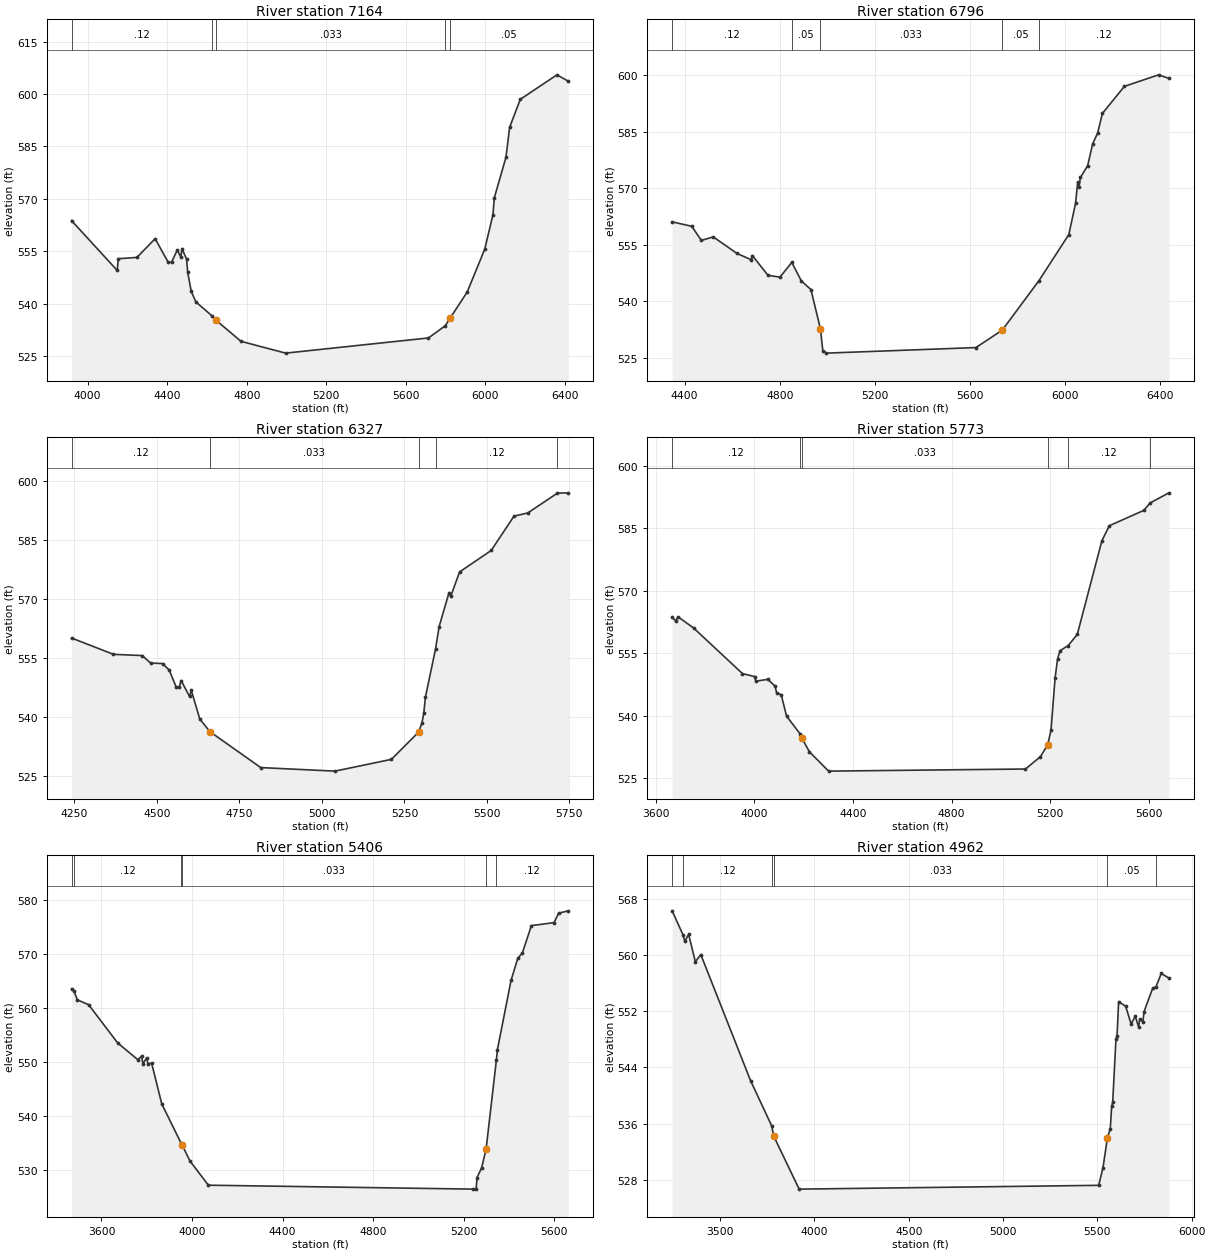
Type RM Length L Ch R = 1 ,7164    ,368,368,368
BEGIN DESCRIPTION:
Kirkwood Branch 11.0
END DESCRIPTION:
XS GIS Cut Line= 4
      2385101.33       7046904.8      2385512.27      7045969.56
      2385533.52       7045764.1      2386014.64      7044589.62
#Sta/Elev= 30
  3919.2  563.81    4149  549.56  4154.4  552.91  4247.8  553.28  4339.5  558.64
    4405  551.91  4422.2  551.91    4451  555.41  4468.9  553.39  4474.4  555.79
  4497.7   552.8  4503.3  549.04  4521.1  543.57  4544.4  540.56  4624.6  536.61
  4643.3  535.44    4771   529.3  4995.5  525.92  5713.7  530.26  5798.4  533.76
  5821.7  535.87  5908.2  543.37  5996.4  555.63  6037.9  565.48  6044.4  570.28
  6103.2  581.91  6121.8  590.51  6175.2  598.47  6359.4  605.48  6416.5  603.65
#Mann= 5 ,-1 , 0
  3919.2     .12       0  4624.6     .05       0  4643.3    .033       0
  5798.4     .12       0  5821.7     .05       0
Bank Sta=4643.3,5821.7
XS Rating Curve= 0 ,0
Exp/Cntr=0.3,0.1

Type RM Length L Ch R = 1 ,6796    ,469,469,469
BEGIN DESCRIPTION:
Kirkwood Branch 10.0
END DESCRIPTION:
XS GIS Cut Line= 3
      2385880.69      7046642.63      2385838.18      7045785.35
      2386121.58      7044587.97
#Sta/Elev= 30
  4347.8   561.1  4430.5  559.91  4470.6  556.17  4520.6  557.11  4620.8  552.71
  4680.3  551.05  4685.3  552.15  4750.9  546.92    4801  546.44  4850.9  550.34
  4891.4   545.4  4931.2  543.16  4971.2  532.76  4981.2  526.99  4995.9   526.3
    5625  527.77  5735.7  532.39  5890.4  545.54  6015.6  557.73    6044     566
  6052.7  571.53  6057.9  570.21  6064.6  572.88    6095  576.01  6115.9  581.79
  6136.5  584.58  6157.1  589.86  6249.5  597.02  6393.4  600.07  6436.6  599.12
#Mann= 5 ,-1 , 0
  4347.8     .12       0  4850.9     .05       0  4971.2    .033       0
  5735.7     .05       0  5890.4     .12       0
Bank Sta=4971.2,5735.7
XS Rating Curve= 0 ,0
Exp/Cntr=0.3,0.1

Type RM Length L Ch R = 1 ,6327    ,554,554,554
BEGIN DESCRIPTION:
Kirkwood Branch 9.0
END DESCRIPTION:
XS GIS Cut Line= 3
      2385972.79      7046578.88        2386229.        7045860.
      2386412.07       7045140.6
#Sta/Elev= 30
  4241.2  560.04  4368.3  555.89  4455.5  555.58    4481  553.67  4517.1  553.55
  4537.3   551.9  4558.5  547.55  4568.1  547.67  4573.4  549.23  4598.9  545.19
  4604.3  546.74  4629.8  539.49  4660.6  536.25  4814.7  527.12  5039.6  526.22
  5210.7  529.21  5293.3  536.15  5303.5  538.55  5308.6  540.86  5313.9  545.08
  5344.4  557.24  5355.2  562.91  5385.3  571.58  5390.5  570.63  5417.1  576.81
  5513.2  582.29  5582.2     591  5623.5  591.79  5713.7  596.84  5746.7  596.92
#Mann= 5 ,-1 , 0
  4241.2     .12       0  4660.6    .033       0  5293.3     .05       0
  5344.4     .12       0  5713.7     .05       0
Bank Sta=4660.6,5293.3
XS Rating Curve= 0 ,0
Exp/Cntr=0.3,0.1

Type RM Length L Ch R = 1 ,5773    ,367,367,367
BEGIN DESCRIPTION:
Kirkwood Branch 8.5
END DESCRIPTION:
XS GIS Cut Line= 3
      2386220.75      7046862.32      2386652.95      7045757.01
       2386631.7      7044928.08
#Sta/Elev= 30
  3666.2  563.58    3680  562.81  3690.2  563.72  3753.4  561.04  3951.5  550.08
  4000.4  549.37  4005.8  548.26  4054.7  548.69  4084.5  547.03  4089.9  545.46
  4108.9  544.99  4130.4  539.86  4186.4  535.52  4193.1  534.52    4223   531.3
  4301.1  526.63  5100.1  527.14  5160.1  530.07  5190.1  532.93  5203.7  536.49
  5220.1  548.96  5230.1  553.54  5240.1  555.56  5273.5  556.83  5310.2  559.48
  5410.2  582.04  5440.2  585.63  5580.3  589.32  5606.1  591.12  5682.2  593.54
#Mann= 6 ,-1 , 0
  3666.2     .12       0  4186.4     .05       0  4193.1    .033       0
  5190.1     .05       0  5273.5     .12       0  5606.1     .05       0
Bank Sta=4193.1,5190.1
XS Rating Curve= 0 ,0
Exp/Cntr=0.3,0.1

Type RM Length L Ch R = 1 ,5406    ,444,444,444
BEGIN DESCRIPTION:
Kirkwood Branch 8.0
END DESCRIPTION:
XS GIS Cut Line= 3
      2386291.63      7046876.42      2387021.37      7045438.19
      2387042.63      7044857.25
#Sta/Elev= 30
  3467.8  563.59  3478.3  563.22  3493.5  561.55  3543.6  560.63  3671.6  553.54
  3760.6  550.43  3777.3  551.08  3782.9  549.65  3799.6  550.77  3805.2  549.67
  3821.8  549.75  3866.4  542.22  3951.6  534.93  3955.4  534.67  3990.8  531.62
  4072.3  527.11  5242.9  526.38  5254.9  526.38  5258.9  528.52  5278.9  530.32
  5298.9   533.8  5344.4   550.4  5348.9  552.29    5409  565.15    5439  569.28
    5459  570.24    5499  575.33  5599.1  575.89  5619.1  577.64  5661.9  578.08
#Mann= 6 ,-1 , 0
  3467.8     .05       0  3478.3     .12       0  3951.6     .05       0
  3955.4    .033       0  5298.9     .05       0  5344.4     .12       0
Bank Sta=3955.4,5298.9
XS Rating Curve= 0 ,0
Exp/Cntr=0.3,0.1

Type RM Length L Ch R = 1 ,4962    ,439,439,439
BEGIN DESCRIPTION:
Kirkwood Branch 7.0
END DESCRIPTION:
XS GIS Cut Line= 3
      2386312.88      7046947.28        2387379.        7045560.
      2387751.12      7044758.05
#Sta/Elev= 30
  3245.8  566.25  3304.5  562.77  3312.5  561.91  3333.3   562.9  3368.7  559.01
  3397.7  560.03  3661.4  542.12  3774.2  535.64  3783.8  534.25  3919.1  526.69
  5507.1  527.23    5530  529.74  5552.9  533.91  5568.7   535.3  5575.8  538.44
  5581.3  539.01  5598.7  548.02  5604.3   548.4  5612.8  553.34  5650.1  552.68
  5678.9  550.17  5701.4  551.26  5718.8  549.71  5724.3  550.83  5741.7  550.51
  5747.2  551.89    5793  555.22    5811  555.47  5838.8  557.35  5879.5  556.69
#Mann= 6 ,-1 , 0
  3245.8     .05       0  3304.5     .12       0  3774.2     .05       0
  3783.8    .033       0  5552.9     .05       0    5811     .12       0
Bank Sta=3783.8,5552.9
XS Rating Curve= 0 ,0
Exp/Cntr=0.3,0.1

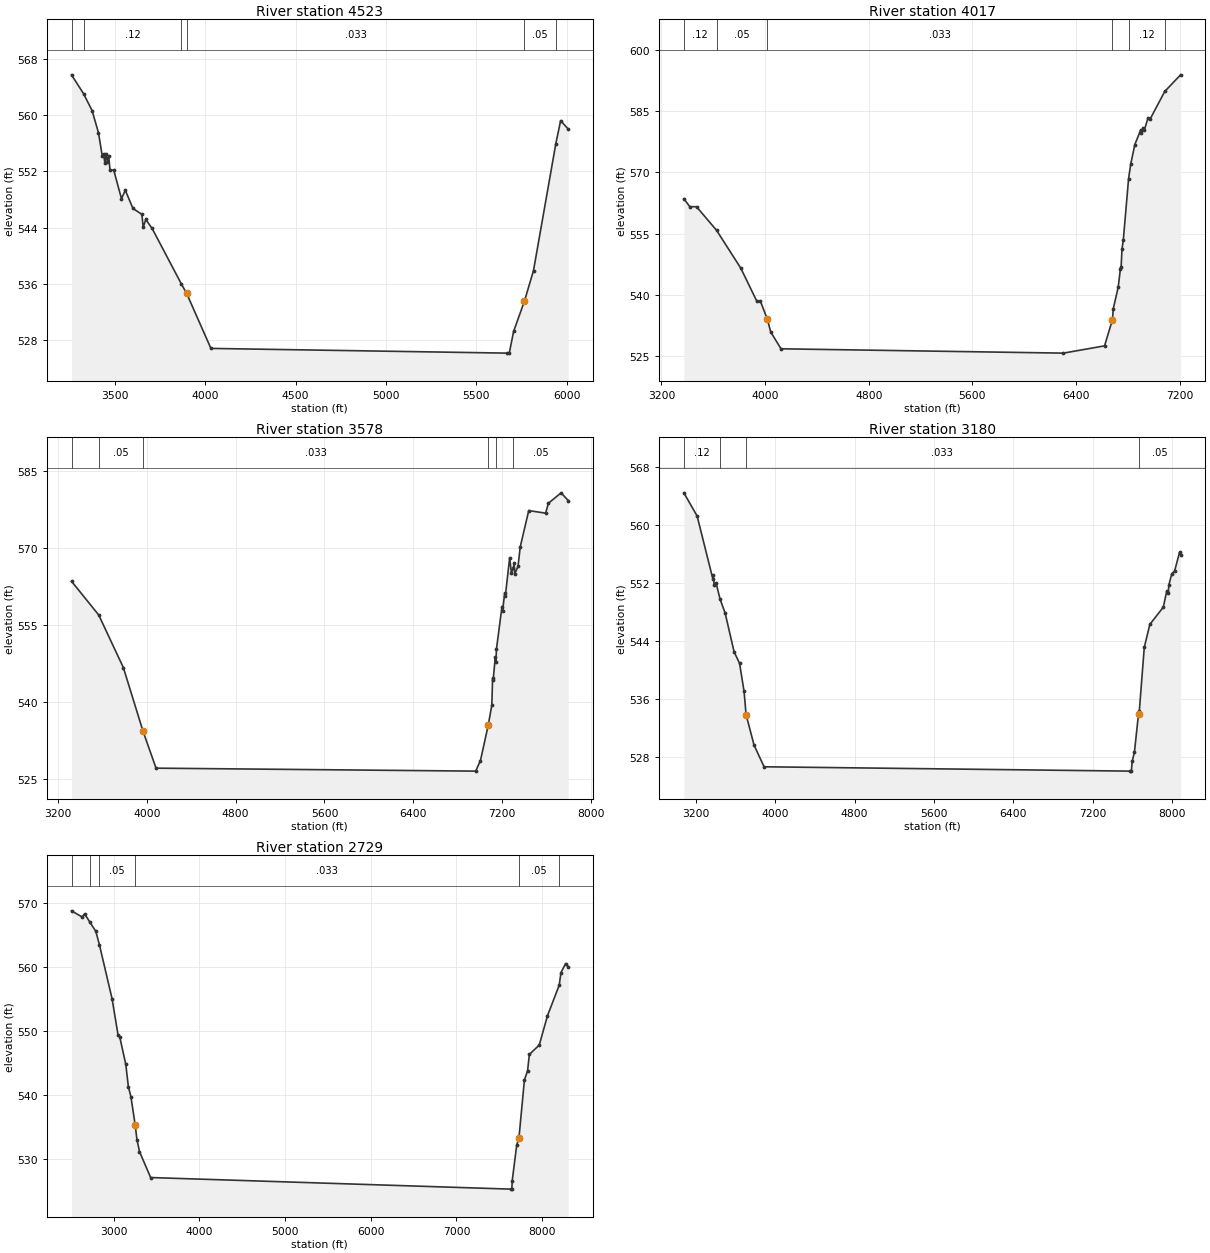
Type RM Length L Ch R = 1 ,4523    ,506,506,506
BEGIN DESCRIPTION:
Kirkwood Branch 6.0
END DESCRIPTION:
XS GIS Cut Line= 3
      2386497.07      7047089.01      2387949.51      7045586.97
      2387977.85      7044928.11
#Sta/Elev= 30
  3259.6  565.69  3326.6     563  3373.4  560.62  3408.9  557.47    3430  554.14
  3437.2   554.5  3444.1  553.17  3451.3  554.44  3458.3  553.36  3465.5  554.16
  3472.4  552.24  3493.7  552.12  3536.2  548.11  3557.3  549.31  3599.7  546.72
  3649.1  545.89  3656.3  544.04  3670.5  545.16  3705.7  543.89  3866.5  536.06
  3896.9  534.66  4031.1  526.86  5670.3  526.19  5682.3  526.19  5706.3  529.27
  5766.4  533.58  5816.4  537.91  5940.1  555.94  5966.6  559.19  6008.5  557.99
#Mann= 6 ,-1 , 0
  3259.6     .05       0  3326.6     .12       0  3866.5     .05       0
  3896.9    .033       0  5766.4     .05       0  5940.1     .12       0
Bank Sta=3896.9,5766.4
XS Rating Curve= 0 ,0
Exp/Cntr=0.3,0.1

Type RM Length L Ch R = 1 ,4017    ,439,439,439
BEGIN DESCRIPTION:
Kirkwood Branch 5.0
END DESCRIPTION:
XS GIS Cut Line= 3
      2386752.16      7047117.32      2387984.94      7046352.15
      2389061.86      7044226.64
#Sta/Elev= 30
  3373.3  563.52  3419.1  561.58  3471.1  561.57  3625.2  555.82  3812.4  546.55
  3934.5  538.58  3964.7  538.42  4016.7  534.11  4043.9  530.92    4123  526.81
  6302.2  525.75  6620.3  527.53  6681.3  533.96  6687.6  536.61  6725.9  541.93
  6742.6   546.4  6748.2   546.9  6754.8  551.18  6764.8  553.36  6805.6  568.42
  6822.1     572  6853.9  576.77  6898.5  580.31  6904.1  579.58  6920.7  580.83
  6926.3  580.25  6956.6  583.35  6970.9  582.96  7084.8  589.77    7207  593.84
#Mann= 6 ,-1 , 0
  3373.3     .12       0  3625.2     .05       0  4016.7    .033       0
  6681.3     .05       0  6805.6     .12       0  7084.8     .05       0
Bank Sta=4016.7,6681.3
XS Rating Curve= 0 ,0
Exp/Cntr=0.3,0.1

Type RM Length L Ch R = 1 ,3578    ,398,398,398
BEGIN DESCRIPTION:
Kirkwood Branch 4.0
END DESCRIPTION:
XS GIS Cut Line= 4
      2386794.61      7047145.69        2388240.       7046614.3
      2388650.93      7046252.96       2389508.2       7044028.3
#Sta/Elev= 30
  3322.8  563.54  3568.1  556.94  3789.7  546.67  3967.2   534.2  4083.9  527.03
    6961  526.45  7004.2  528.52  7074.3  535.44  7106.4  539.34  7113.4  544.57
  7118.7  544.34    7138  548.74  7143.3  547.72    7148  550.27  7197.9   558.6
  7203.3  557.74  7222.6  561.28  7227.9  560.63  7267.2  568.15  7282.5  565.17
  7300.1  566.17  7307.2  567.11  7312.5  564.96  7342.5  566.44  7361.8  570.21
  7438.6  577.34  7590.9  576.84  7615.5  578.77  7730.1  580.81  7794.1   579.3
#Mann= 6 ,-1 , 0
  3322.8     .12       0  3568.1     .05       0  3967.2    .033       0
  7074.3     .05       0    7148     .12       0  7300.1     .05       0
Bank Sta=3967.2,7074.3
XS Rating Curve= 0 ,0
Exp/Cntr=0.3,0.1

Type RM Length L Ch R = 1 ,3180    ,451,451,451
BEGIN DESCRIPTION:
Kirkwood Branch 3.0
END DESCRIPTION:
XS GIS Cut Line= 3
       2386766.3      7047188.19      2388452.55      7046996.89
      2390521.39      7044417.92
#Sta/Elev= 30
    3080  564.39  3213.6  561.19    3372  552.52    3377  553.08  3384.6  551.73
  3404.8  551.96  3444.3  549.74  3495.3  547.84  3585.9  542.47  3640.9  540.89
  3686.6     537  3706.7  533.81  3787.2   529.6  3887.9  526.62  7575.5  526.02
  7587.7  526.02    7596  527.36  7618.4  528.63    7660  533.95    7668  534.37
  7717.6  543.07  7773.6  546.25  7909.6  548.63  7944.8   550.9  7959.2  550.62
  7965.6   551.7  7994.4  553.22  8023.2  553.62  8072.9  556.18  8083.3  555.88
#Mann= 4 ,-1 , 0
    3080     .12       0  3444.3     .05       0  3706.7    .033       0
    7660     .05       0
Bank Sta=3706.7,7660
XS Rating Curve= 0 ,0
Exp/Cntr=0.3,0.1

Type RM Length L Ch R = 1 ,2729    ,0,0,0
BEGIN DESCRIPTION:
Kirkwood Branch 2.0
END DESCRIPTION:
XS GIS Cut Line= 4
      2386525.45       7047556.6      2388367.53      7047507.01
      2389954.57      7046373.41      2390584.56      7044469.29
#Sta/Elev= 30
  2505.9   568.7  2629.5  567.74  2659.5  568.22  2717.6  566.99  2789.6   565.5
    2831  563.44  2979.6  554.97  3049.6  549.29  3069.7  548.97  3139.7  544.71
  3169.7  541.23  3199.7  539.66  3249.7  535.22  3269.7  532.98  3299.7  531.09
  3429.8  527.04  7634.1  525.23  7646.4  525.23  7650.8  526.54  7703.5  532.13
  7729.8  533.28  7793.2  542.27  7830.2  543.72  7850.9  546.27  7966.8  547.74
  8061.6  552.28  8199.8   557.1  8219.6  559.04  8274.3  560.47  8304.6  559.94
#Mann= 6 ,-1 , 0
  2505.9     .05       0  2717.6     .12       0    2831     .05       0
  3249.7    .033       0  7729.8     .05       0  8199.8    .075       0
Bank Sta=3249.7,7729.8
XS Rating Curve= 0 ,0
Exp/Cntr=0.3,0.1

Chan Stop Cuts=-1
Use User Specified Reach Order=0
Composite Channel Slope=5