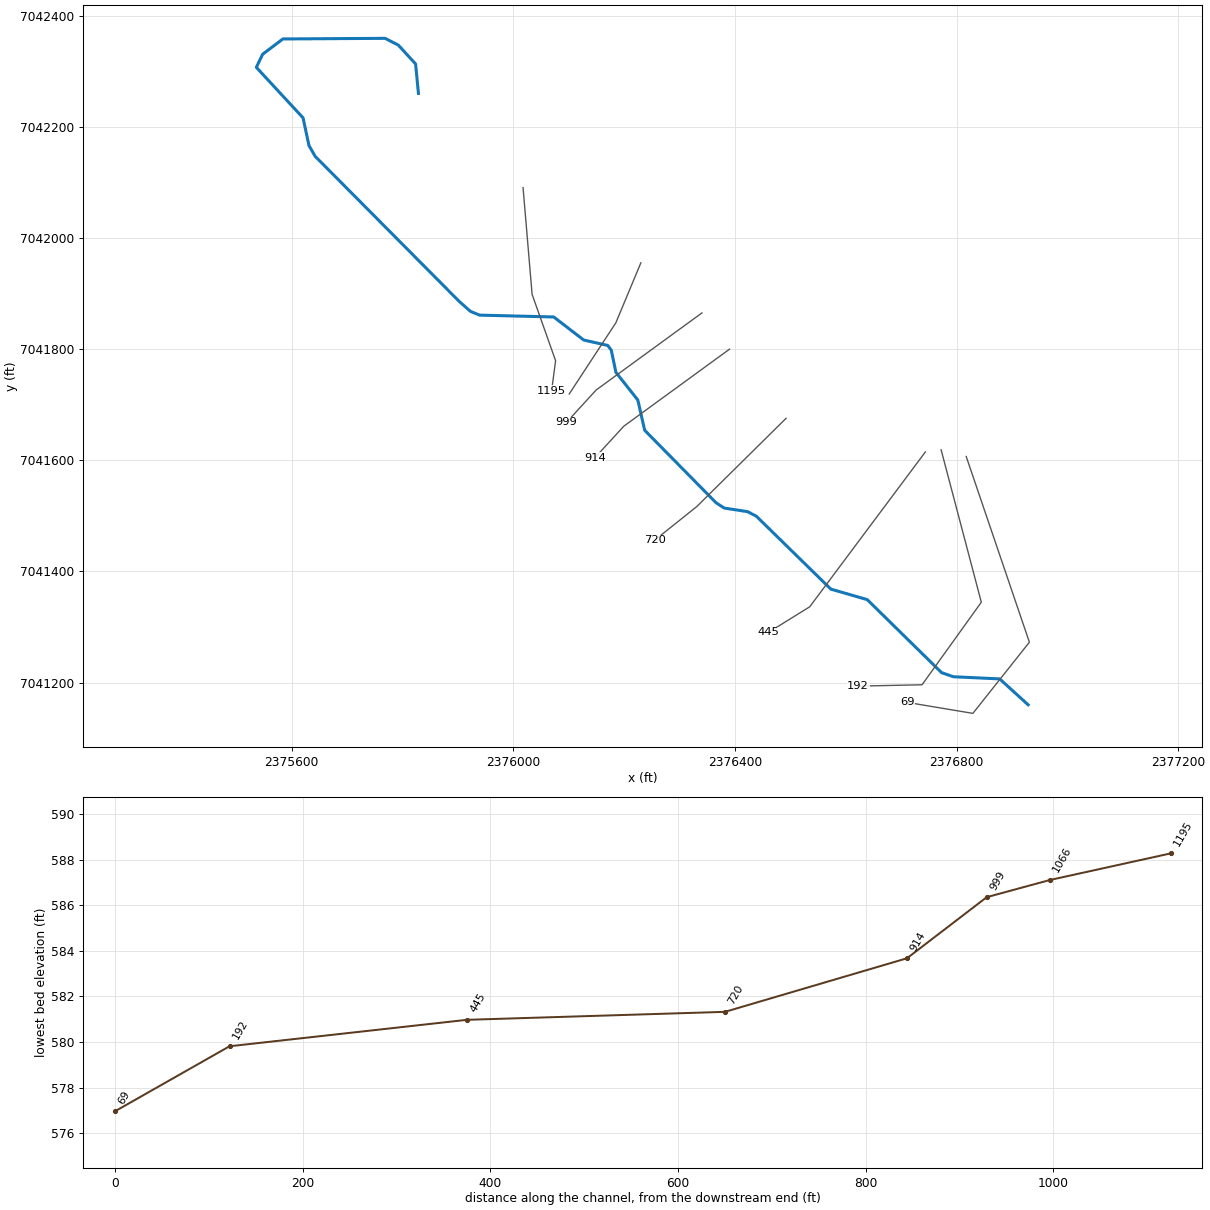
--- Kirkwood Branch Tr.prj (project) ---

Proj Title=Kirkwood Branch Tr Base Level Engineering
Current Plan=p01
Default Exp/Contr=0.3,0.1
English Units
Geom File=g01
Flow File=f01
Plan File=p01
Y Axis Title=Elevation
X Axis Title(PF)=Main Channel Distance
X Axis Title(XS)=Station
BEGIN DESCRIPTION:
Kirkwood Branch Tr
END DESCRIPTION:
DSS Export Rating Curves= 0
DSS Export Rating Curve Sorted= 0
DSS Export Volume Flow Curves= 0
DXF OffsetX= 0
DXF OffsetY= 0
DXF ScaleX= 1
DXF ScaleY= 10

--- Kirkwood Branch Tr.p01 (plan) ---

Plan Title=Multiple Run
Program Version=4.10
Short Identifier=Multiple
Geom File=g01
Flow File=f01
Subcritical Flow
K Sum by GR= 0
Std Step Tol= 0.01
Critical Tol= 0.01
Num of Std Step Trials= 20
Max Error Tol= 0.3
Flow Tol Ratio= 0.001
Split Flow NTrial= 30
Split Flow Tol= 0.02
Split Flow Ratio= 0.02
Log Output Level= 0
Friction Slope Method= 1
Unsteady Friction Slope Method= 2
Unsteady Bridges Friction Slope Method= 1
Parabolic Critical Depth
Global Vel Dist= 1 , 1 , 1
Global Log Level= 0
CheckData=True
Encroach Param=-1 ,0,0, 0
BEGIN DESCRIPTION:
Multiple Run
END DESCRIPTION:
Computation Interval=1HOUR
Output Interval=1HOUR
Run HTab= 0
Run UNet= 0
Run PostProcess= 0
Run WQNet= 0
UNET Theta= 1
UNET Theta Warmup= 1
UNET ZTol= 0.02
UNET ZSATol= 0.05
UNET MxIter= 20
UNET MaxInSteps= 0
UNET DtIC= 0
UNET DtMin= 0
UNET MaxCRTS= 20
UNET WFStab= 2
UNET SFStab= 1
UNET WFX= 1
UNET SFX= 1
UNET DSS MLevel= 4
UNET DZMax Abort= 100
UNET Convert EG Bridges= 0
UNET Use Existing IB Tables=-1
UNET Froude Reduction=False
UNET Froude Limit= 1
UNET Froude Power= 10
UNET Time Slicing=0,0, 5
UNET Junction Losses=0
Instantaneous Interval=1HOUR
Write IC File= 0
Write IC File at Sim End=0
Echo Input=False
Echo Parameters=False
Echo Output=False
Write Detailed= 0
WQ AD Non Conservative
WQ ULTIMATE=-1
WQ Max Comp Step=1HOUR
WQ Output Interval=15MIN
WQ Output Selected Increments= 0
WQ Output face flow=0
WQ Output face velocity=0
WQ Output face area=0
WQ Output face dispersion=0
WQ Output cell volume=0
WQ Output cell surface area=0
WQ Output cell continuity=0
WQ Output cumulative cell continuity=0
WQ Output face conc=0
WQ Output face dconc_dx=0
WQ Output face courant=0
WQ Output face peclet=0
WQ Output face adv mass=0
WQ Output face disp mass=0
WQ Output cell mass=0
WQ Output cell source sink temp=0
WQ Output cell source sink nsm=0
WQ Output MaxMinRange=-1
WQ Daily Max Min Mean=-1
WQ Daily Range=0
WQ Daily Time=0
WQ Create Restart=0
WQ Fixed Restart=0
WQ System Summary=0
WQ Use Fixed Temperature=0
Sorting and Armoring Iterations= 10
XS Update Threshold= 0.02
Hydraulics Update Threshold= 0.02
Energy Slope Method= 1
Volume Change Method= 0
XS Weighting Method= 0
Number of US Weighted Cross Sections= 1
Number of DS Weighted Cross Sections= 1
Upstream XS Weight=0.25
Main XS Weight=0.5
Downstream XS Weight=0.25
Number of DS XS's Weighted with US Boundary= 1
Upstream Boundary Weight= 1
Weight of XSs Associated with US Boundary= 0
Number of US XS's Weighted with DS Boundary= 1
Downstream Boundary Weight= 0.5
Weight of XSs Associated with DS Boundary= 0.5
Sediment Output Level= 4
Mass or Volume Output= 0
Output Increment Type= 1
Profile and TS Output Increment= 10
XS Output Flag= 0
XS Output Increment= 10
Disregard all LS=0
Disregard all Conn=0
Disregard all Breaches=0
Disregard all Pumps=0

--- Kirkwood Branch Tr.f01 (steady flow) ---

Flow Title=Multiple
Number of Profiles=7
Profile Names=10-year,25-year,50-year,1pct_min,100-year,1pct_plu,500-year
River Rch & RM= Kirkwood Branch ,Reach-1,1195
     429     572     687     410     819    1634    1160
Boundary for River Rch & Prof#=Kirkwood Branch ,Reach-1,1
Up Type=0
Dn Type=3
Dn Slope=0.005
Boundary for River Rch & Prof#=Kirkwood Branch ,Reach-1,2
Up Type=0
Dn Type=3
Dn Slope=0.005
Boundary for River Rch & Prof#=Kirkwood Branch ,Reach-1,3
Up Type=0
Dn Type=3
Dn Slope=0.005
Boundary for River Rch & Prof#=Kirkwood Branch ,Reach-1,4
Up Type=0
Dn Type=3
Dn Slope=0.005
Boundary for River Rch & Prof#=Kirkwood Branch ,Reach-1,5
Up Type=0
Dn Type=3
Dn Slope=0.005
Boundary for River Rch & Prof#=Kirkwood Branch ,Reach-1,6
Up Type=0
Dn Type=3
Dn Slope=0.005
Boundary for River Rch & Prof#=Kirkwood Branch ,Reach-1,7
Up Type=0
Dn Type=3
Dn Slope=0.005

--- Kirkwood Branch Tr.g01 (geometry) ---

Geom Title=Existing Conditions

River Reach=Kirkwood Branch ,Reach-1
Reach XY= 30
      2375829.00      7042260.00      2375823.87      7042312.95
      2375792.67      7042346.92      2375768.70      7042359.05
      2375584.44      7042357.94      2375548.01      7042330.49
      2375536.51      7042306.88      2375620.80      7042216.05
      2375631.53      7042166.05      2375642.63      7042146.79
      2375902.13      7041886.17      2375922.81      7041867.82
      2375939.44      7041861.06      2376073.09      7041857.76
      2376127.16      7041816.28      2376170.54      7041806.50
      2376176.93      7041798.01      2376185.24      7041758.15
      2376224.82      7041708.29      2376237.14      7041653.95
      2376365.79      7041523.63      2376380.65      7041513.98
      2376422.95      7041507.46      2376438.68      7041499.22
      2376572.95      7041368.16      2376638.68      7041349.22
      2376772.82      7041217.85      2376794.19      7041210.47
      2376877.59      7041206.61      2376929.00      7041160.00

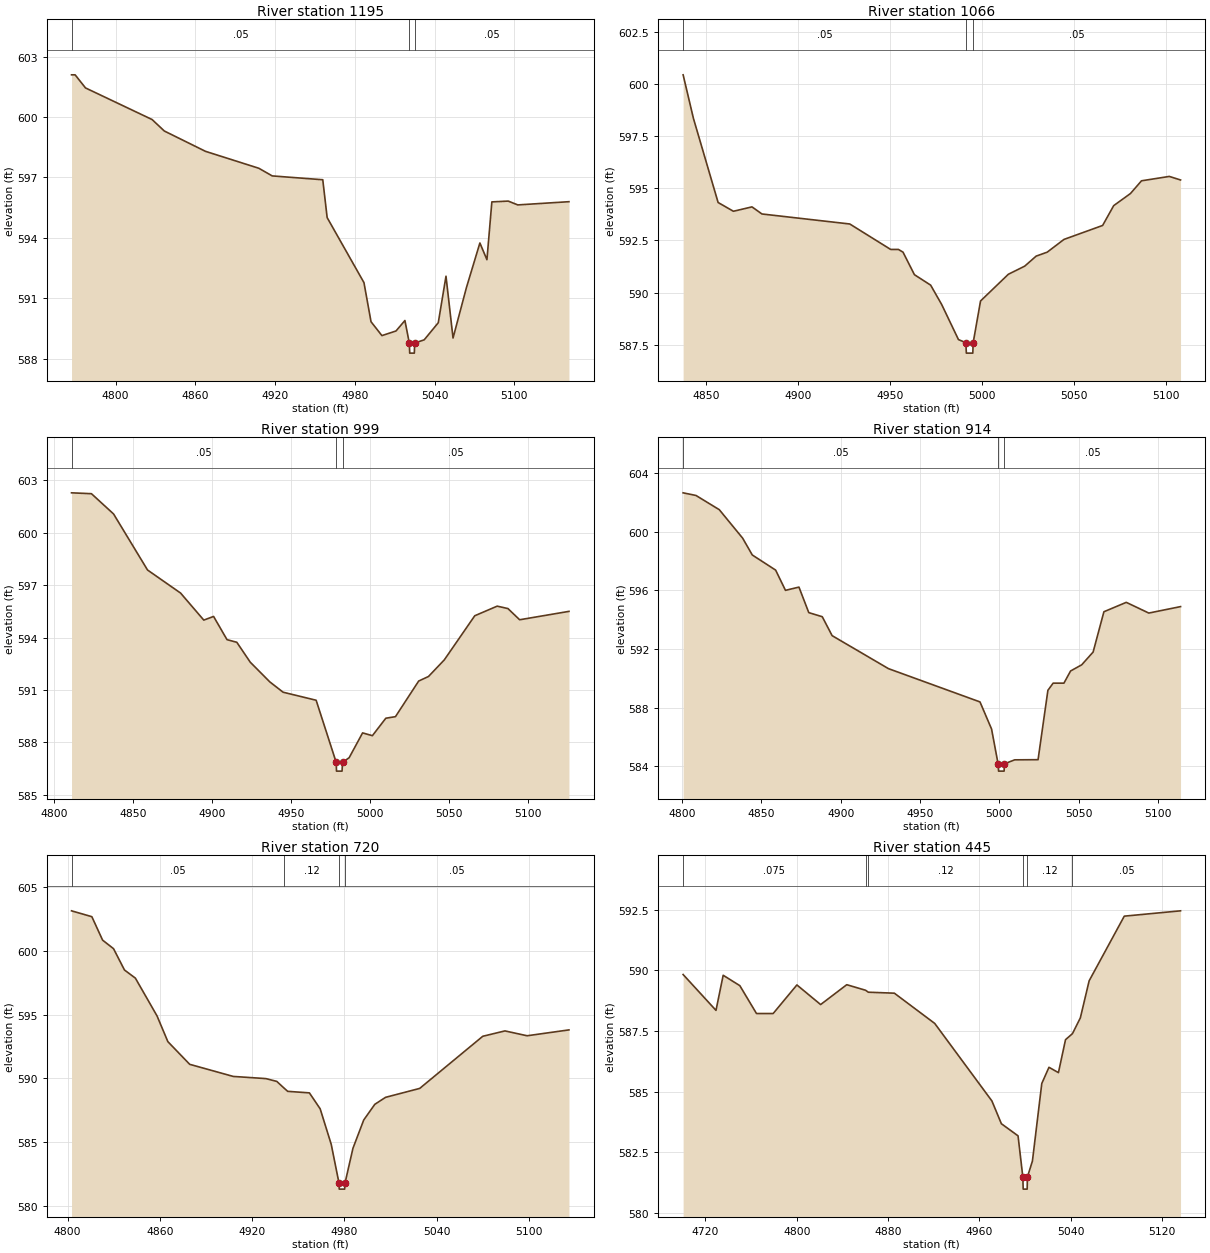
Type RM Length L Ch R = 1,1195,129,129,129
BEGIN DESCRIPTION:
Kirkwood Branch Tr 3.0
END DESCRIPTION:
XS GIS Cut Line= 4
      2376017.73      7042090.42      2376034.07      7041898.42
      2376076.44      7041779.08      2376069.23      7041724.68
#Sta/Elev= 30
  4766.9  602.09  4769.6  602.09  4777.4  601.44  4827.5  599.87  4836.7  599.30
  4867.7  598.29  4907.8  597.45  4917.9  597.07  4955.9  596.88  4959.2  595.00
  4986.9  591.77  4992.2  589.83  5000.4  589.14  5011.0  589.37  5017.7  589.89
  5021.0  588.77  5021.3  588.27  5024.8  588.27  5025.0  588.77  5032.2  588.93
  5042.8  589.78  5048.6  592.09  5053.9  589.02  5064.0  591.53  5074.1  593.74
  5079.4  592.91  5083.1  595.78  5095.4  595.82  5102.6  595.63  5141.1  595.79
#Mann=3,-1,0
  4766.9    0.05       0  5021.0    0.05       0  5025.0    0.05       0
Bank Sta=5021,5025
Exp/Cntr=0.3,0.1

Type RM Length L Ch R = 1,1066,67,67,67
BEGIN DESCRIPTION:
Kirkwood Branch Tr 2.7
END DESCRIPTION:
XS GIS Cut Line= 3
      2376230.25      7041955.16      2376185.21      7041847.30
      2376101.05      7041719.27
#Sta/Elev= 30
  4837.7  600.44  4843.3  598.35  4856.7  594.32  4865.0  593.90  4875.1  594.11
  4880.5  593.77  4928.2  593.29  4950.4  592.07  4954.6  592.07  4957.1  591.94
  4963.3  590.86  4972.1  590.36  4978.1  589.43  4987.2  587.75  4991.2  587.60
  4991.5  587.10  4995.0  587.10  4995.2  587.60  4999.2  589.60  5014.3  590.88
  5023.2  591.27  5029.4  591.75  5035.4  591.94  5044.5  592.55  5065.5  593.22
  5071.5  594.17  5080.6  594.75  5086.6  595.36  5101.7  595.57  5107.8  595.40
#Mann=3,-1,0
  4837.7    0.05       0  4991.2   0.033       0  4995.2    0.05       0
Bank Sta=4991.2,4995.2
Exp/Cntr=0.3,0.1

Type RM Length L Ch R = 1,999,85,85,85
BEGIN DESCRIPTION:
Kirkwood Branch Tr 2.4
END DESCRIPTION:
XS GIS Cut Line= 3
      2376340.50      7041865.08      2376149.65      7041726.38
      2376096.30      7041668.29
#Sta/Elev= 30
  4811.2  602.29  4823.8  602.24  4837.8  601.08  4859.3  597.87  4880.2  596.55
  4894.9  595.00  4901.1  595.21  4909.6  593.88  4915.8  593.73  4924.3  592.59
  4936.7  591.46  4945.1  590.87  4966.0  590.41  4978.7  586.85  4978.9  586.35
  4982.4  586.35  4982.7  586.85  4986.9  587.12  4995.4  588.54  5001.6  588.38
  5010.1  589.38  5016.2  589.47  5030.9  591.51  5037.1  591.77  5047.1  592.72
  5066.4  595.25  5080.6  595.80  5087.4  595.66  5094.8  595.02  5126.0  595.50
#Mann=3,-1,0
  4811.2    0.05       0  4978.7    0.05       0  4982.7    0.05       0
Bank Sta=4978.7,4982.7
Exp/Cntr=0.3,0.1

Type RM Length L Ch R = 1,914,194,194,194
BEGIN DESCRIPTION:
Kirkwood Branch Tr 2.2
END DESCRIPTION:
XS GIS Cut Line= 3
      2376390.33      7041799.90      2376199.44      7041661.18
      2376147.00      7041604.08
#Sta/Elev= 30
  4800.7  602.65  4808.8  602.47  4823.5  601.50  4838.2  599.56  4844.3  598.41
  4859.0  597.38  4865.2  596.00  4873.7  596.22  4879.9  594.48  4888.4  594.20
  4894.6  592.91  4930.1  590.66  4987.8  588.39  4995.1  586.54  4999.2  584.17
  4999.5  583.67  5003.0  583.67  5003.2  584.17  5009.7  584.44  5024.4  584.45
  5030.6  589.18  5033.9  589.67  5040.7  589.67  5044.9  590.50  5051.9  590.92
  5059.1  591.79  5065.9  594.54  5080.0  595.18  5094.2  594.45  5114.2  594.89
#Mann=3,-1,0
  4800.7    0.05       0  4999.2    0.05       0  5003.2    0.05       0
Bank Sta=4999.2,5003.2
Exp/Cntr=0.3,0.1

Type RM Length L Ch R = 1,720,275,275,275
BEGIN DESCRIPTION:
Kirkwood Branch Tr 2.0
END DESCRIPTION:
XS GIS Cut Line= 3
      2376492.24      7041675.39      2376331.03      7041516.55
      2376255.19      7041456.11
#Sta/Elev= 30
  4802.6  603.15  4815.8  602.69  4822.8  600.85  4829.9  600.18  4837.0  598.51
  4844.1  597.87  4858.2  594.90  4865.2  592.89  4879.4  591.11  4907.7  590.16
  4928.9  589.99  4936.0  589.77  4940.6  589.26  4943.1  588.99  4957.2  588.87
  4964.2  587.62  4971.4  584.83  4976.4  581.82  4976.6  581.32  4980.1  581.32
  4980.4  581.82  4985.5  584.52  4992.5  586.74  4999.7  587.97  5006.7  588.52
  5028.9  589.22  5069.9  593.31  5084.3  593.73  5098.7  593.35  5125.9  593.81
#Mann=4,-1,0
  4802.6    0.05       0  4940.6    0.12       0  4976.4    0.05       0
  4980.4    0.05       0
Bank Sta=4976.4,4980.4
Exp/Cntr=0.3,0.1

Type RM Length L Ch R = 1,445,253,253,253
BEGIN DESCRIPTION:
Kirkwood Branch Tr 1.0
END DESCRIPTION:
XS GIS Cut Line= 3
      2376743.61      7041614.98      2376534.94      7041336.35
      2376460.29      7041290.14
#Sta/Elev= 30
  4700.4  589.83  4729.2  588.35  4735.5  589.80  4750.1  589.37  4764.7  588.22
  4779.3  588.22  4800.1  589.40  4820.9  588.59  4843.8  589.41  4860.3  589.18
  4862.7  589.10  4885.5  589.06  4920.9  587.81  4971.0  584.61  4979.3  583.67
  4993.9  583.17  4998.1  581.47  4998.4  580.97  5001.9  580.97  5002.1  581.47
  5006.5  582.13  5014.7  585.33  5021.0  586.00  5029.3  585.78  5035.5  587.14
  5041.6  587.39  5048.5  588.04  5056.2  589.57  5087.0  592.24  5136.3  592.46
#Mann=6,-1,0
  4700.4   0.075       0  4860.3    0.05       0  4862.7    0.12       0
  4998.1    0.07       0  5002.1    0.12       0  5041.6    0.05       0
Bank Sta=4998.1,5002.1
Exp/Cntr=0.3,0.1

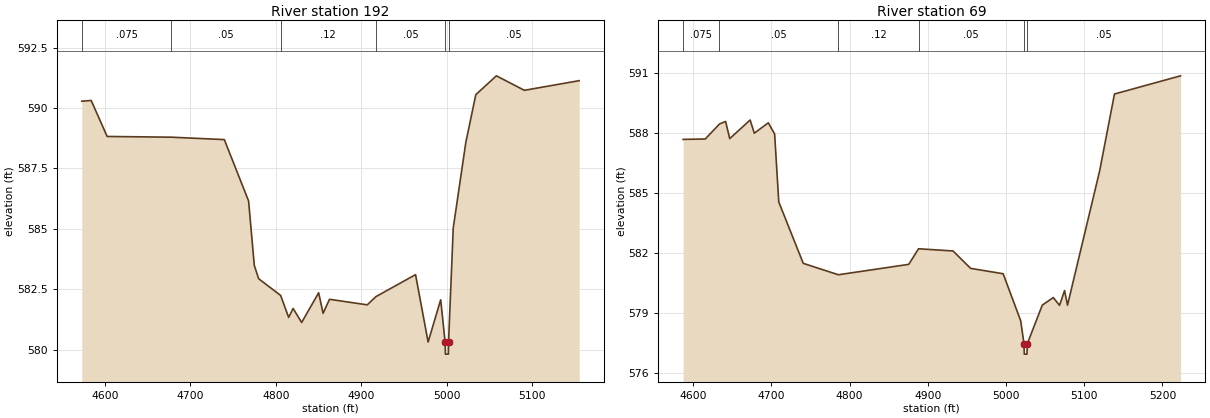
Type RM Length L Ch R = 1,192,122,122,122
BEGIN DESCRIPTION:
Kirkwood Branch Tr 0.6
END DESCRIPTION:
XS GIS Cut Line= 4
      2376772.00      7041618.72      2376844.51      7041344.55
      2376737.58      7041196.00      2376622.13      7041193.64
#Sta/Elev= 30
  4572.8  590.28  4583.8  590.31  4602.5  588.82  4677.6  588.79  4739.6  588.69
  4768.0  586.15  4774.7  583.48  4779.8  582.93  4805.5  582.24  4814.9  581.33
  4820.1  581.70  4830.1  581.12  4850.0  582.35  4855.2  581.50  4862.7  582.08
  4906.9  581.85  4917.0  582.19  4963.4  583.10  4978.1  580.31  4992.8  582.06
  4998.0  580.31  4998.3  579.81  5001.8  579.81  5002.0  580.31  5007.5  585.03
  5022.2  588.57  5033.9  590.55  5058.0  591.33  5090.7  590.73  5154.9  591.13
#Mann=6,-1,0
  4572.8   0.075       0  4677.6    0.05       0  4805.5    0.12       0
  4917.0    0.05       0  4998.0   0.033       0  5002.0    0.05       0
Bank Sta=4998,5002
Exp/Cntr=0.3,0.1

Type RM Length L Ch R = 1,69,0,0,0
BEGIN DESCRIPTION:
Kirkwood Branch Tr 0.3
END DESCRIPTION:
XS GIS Cut Line= 4
      2376817.24      7041606.75      2376931.24      7041272.60
      2376829.29      7041144.57      2376711.64      7041164.18
#Sta/Elev= 30
  4587.1  587.70  4615.4  587.72  4633.6  588.47  4641.4  588.60  4646.7  587.74
  4672.8  588.67  4678.1  588.01  4696.0  588.53  4704.1  587.97  4709.4  584.57
  4740.7  581.50  4785.6  580.93  4875.6  581.45  4888.1  582.23  4932.2  582.12
  4954.7  581.25  4996.3  580.98  5018.7  578.63  5023.0  577.46  5023.3  576.96
  5026.8  576.96  5027.0  577.46  5046.3  579.41  5060.4  579.79  5068.4  579.40
  5074.8  580.14  5078.6  579.41  5119.7  586.13  5138.6  589.97  5223.1  590.88
#Mann=6,-1,0
  4587.1   0.075       0  4633.6    0.05       0  4785.6    0.12       0
  4888.1    0.05       0  5023.0   0.033       0  5027.0    0.05       0
Bank Sta=5023,5027
Exp/Cntr=0.3,0.1

Chan Stop Cuts=-1