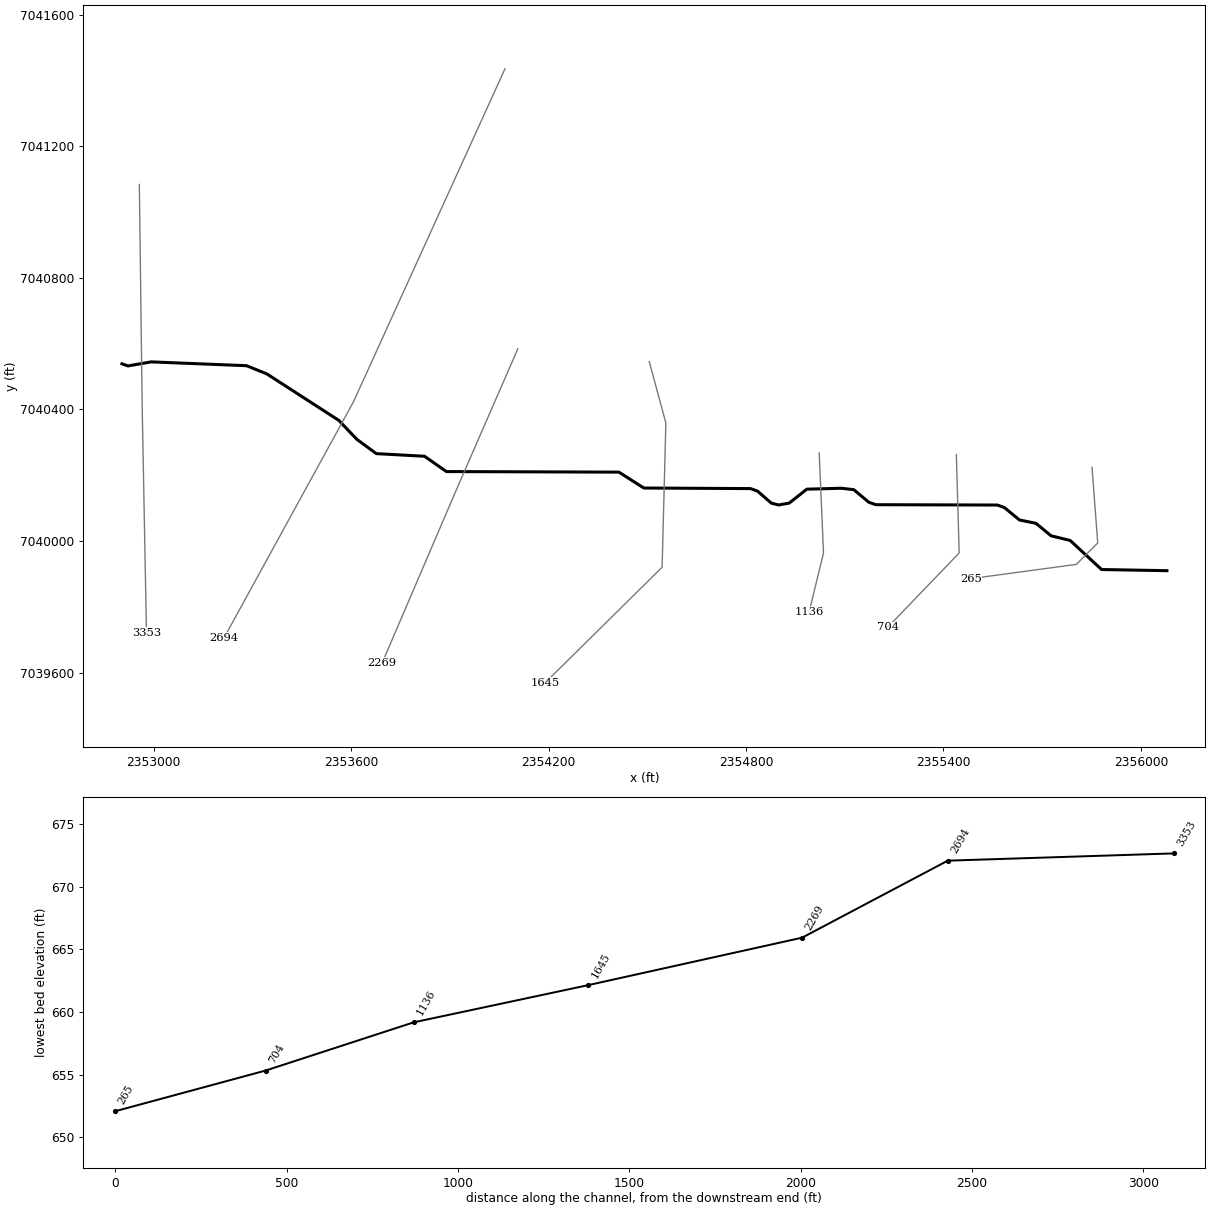
--- LWE S 002.prj (project) ---

Proj Title=LWE S 002 Base Level Engineering
Current Plan=p01
Default Exp/Contr=0.3,0.1
English Units
Geom File=g01
Flow File=f01
Plan File=p01
Y Axis Title=Elevation
X Axis Title(PF)=Main Channel Distance
X Axis Title(XS)=Station
BEGIN DESCRIPTION:
LWE S 002
END DESCRIPTION:
DSS Export Rating Curves= 0
DSS Export Rating Curve Sorted= 0
DSS Export Volume Flow Curves= 0
DXF OffsetX= 0
DXF OffsetY= 0
DXF ScaleX= 1
DXF ScaleY= 10

--- LWE S 002.p01 (plan) ---

Plan Title=Multiple Run
Program Version=4.10
Short Identifier=Multiple
Geom File=g01
Flow File=f01
Subcritical Flow
K Sum by GR= 0
Std Step Tol= 0.01
Critical Tol= 0.01
Num of Std Step Trials= 20
Max Error Tol= 0.3
Flow Tol Ratio= 0.001
Split Flow NTrial= 30
Split Flow Tol= 0.02
Split Flow Ratio= 0.02
Log Output Level= 0
Friction Slope Method= 1
Unsteady Friction Slope Method= 2
Unsteady Bridges Friction Slope Method= 1
Parabolic Critical Depth
Global Vel Dist= 1 , 1 , 1
Global Log Level= 0
CheckData=True
Encroach Param=-1 ,0,0, 0
BEGIN DESCRIPTION:
Multiple Run
END DESCRIPTION:
Computation Interval=1HOUR
Output Interval=1HOUR
Run HTab= 0
Run UNet= 0
Run PostProcess= 0
Run WQNet= 0
UNET Theta= 1
UNET Theta Warmup= 1
UNET ZTol= 0.02
UNET ZSATol= 0.05
UNET MxIter= 20
UNET MaxInSteps= 0
UNET DtIC= 0
UNET DtMin= 0
UNET MaxCRTS= 20
UNET WFStab= 2
UNET SFStab= 1
UNET WFX= 1
UNET SFX= 1
UNET DSS MLevel= 4
UNET DZMax Abort= 100
UNET Convert EG Bridges= 0
UNET Use Existing IB Tables=-1
UNET Froude Reduction=False
UNET Froude Limit= 1
UNET Froude Power= 10
UNET Time Slicing=0,0, 5
UNET Junction Losses=0
Instantaneous Interval=1HOUR
Write IC File= 0
Write IC File at Sim End=0
Echo Input=False
Echo Parameters=False
Echo Output=False
Write Detailed= 0
WQ AD Non Conservative
WQ ULTIMATE=-1
WQ Max Comp Step=1HOUR
WQ Output Interval=15MIN
WQ Output Selected Increments= 0
WQ Output face flow=0
WQ Output face velocity=0
WQ Output face area=0
WQ Output face dispersion=0
WQ Output cell volume=0
WQ Output cell surface area=0
WQ Output cell continuity=0
WQ Output cumulative cell continuity=0
WQ Output face conc=0
WQ Output face dconc_dx=0
WQ Output face courant=0
WQ Output face peclet=0
WQ Output face adv mass=0
WQ Output face disp mass=0
WQ Output cell mass=0
WQ Output cell source sink temp=0
WQ Output cell source sink nsm=0
WQ Output MaxMinRange=-1
WQ Daily Max Min Mean=-1
WQ Daily Range=0
WQ Daily Time=0
WQ Create Restart=0
WQ Fixed Restart=0
WQ System Summary=0
WQ Use Fixed Temperature=0
Sorting and Armoring Iterations= 10
XS Update Threshold= 0.02
Hydraulics Update Threshold= 0.02
Energy Slope Method= 1
Volume Change Method= 0
XS Weighting Method= 0
Number of US Weighted Cross Sections= 1
Number of DS Weighted Cross Sections= 1
Upstream XS Weight=0.25
Main XS Weight=0.5
Downstream XS Weight=0.25
Number of DS XS's Weighted with US Boundary= 1
Upstream Boundary Weight= 1
Weight of XSs Associated with US Boundary= 0
Number of US XS's Weighted with DS Boundary= 1
Downstream Boundary Weight= 0.5
Weight of XSs Associated with DS Boundary= 0.5
Sediment Output Level= 4
Mass or Volume Output= 0
Output Increment Type= 1
Profile and TS Output Increment= 10
XS Output Flag= 0
XS Output Increment= 10
Disregard all LS=0
Disregard all Conn=0
Disregard all Breaches=0
Disregard all Pumps=0

--- LWE S 002.f01 (steady flow) ---

Flow Title=Multiple
Program Version=4.10
Number of Profiles= 7
Profile Names=10-year,25-year,50-year,1pct_min,100-year,1pct_plu,500-year
River Rch & RM=LWE S 002,Reach-1         ,3353
     531     708     850     506    1010    2014    1422
Boundary for River Rch & Prof#=LWE S 002,Reach-1         , 1
Up Type= 0
Dn Type= 3
Dn Slope=0.007
Boundary for River Rch & Prof#=LWE S 002,Reach-1         , 2
Up Type= 0
Dn Type= 3
Dn Slope=0.007
Boundary for River Rch & Prof#=LWE S 002,Reach-1         , 3
Up Type= 0
Dn Type= 3
Dn Slope=0.007
Boundary for River Rch & Prof#=LWE S 002,Reach-1         , 4
Up Type= 0
Dn Type= 3
Dn Slope=0.007
Boundary for River Rch & Prof#=LWE S 002,Reach-1         , 5
Up Type= 0
Dn Type= 3
Dn Slope=0.007
Boundary for River Rch & Prof#=LWE S 002,Reach-1         , 6
Up Type= 0
Dn Type= 3
Dn Slope=0.007
Boundary for River Rch & Prof#=LWE S 002,Reach-1         , 7
Up Type= 0
Dn Type= 3
Dn Slope=0.007
DSS Import GetInterval= 0
DSS Import GetPeak= 0
DSS Import FillOption= 0

--- LWE S 002.g01 (geometry) ---

Geom Title=Existing Conditions
Program Version=4.10

River Reach=LWE S 002       ,Reach-1
Reach XY= 30
      2352903.58      7040538.71      2352921.64      7040532.19
      2352992.48      7040544.51      2353282.39      7040532.91
      2353344.24      7040507.79      2353562.63       7040366.7
      2353617.44      7040309.16      2353676.65      7040265.71
      2353823.06      7040257.73       2353889.5      7040211.22
      2354413.78      7040209.48       2354489.5      7040161.22
      2354813.79      7040159.46      2354835.08      7040151.81
      2354876.82      7040115.38      2354899.18      7040109.72
      2354931.18      7040115.38      2354984.93      7040157.72
      2355089.17       7040160.5      2355127.43      7040156.23
      2355172.94      7040118.14      2355194.22      7040110.52
      2355563.79      7040109.49      2355585.08      7040101.91
      2355630.74      7040064.19       2355681.2      7040053.92
      2355726.81       7040016.1      2355785.05      7040001.84
      2355880.47      7039913.54        2356079.        7039910.

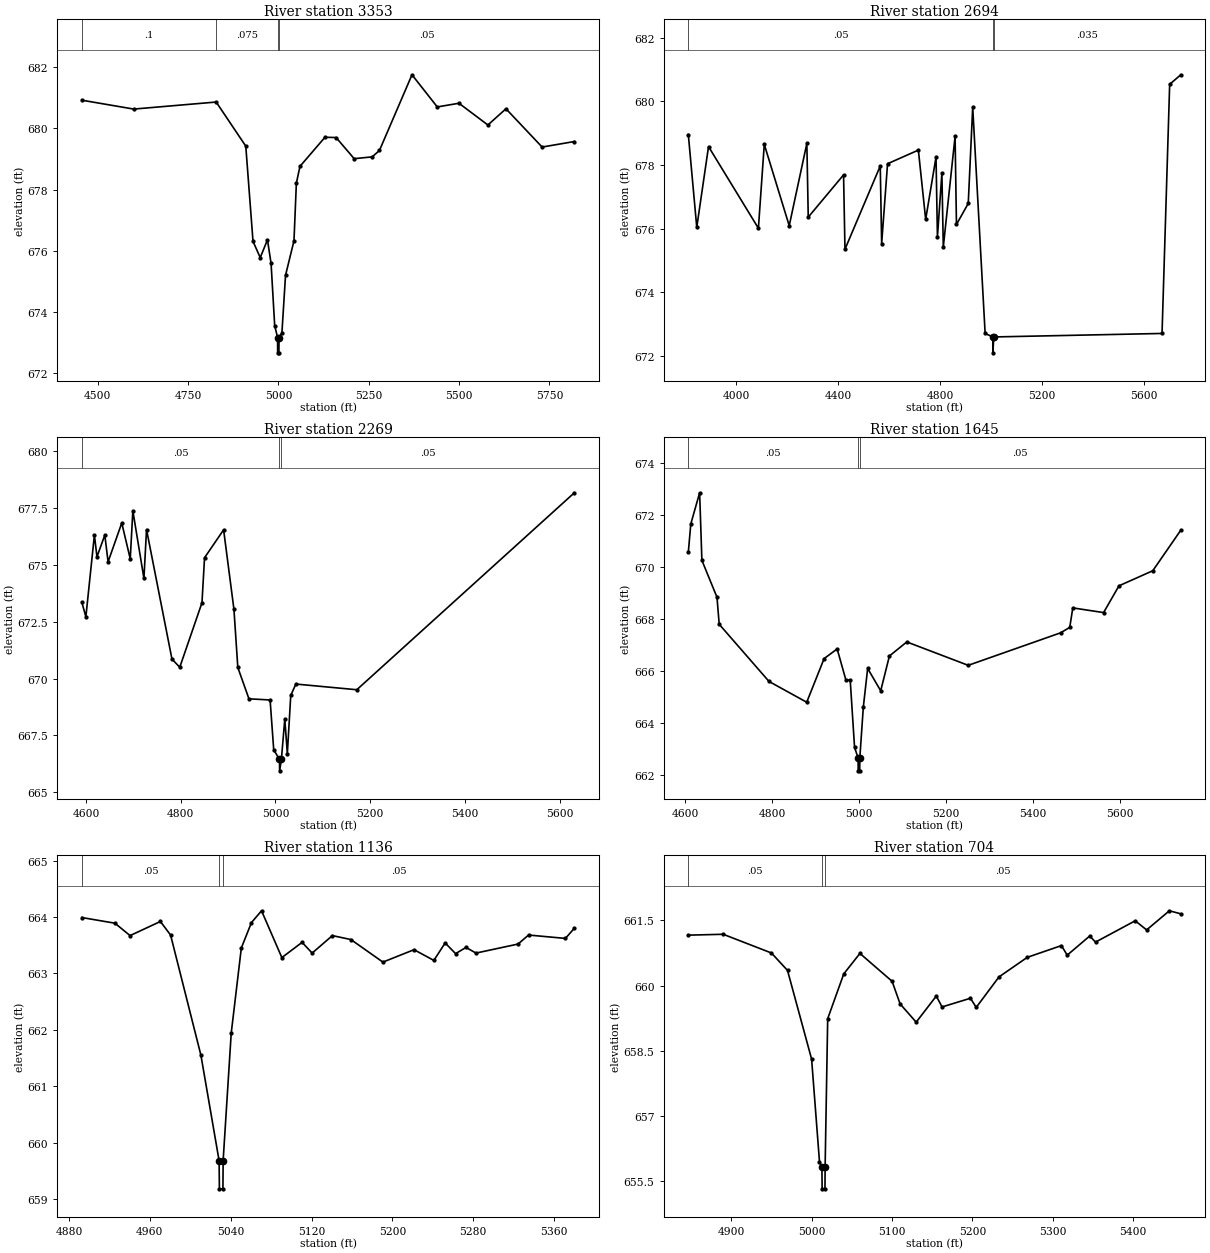
Type RM Length L Ch R = 1 ,3353    ,659,659,659
BEGIN DESCRIPTION:
LWE S 002 4.0
END DESCRIPTION:
XS GIS Cut Line= 3
      2352956.49      7041083.62      2352965.17      7040406.55
      2352978.19       7039720.8
#Sta/Elev= 30
  4455.8  680.92  4599.4  680.63  4827.6  680.86  4909.5  679.42  4929.5  676.31
  4949.5  675.78  4969.5  676.36  4979.5  675.59  4989.5  673.56  4997.5  673.17
  4997.7  672.67  5001.2  672.67  5001.5  673.17  5009.5  673.32  5019.5   675.2
  5042.9  676.33  5049.5  678.21  5059.5  678.76  5128.7  679.71  5159.5   679.7
  5209.5  679.01  5259.5  679.07  5279.5  679.28  5369.5  681.75  5439.5   680.7
  5499.5  680.82  5579.6  680.11  5629.6  680.64  5729.6  679.39  5818.8  679.57
#Mann= 4 ,-1 , 0
  4455.8      .1       0  4827.6    .075       0  4997.5    .033       0
  5001.5     .05       0
Bank Sta=4997.5,5001.5
XS Rating Curve= 0 ,0
Exp/Cntr=0.3,0.1

Type RM Length L Ch R = 1 ,2694    ,425,425,425
BEGIN DESCRIPTION:
LWE S 002 3.5
END DESCRIPTION:
XS GIS Cut Line= 3
      2354067.62      7041435.24      2353607.53      7040423.91
      2353213.73      7039705.54
#Sta/Elev= 30
  3813.4  678.96  3846.5  676.04  3892.6  678.58  4088.1  676.01  4111.1  678.65
  4208.9  676.09    4278  678.68  4283.5  676.36  4421.9  677.69  4427.4  675.35
  4565.7  677.97  4571.2  675.53  4594.3  678.04  4715.1  678.47  4743.7  676.29
  4784.3  678.25  4789.8  675.74  4807.3  677.74  4812.8  675.42    4859   678.9
  4864.4  676.13  4910.6  676.79  4928.1  679.82  4976.8   672.7  5006.8  672.59
    5007  672.09  5010.8  672.59  5670.2   672.7  5700.1  680.54  5743.7  680.84
#Mann= 3 ,-1 , 0
  3813.4     .05       0  5006.8    .033       0  5010.8    .035       0
Bank Sta=5006.8,5010.8
XS Rating Curve= 0 ,0
Exp/Cntr=0.3,0.1

Type RM Length L Ch R = 1 ,2269    ,624,624,624
BEGIN DESCRIPTION:
LWE S 002 3.0
END DESCRIPTION:
XS GIS Cut Line= 3
      2354106.66       7040584.5      2353915.69      7040146.14
      2353694.33      7039629.63
#Sta/Elev= 30
  4591.2  673.36  4599.7  672.72  4617.7  676.32  4623.1  675.36  4639.7  676.32
  4646.6  675.14  4675.5  676.85  4693.4  675.27  4698.9  677.39  4722.3  674.41
  4727.8  676.56  4781.5  670.86    4798   670.5  4844.9  673.34  4850.3  675.32
  4890.6  676.55  4912.4  673.05  4920.6  670.49  4944.1  669.11  4988.8  669.06
  4996.4  666.87  5008.6  666.44  5008.9  665.94  5012.6  666.44  5019.8  668.22
  5025.2   666.7  5032.4  669.26  5043.2  669.76  5171.9  669.51  5631.3  678.18
#Mann= 3 ,-1 , 0
  4591.2     .05       0  5008.6     .05       0  5012.6     .05       0
Bank Sta=5008.6,5012.6
XS Rating Curve= 0 ,0
Exp/Cntr=0.3,0.1

Type RM Length L Ch R = 1 ,1645    ,509,509,509
BEGIN DESCRIPTION:
LWE S 002 2.4
END DESCRIPTION:
XS GIS Cut Line= 4
      2354505.96      7040545.47      2354556.47      7040358.74
      2354545.03      7039920.44       2354189.1      7039568.85
#Sta/Elev= 30
  4607.5  670.56  4613.2  671.65  4633.5  672.85  4638.7  670.25  4673.4  668.83
  4678.5  667.79    4793  665.59  4879.7  664.79  4919.7  666.47  4949.7  666.84
  4969.7  665.65  4979.7  665.64  4989.7  663.05  4997.8  662.65    4998  662.15
  5001.5  662.15  5001.8  662.65  5009.8   664.6  5019.8  666.09  5049.8  665.23
  5069.8  666.57  5109.8  667.11    5251  666.21  5463.2  667.46  5484.4  667.67
  5491.4  668.42  5562.2  668.24  5597.6  669.27  5675.3  669.85  5739.7  671.41
#Mann= 3 ,-1 , 0
  4607.5     .05       0  4997.8    .033       0  5001.8     .05       0
Bank Sta=4997.8,5001.8
XS Rating Curve= 0 ,0
Exp/Cntr=0.3,0.1

Type RM Length L Ch R = 1 ,1136    ,432,432,432
BEGIN DESCRIPTION:
LWE S 002 2.0
END DESCRIPTION:
XS GIS Cut Line= 3
      2355022.46      7040267.68      2355035.49      7039963.84
      2354992.08      7039785.87
#Sta/Elev= 30
  4892.7  663.99  4925.4  663.89  4940.4  663.67  4970.4  663.92  4980.5  663.68
  5010.5  661.55  5028.5  659.68  5028.8  659.18  5032.3  659.18  5032.5  659.68
  5040.5  661.94  5050.5  663.45  5060.5   663.9  5070.5  664.11  5090.6  663.28
  5110.6  663.55  5120.6  663.36  5140.6  663.67  5158.9   663.6  5190.6   663.2
  5221.4  663.42    5241  663.23  5252.2  663.54  5262.5  663.35  5272.8  663.46
  5282.7  663.36  5324.3  663.52  5334.7  663.68  5371.2  663.62    5380   663.8
#Mann= 3 ,-1 , 0
  4892.7     .05       0  5028.5    .033       0  5032.5     .05       0
Bank Sta=5028.5,5032.5
XS Rating Curve= 0 ,0
Exp/Cntr=0.3,0.1

Type RM Length L Ch R = 1 ,704     ,439,439,439
BEGIN DESCRIPTION:
LWE S 002 1.5
END DESCRIPTION:
XS GIS Cut Line= 3
      2355439.13      7040263.36      2355447.81      7039963.84
      2355230.83      7039738.18
#Sta/Elev= 30
  4846.6  661.16    4890  661.18    4950  660.75    4970  660.35    5000  658.31
  5009.8  655.95  5012.8  655.83  5013.1  655.33  5016.6  655.33  5016.8  655.83
    5020  659.24    5040  660.27  5060.1  660.74  5100.1   660.1  5110.1  659.58
  5130.1  659.16  5155.1  659.76  5162.3  659.51  5197.6  659.71  5204.8   659.5
  5233.1   660.2  5268.3  660.65  5310.8  660.92    5318   660.7    5346  661.14
  5353.2     661  5402.6  661.49  5416.8  661.28  5445.1  661.72  5459.3  661.65
#Mann= 3 ,-1 , 0
  4846.6     .05       0  5012.8    .033       0  5016.8     .05       0
Bank Sta=5012.8,5016.8
XS Rating Curve= 0 ,0
Exp/Cntr=0.3,0.1

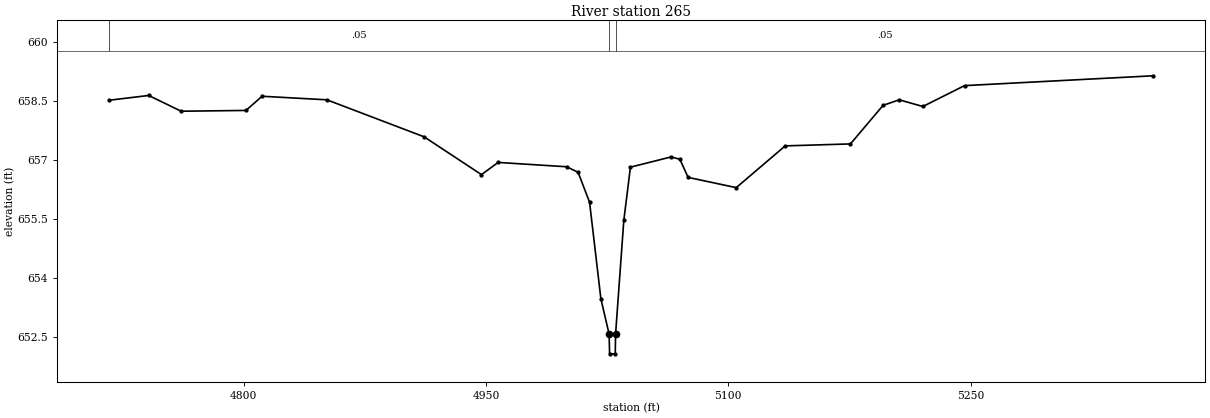
Type RM Length L Ch R = 1 ,265     ,0,0,0
BEGIN DESCRIPTION:
LWE S 002 1.0
END DESCRIPTION:
XS GIS Cut Line= 4
      2355851.46      7040224.23      2355868.82      7039994.23
      2355803.72      7039929.12      2355483.26      7039885.82
#Sta/Elev= 30
  4716.9  658.52  4741.2  658.64  4761.3  658.24  4801.4  658.26  4811.4  658.62
  4851.5  658.53  4911.7  657.59  4947.2  656.63  4957.5  656.94  4999.9  656.83
    5007  656.69  5014.1  655.93  5021.1  653.48  5026.2  652.58  5026.5  652.08
    5030  652.08  5030.2  652.58  5035.3  655.47  5039.4  656.82  5064.6  657.08
    5070  657.02  5075.1  656.56  5104.9   656.3  5135.2  657.36  5175.6  657.41
  5195.8  658.39  5205.8  658.53  5220.4  658.36  5246.2  658.89    5363  659.14
#Mann= 3 ,-1 , 0
  4716.9     .05       0  5026.2    .033       0  5030.2     .05       0
Bank Sta=5026.2,5030.2
XS Rating Curve= 0 ,0
Exp/Cntr=0.3,0.1

Chan Stop Cuts=-1
Use User Specified Reach Order=0
Composite Channel Slope=5