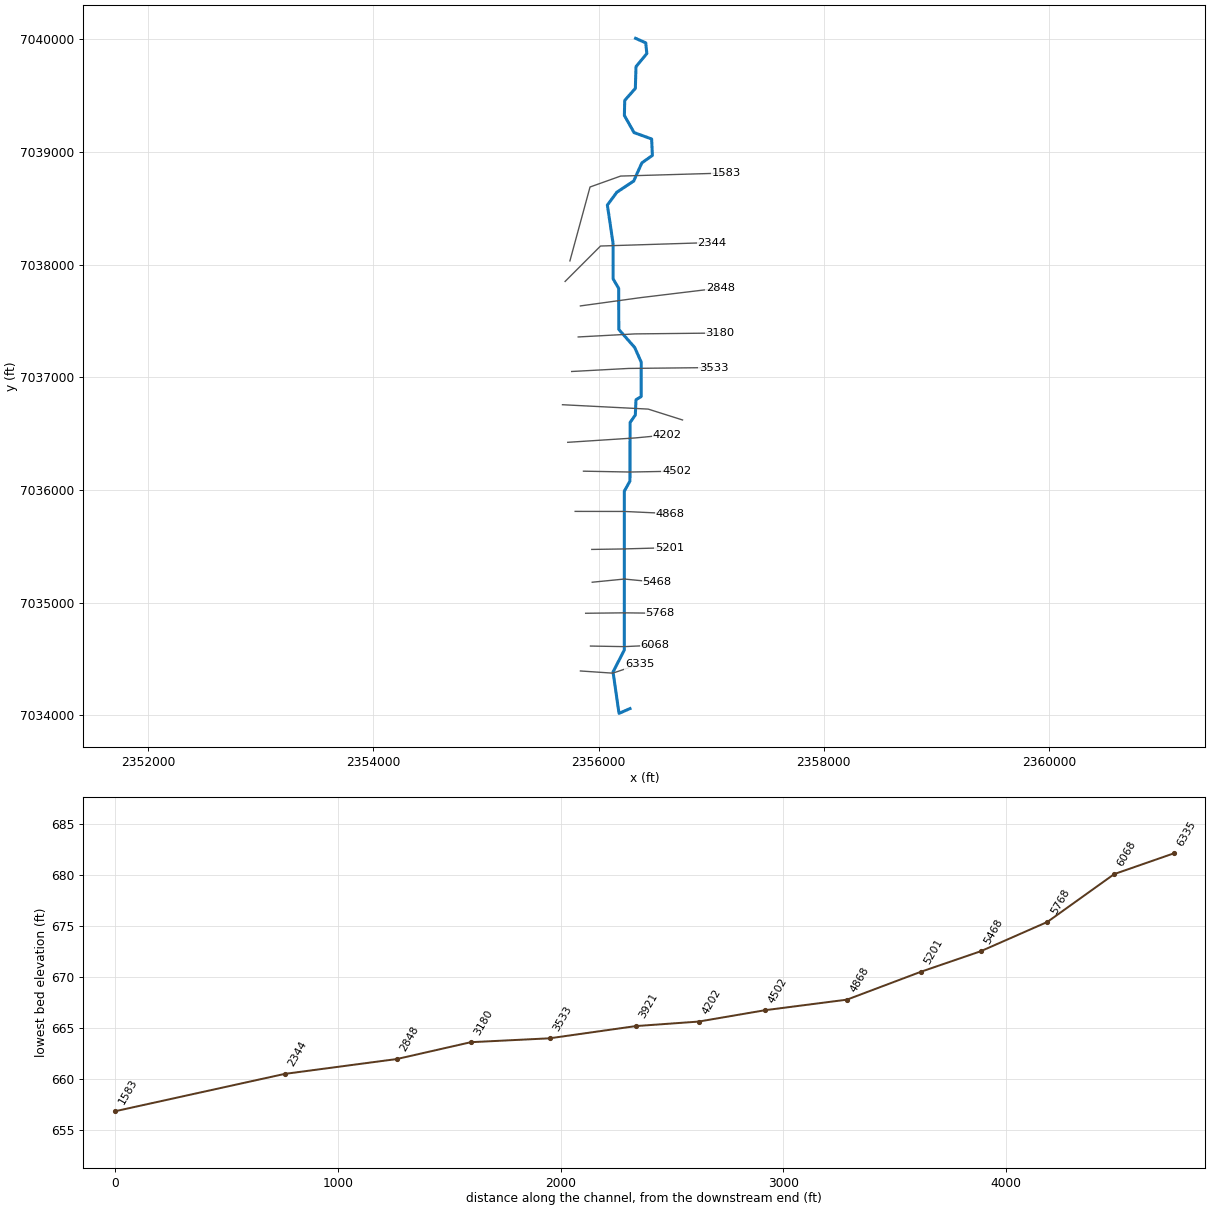
--- LWE S 003.prj (project) ---

Proj Title=LWE S 003 Base Level Engineering
Current Plan=p01
Default Exp/Contr=0.3,0.1
English Units
Geom File=g01
Flow File=f01
Plan File=p01
BEGIN DESCRIPTION:
LWE S 003
END DESCRIPTION:

--- LWE S 003.p01 (plan) ---

Plan Title=Multiple Run
Short Identifier=Multiple
Geom File=g01
Flow File=f01
Subcritical Flow
K Sum by GR= 0
Std Step Tol= 0.01
Critical Tol= 0.01
Num of Std Step Trials= 20
Max Error Tol= 0.3
Flow Tol Ratio= 0.001
Split Flow NTrial= 30
Split Flow Tol= 0.02
Split Flow Ratio= 0.02
Log Output Level= 0
Friction Slope Method= 1
Unsteady Friction Slope Method= 2
Unsteady Bridges Friction Slope Method= 1
Parabolic Critical Depth
Global Vel Dist=  1 , 1 , 1
Global Log Level= 0
CheckData=True
Encroach Param= -1, 0, 0, 0
BEGIN DESCRIPTION:
Multiple Run
END DESCRIPTION:

--- LWE S 003.f01 (steady flow) ---

Flow Title=Multiple
Number of Profiles=7
Profile Names=10-year,25-year,50-year,1pct_min,100-year,1pct_plu,500-year
River Rch & RM= LWE S 003,Reach-1,6335
     626     860    1054     641    1279    2553    1883
River Rch & RM= LWE S 003,Reach-1,4502
     629     863    1057     643    1283    2559    1886
River Rch & RM= LWE S 003,Reach-1,4202
     969    1363    1698    1048    2091    4172    3170
River Rch & RM= LWE S 003,Reach-1,1583
    1057    1492    1860    1149    2293    4576    3484
Boundary for River Rch & Prof#=LWE S 003,Reach-1,1
Up Type=0
Dn Type=3
Dn Slope=0.005
Boundary for River Rch & Prof#=LWE S 003,Reach-1,2
Up Type=0
Dn Type=3
Dn Slope=0.005
Boundary for River Rch & Prof#=LWE S 003,Reach-1,3
Up Type=0
Dn Type=3
Dn Slope=0.005
Boundary for River Rch & Prof#=LWE S 003,Reach-1,4
Up Type=0
Dn Type=3
Dn Slope=0.005
Boundary for River Rch & Prof#=LWE S 003,Reach-1,5
Up Type=0
Dn Type=3
Dn Slope=0.005
Boundary for River Rch & Prof#=LWE S 003,Reach-1,6
Up Type=0
Dn Type=3
Dn Slope=0.005
Boundary for River Rch & Prof#=LWE S 003,Reach-1,7
Up Type=0
Dn Type=3
Dn Slope=0.005

--- LWE S 003.g01 (geometry) ---

Geom Title=Existing Conditions

River Reach=LWE S 003,Reach-1
Reach XY= 30
      2356279.00      7034060.00      2356181.96      7034017.49
      2356128.79      7034385.09      2356228.94      7034580.03
      2356229.07      7035989.97      2356278.93      7036080.03
      2356280.21      7036599.50      2356326.73      7036665.95
      2356332.47      7036801.53      2356378.71      7036830.30
      2356379.21      7037135.09      2356320.84      7037266.05
      2356179.92      7037425.94      2356178.93      7037789.97
      2356129.52      7037875.22      2356128.93      7038189.97
      2356078.57      7038530.18      2356162.29      7038643.36
      2356312.37      7038743.29      2356384.63      7038904.38
      2356478.01      7038970.30      2356471.33      7039116.52
      2356315.34      7039173.26      2356229.49      7039325.22
      2356232.54      7039458.53      2356326.93      7039565.86
      2356332.55      7039758.53      2356428.76      7039875.22
      2356418.83      7039970.10      2356329.00      7040010.00

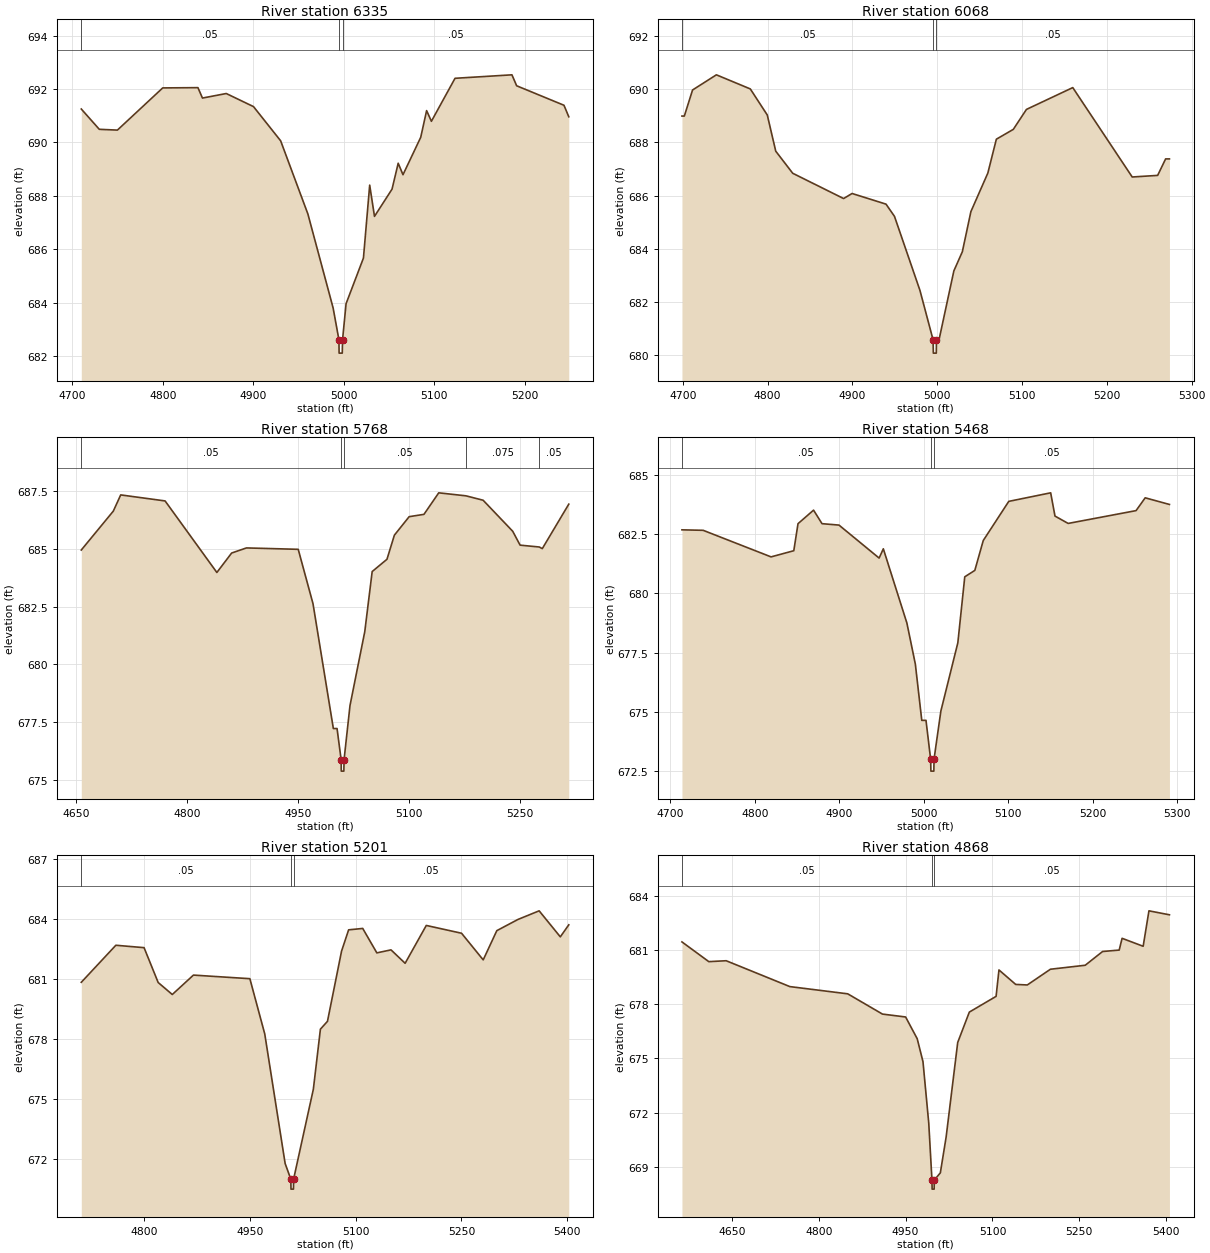
Type RM Length L Ch R = 1,6335,267,267,267
BEGIN DESCRIPTION:
LWE S 003 11.0
END DESCRIPTION:
XS GIS Cut Line= 3
      2355839.17      7034393.95      2356126.37      7034374.54
      2356363.95      7034455.01
#Sta/Elev= 30
  4709.8  691.25  4729.7  690.49  4749.7  690.46  4799.8  692.04  4838.7  692.05
  4843.7  691.66  4870.0  691.83  4900.1  691.34  4930.1  690.06  4960.2  687.32
  4988.1  683.80  4994.5  682.61  4994.7  682.11  4998.2  682.11  4998.5  682.61
  5002.4  683.96  5021.6  685.67  5028.5  688.40  5033.8  687.23  5053.2  688.25
  5060.0  689.22  5065.3  688.79  5084.9  690.19  5091.4  691.19  5096.7  690.79
  5122.8  692.40  5185.7  692.53  5190.9  692.12  5243.2  691.39  5248.5  690.96
#Mann=3,-1,0
  4709.8    0.05       0  4994.5    0.05       0  4998.5    0.05       0
Bank Sta=4994.5,4998.5
Exp/Cntr=0.3,0.1

Type RM Length L Ch R = 1,6068,300,300,300
BEGIN DESCRIPTION:
LWE S 003 10.0
END DESCRIPTION:
XS GIS Cut Line= 3
      2355928.43      7034615.16      2356229.00      7034610.00
      2356502.88      7034622.93
#Sta/Elev= 30
  4699.0  688.99  4701.8  688.99  4711.5  689.97  4739.6  690.54  4779.6  690.01
  4799.6  689.03  4809.6  687.67  4829.6  686.84  4889.6  685.89  4899.6  686.08
  4939.6  685.68  4949.6  685.22  4979.6  682.44  4995.1  680.58  4995.4  680.08
  4998.9  680.08  4999.1  680.58  5002.1  680.58  5019.6  683.17  5029.6  683.89
  5039.7  685.40  5059.7  686.85  5069.7  688.12  5089.7  688.49  5105.2  689.24
  5159.8  690.06  5229.9  686.70  5259.9  686.76  5269.3  687.38  5273.8  687.38
#Mann=3,-1,0
  4699.0    0.05       0  4995.1    0.05       0  4999.1    0.05       0
Bank Sta=4995.1,4999.1
Exp/Cntr=0.3,0.1

Type RM Length L Ch R = 1,5768,300,300,300
BEGIN DESCRIPTION:
LWE S 003 9.0
END DESCRIPTION:
XS GIS Cut Line= 3
      2355885.73      7034906.24      2356229.00      7034910.00
      2356544.79      7034906.25
#Sta/Elev= 30
  4656.7  684.94  4700.0  686.62  4710.0  687.32  4770.0  687.06  4840.0  683.97
  4860.0  684.81  4880.0  685.03  4950.0  684.97  4970.0  682.62  4997.5  677.23
  5002.5  677.23  5008.0  675.89  5008.2  675.39  5011.7  675.39  5012.0  675.89
  5020.0  678.22  5040.0  681.42  5050.0  684.01  5070.0  684.54  5080.0  685.58
  5100.0  686.38  5120.0  686.48  5140.0  687.41  5176.8  687.28  5200.0  687.09
  5240.0  685.75  5250.0  685.15  5275.9  685.07  5280.0  685.00  5315.8  686.92
#Mann=5,-1,0
  4656.7    0.05       0  5008.0    0.05       0  5012.0    0.05       0
  5176.8   0.075       0  5275.9    0.05       0
Bank Sta=5008,5012
Exp/Cntr=0.3,0.1

Type RM Length L Ch R = 1,5468,267,267,267
BEGIN DESCRIPTION:
LWE S 003 8.0
END DESCRIPTION:
XS GIS Cut Line= 3
      2355944.00      7035181.79      2356229.00      7035210.00
      2356518.33      7035181.79
#Sta/Elev= 30
  4713.6  682.68  4738.7  682.66  4819.1  681.54  4846.0  681.80  4851.0  682.94
  4869.4  683.51  4879.4  682.94  4899.5  682.88  4947.0  681.49  4952.0  681.88
  4979.9  678.75  4989.9  677.02  4997.5  674.65  5002.5  674.65  5008.0  673.01
  5008.3  672.51  5011.8  672.51  5012.0  673.01  5020.1  675.04  5040.2  677.92
  5048.4  680.70  5060.3  680.97  5070.3  682.23  5100.5  683.88  5150.1  684.24
  5155.2  683.26  5170.8  682.95  5251.2  683.49  5262.0  684.03  5290.7  683.75
#Mann=3,-1,0
  4713.6    0.05       0  5008.0    0.05       0  5012.0    0.05       0
Bank Sta=5008,5012
Exp/Cntr=0.3,0.1

Type RM Length L Ch R = 1,5201,333,333,333
BEGIN DESCRIPTION:
LWE S 003 7.0
END DESCRIPTION:
XS GIS Cut Line= 3
      2355940.04      7035472.87      2356200.11      7035476.75
      2356630.95      7035488.39
#Sta/Elev= 30
  4711.0  680.84  4760.0  682.69  4800.0  682.57  4820.0  680.83  4840.0  680.23
  4870.0  681.20  4950.0  681.02  4971.1  678.26  5000.0  671.79  5008.0  671.01
  5008.3  670.51  5011.8  670.51  5012.0  671.01  5040.0  675.50  5050.0  678.50
  5060.0  678.89  5080.0  682.40  5090.0  683.46  5110.0  683.53  5130.0  682.31
  5150.1  682.46  5170.1  681.79  5200.1  683.68  5250.1  683.29  5280.8  681.96
  5300.1  683.42  5330.1  683.98  5360.1  684.41  5390.1  683.11  5402.1  683.71
#Mann=3,-1,0
  4711.0    0.05       0  5008.0    0.05       0  5012.0    0.05       0
Bank Sta=5008,5012
Exp/Cntr=0.3,0.1

Type RM Length L Ch R = 1,4868,366,366,366
BEGIN DESCRIPTION:
LWE S 003 6.0
END DESCRIPTION:
XS GIS Cut Line= 3
      2355792.59      7035810.52      2356229.00      7035810.00
      2356634.36      7035791.13
#Sta/Elev= 30
  4563.6  681.44  4610.0  680.35  4640.0  680.40  4750.0  678.97  4850.0  678.57
  4910.0  677.45  4950.0  677.29  4970.0  676.09  4980.0  674.82  4990.0  671.41
  4995.5  668.27  4995.8  667.77  4999.3  667.77  4999.5  668.27  5010.0  668.67
  5020.0  670.65  5040.0  675.88  5060.1  677.56  5106.3  678.43  5111.3  679.89
  5140.2  679.09  5160.2  679.06  5200.2  679.93  5260.3  680.15  5290.3  680.91
  5319.0  680.99  5324.0  681.64  5360.4  681.20  5370.4  683.16  5405.8  682.94
#Mann=3,-1,0
  4563.6    0.05       0  4995.5    0.05       0  4999.5    0.05       0
Bank Sta=4995.5,4999.5
Exp/Cntr=0.3,0.1

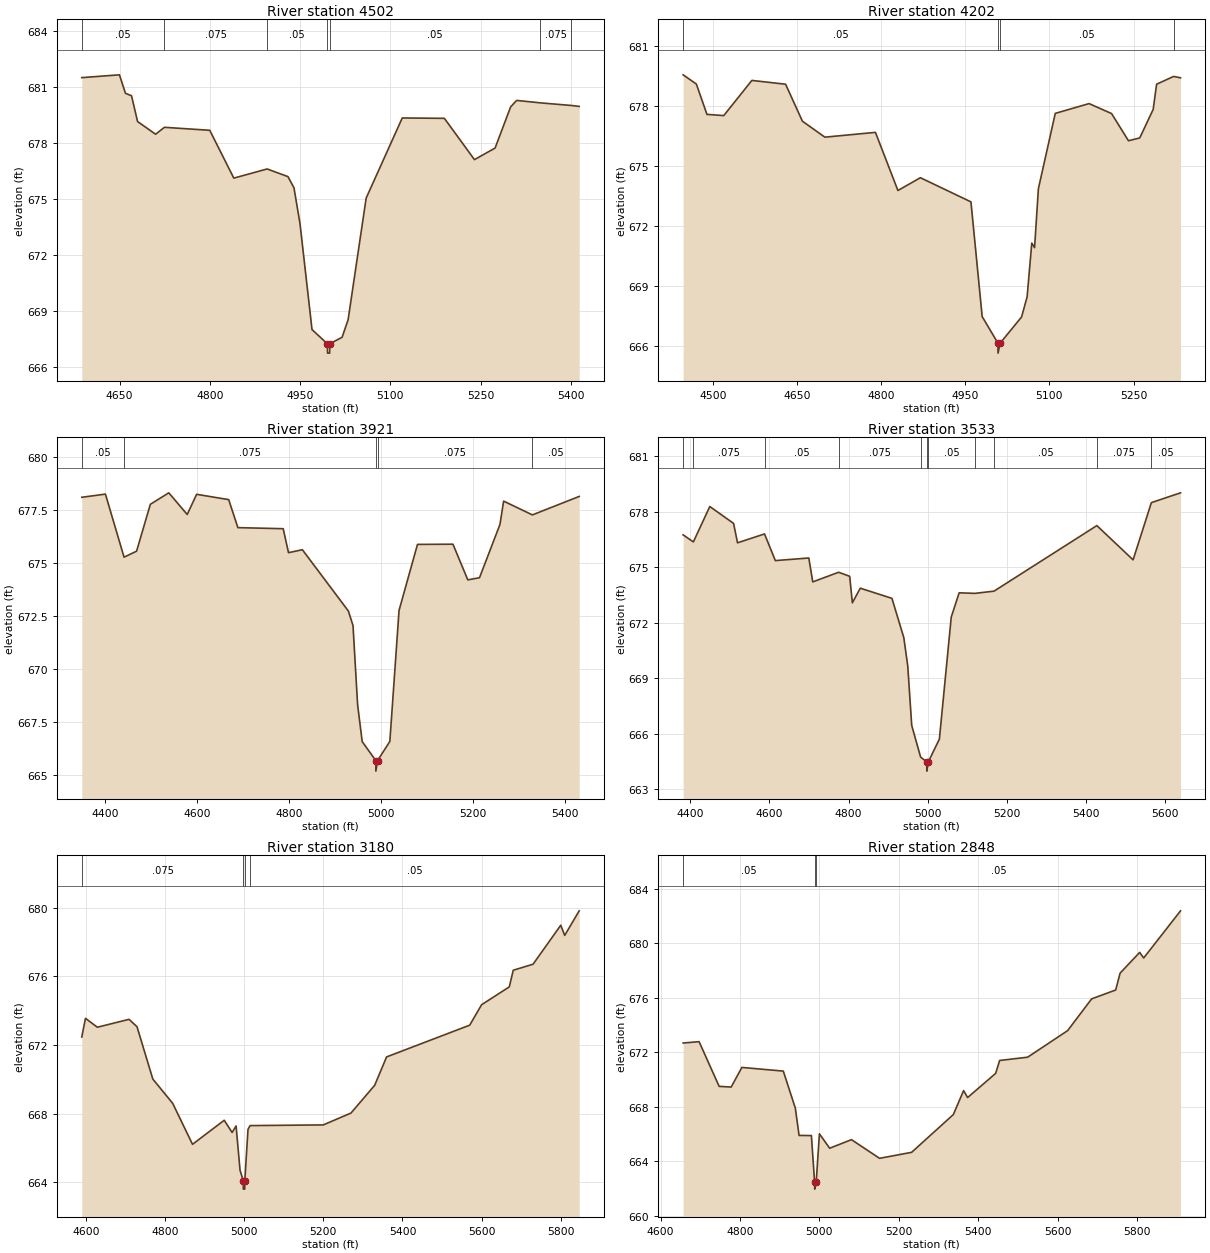
Type RM Length L Ch R = 1,4502,300,300,300
BEGIN DESCRIPTION:
LWE S 003 5.0
END DESCRIPTION:
XS GIS Cut Line= 3
      2355866.36      7036167.57      2356279.00      7036160.00
      2356693.02      7036167.57
#Sta/Elev= 30
  4587.2  681.49  4649.8  681.64  4659.8  680.65  4669.9  680.52  4679.9  679.14
  4709.9  678.46  4724.6  678.83  4799.9  678.67  4839.9  676.11  4895.3  676.60
  4929.9  676.19  4939.9  675.59  4949.9  673.68  4969.9  668.00  4995.4  667.24
  4995.7  666.74  4999.2  666.74  4999.4  667.24  5019.9  667.59  5029.9  668.53
  5059.9  675.04  5119.9  679.33  5189.9  679.31  5239.9  677.10  5274.2  677.72
  5300.0  679.92  5310.0  680.27  5349.1  680.14  5400.6  680.00  5414.0  679.95
#Mann=7,-1,0
  4587.2    0.05       0  4724.6   0.075       0  4895.3    0.05       0
  4995.4   0.033       0  4999.4    0.05       0  5349.1   0.075       0
  5400.6    0.05       0
Bank Sta=4995.4,4999.4
Exp/Cntr=0.3,0.1

Type RM Length L Ch R = 1,4202,281,281,281
BEGIN DESCRIPTION:
LWE S 003 4.0
END DESCRIPTION:
XS GIS Cut Line= 3
      2355726.63      7036423.72      2356324.31      7036462.53
      2356611.48      7036489.69
#Sta/Elev= 30
  4446.5  679.55  4470.1  679.09  4489.0  677.57  4519.0  677.51  4569.1  679.27
  4629.3  679.08  4659.3  677.23  4699.4  676.43  4789.6  676.67  4829.7  673.76
  4869.8  674.40  4960.0  673.19  4980.0  667.45  5008.1  666.12  5008.3  665.62
  5012.1  666.12  5050.3  667.43  5060.2  668.44  5068.5  671.13  5073.5  670.90
  5080.3  673.85  5110.4  677.62  5170.7  678.11  5210.9  677.61  5241.0  676.25
  5261.1  676.39  5285.1  677.82  5291.2  679.08  5321.6  679.47  5333.9  679.40
#Mann=4,-1,0
  4446.5    0.05       0  5008.1   0.033       0  5012.1    0.05       0
  5321.6   0.075       0
Bank Sta=5008.1,5012.1
Exp/Cntr=0.3,0.1

Type RM Length L Ch R = 1,3921,388,388,388
BEGIN DESCRIPTION:
LWE S 003 3.0
END DESCRIPTION:
XS GIS Cut Line= 3
      2355680.05      7036757.49      2356440.74      7036718.68
      2356745.65      7036622.18
#Sta/Elev= 30
  4350.1  678.08  4401.5  678.23  4442.0  675.26  4469.2  675.54  4499.2  677.75
  4539.3  678.29  4579.3  677.27  4599.8  678.22  4669.5  677.97  4689.5  676.65
  4788.0  676.60  4799.6  675.47  4829.7  675.61  4929.8  672.72  4939.8  672.04
  4949.8  668.31  4959.8  666.57  4989.3  665.68  4989.5  665.18  4993.3  665.68
  5019.9  666.58  5039.9  672.75  5080.0  675.86  5157.1  675.87  5189.4  674.19
  5214.8  674.29  5259.3  676.80  5267.3  677.90  5329.8  677.25  5431.6  678.12
#Mann=5,-1,0
  4350.1    0.05       0  4442.0   0.075       0  4989.3    0.07       0
  4993.3   0.075       0  5329.8    0.05       0
Bank Sta=4989.3,4993.3
Exp/Cntr=0.3,0.1

Type RM Length L Ch R = 1,3533,353,353,353
BEGIN DESCRIPTION:
LWE S 003 2.5
END DESCRIPTION:
XS GIS Cut Line= 3
      2355761.55      7037052.44      2356266.09      7037079.61
      2357018.98      7037087.37
#Sta/Elev= 30
  4381.6  676.74  4407.5  676.36  4449.1  678.27  4509.2  677.36  4519.2  676.31
  4587.5  676.79  4614.8  675.35  4699.5  675.49  4709.5  674.20  4775.0  674.72
  4802.9  674.50  4809.7  673.07  4829.7  673.86  4909.8  673.31  4939.8  671.19
  4949.8  669.66  4959.8  666.45  4982.3  664.74  4997.8  664.48  4998.0  663.98
  5001.8  664.48  5029.8  665.71  5059.8  672.30  5079.8  673.61  5119.5  673.58
  5168.0  673.70  5428.1  677.24  5519.8  675.39  5566.0  678.48  5639.8  679.01
#Mann=11,-1,0
  4381.6    0.05       0  4407.5   0.075       0  4587.5    0.05       0
  4775.0   0.075       0  4982.3    0.05       0  4997.8    0.05       0
  5001.8    0.05       0  5119.5   0.075       0  5168.0    0.05       0
  5428.1   0.075       0  5566.0    0.05       0
Bank Sta=4997.8,5001.8
Exp/Cntr=0.3,0.1

Type RM Length L Ch R = 1,3180,332,332,332
BEGIN DESCRIPTION:
LWE S 003 2.0
END DESCRIPTION:
XS GIS Cut Line= 3
      2355819.74      7037359.04      2356324.31      7037386.21
      2357075.57      7037393.96
#Sta/Elev= 30
  4589.9  672.46  4599.2  673.55  4629.2  673.03  4709.3  673.49  4729.4  673.06
  4769.4  670.01  4819.5  668.60  4869.6  666.21  4949.7  667.61  4969.7  666.90
  4979.7  667.28  4989.7  664.70  4997.8  664.10  4998.0  663.60  5001.5  663.60
  5001.8  664.10  5009.8  667.08  5015.1  667.30  5199.9  667.34  5269.9  668.03
  5329.9  669.65  5359.9  671.30  5569.9  673.15  5599.9  674.34  5669.9  675.38
  5679.9  676.35  5729.9  676.70  5799.9  678.97  5809.9  678.38  5846.5  679.81
#Mann=4,-1,0
  4589.9   0.075       0  4997.8    0.07       0  5001.8   0.075       0
  5015.1    0.05       0
Bank Sta=4997.8,5001.8
Exp/Cntr=0.3,0.1

Type RM Length L Ch R = 1,2848,504,504,504
BEGIN DESCRIPTION:
LWE S 003 1.0
END DESCRIPTION:
XS GIS Cut Line= 3
      2355839.14      7037634.59      2356374.76      7037708.33
      2357081.15      7037793.72
#Sta/Elev= 30
  4656.9  672.67  4697.1  672.77  4747.6  669.49  4777.9  669.44  4804.8  670.88
  4909.1  670.61  4939.4  667.89  4948.8  665.89  4979.8  665.88  4987.9  662.45
  4988.1  661.95  4991.9  662.45  5000.0  666.01  5025.8  664.95  5080.7  665.58
  5151.4  664.21  5232.1  664.65  5337.1  667.42  5363.0  669.18  5373.1  668.67
  5443.6  670.44  5453.7  671.39  5524.2  671.63  5624.9  673.58  5685.3  675.91
  5745.8  676.56  5757.0  677.80  5806.2  679.32  5816.3  678.91  5909.1  682.37
#Mann=3,-1,0
  4656.9    0.05       0  4987.9    0.05       0  4991.9    0.05       0
Bank Sta=4987.9,4991.9
Exp/Cntr=0.3,0.1

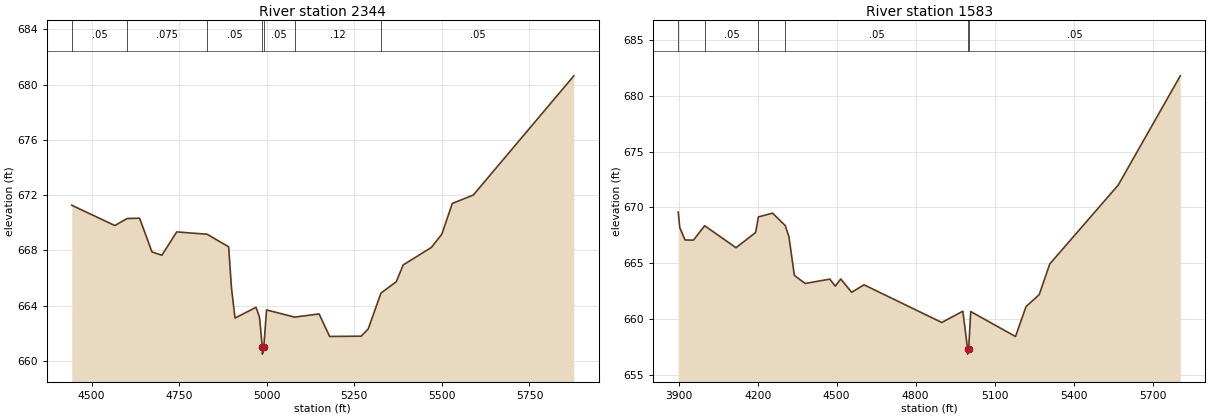
Type RM Length L Ch R = 1,2344,761,761,761
BEGIN DESCRIPTION:
LWE S 003 0.7
END DESCRIPTION:
XS GIS Cut Line= 3
      2355703.32      7037851.91      2356017.71      7038166.30
      2357005.72      7038197.29
#Sta/Elev= 30
  4443.6  671.27  4566.5  669.80  4601.8  670.31  4637.2  670.33  4672.5  667.89
  4700.8  667.65  4743.2  669.34  4830.0  669.17  4891.4  668.26  4899.5  665.27
  4909.5  663.10  4969.5  663.88  4979.5  663.16  4987.5  660.99  4987.8  660.49
  4991.6  660.99  4999.6  663.69  5079.7  663.17  5149.6  663.40  5179.6  661.77
  5269.7  661.79  5289.7  662.31  5326.2  664.91  5369.7  665.73  5389.7  666.95
  5469.8  668.21  5499.8  669.17  5529.8  671.40  5589.8  672.01  5876.7  680.64
#Mann=7,-1,0
  4443.6    0.05       0  4601.8   0.075       0  4830.0    0.05       0
  4987.5    0.05       0  4991.6    0.05       0  5079.7    0.12       0
  5326.2    0.05       0
Bank Sta=4987.5,4991.6
Exp/Cntr=0.3,0.1

Type RM Length L Ch R = 1,1583,0,0,0
BEGIN DESCRIPTION:
LWE S 003 0.5
END DESCRIPTION:
XS GIS Cut Line= 4
      2355746.03      7038034.32      2355924.56      7038690.23
      2356196.23      7038787.26      2357134.69      7038814.40
#Sta/Elev= 30
  3898.3  669.57  3904.2  668.18  3924.2  667.07  3956.0  667.06  3998.6  668.35
  4117.8  666.38  4192.2  667.74  4202.8  669.14  4256.6  669.48  4304.9  668.36
  4318.7  667.38  4339.5  663.89  4380.6  663.17  4474.2  663.56  4494.8  662.93
  4515.6  663.57  4557.1  662.38  4604.0  663.05  4899.3  659.67  4979.4  660.68
  4997.2  657.33  4997.6  656.83  5001.5  657.33  5009.4  660.65  5179.4  658.41
  5219.5  661.10  5269.5  662.17  5309.5  664.92  5569.6  672.00  5805.4  681.80
#Mann=6,-1,0
  3898.3   0.075       0  3998.6    0.05       0  4202.8   0.075       0
  4304.9    0.05       0  4997.2   0.033       0  5001.5    0.05       0
Bank Sta=4997.2,5001.5
Exp/Cntr=0.3,0.1

Chan Stop Cuts=-1