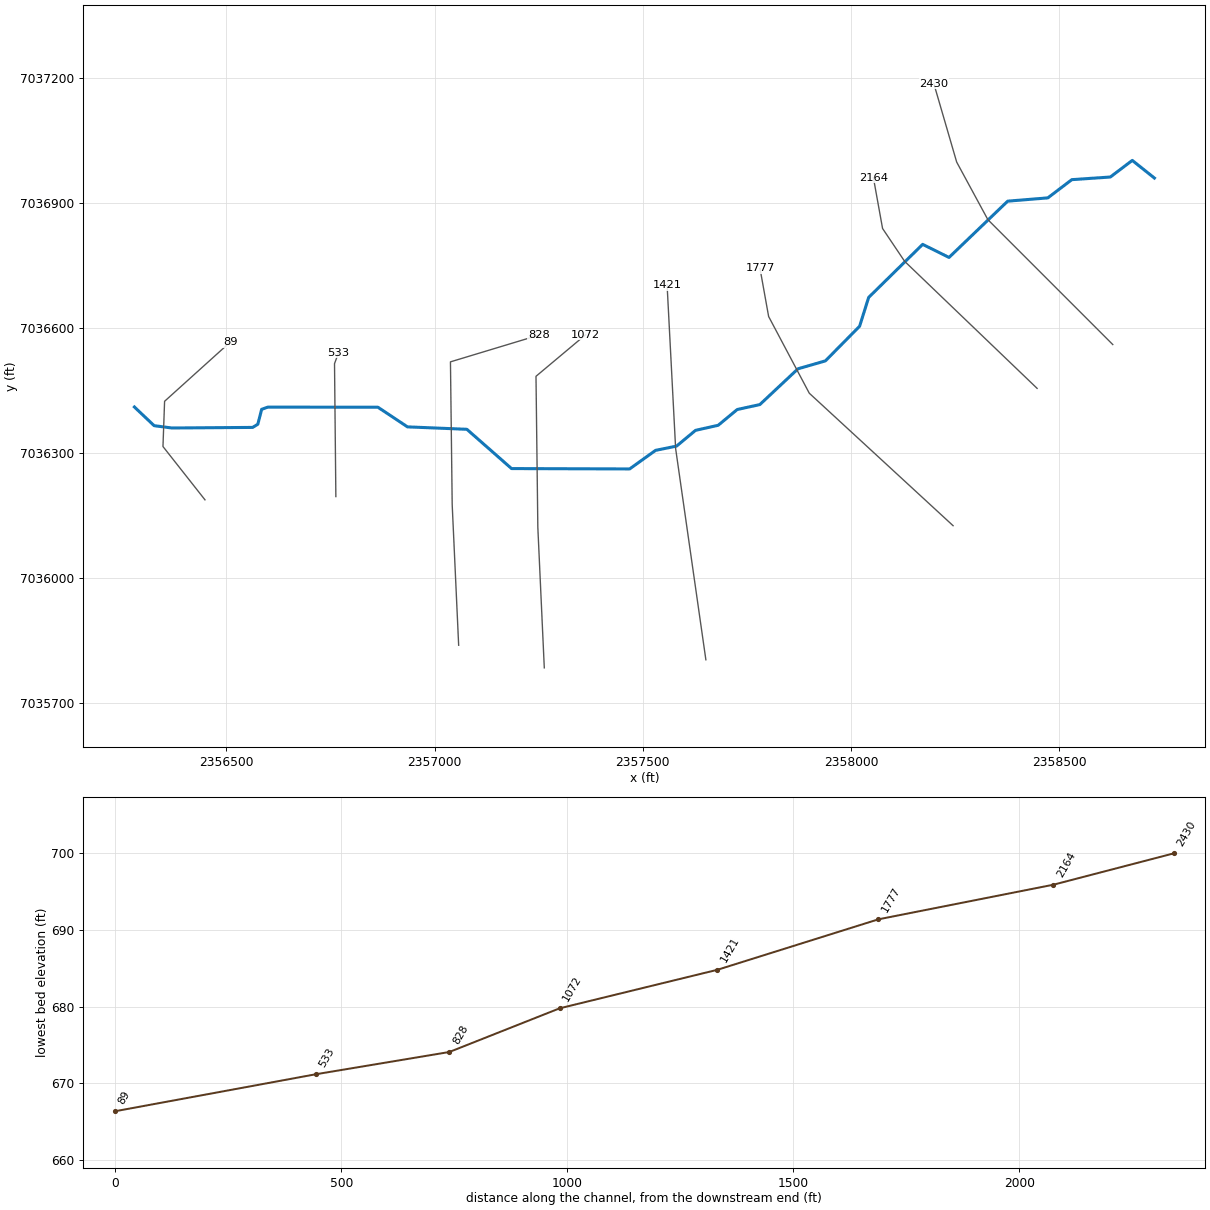
--- LWE S 004.prj (project) ---

Proj Title=LWE S 004 Base Level Engineering
Current Plan=p01
Default Exp/Contr=0.3,0.1
English Units
Geom File=g01
Flow File=f01
Plan File=p01
Y Axis Title=Elevation
X Axis Title(PF)=Main Channel Distance
X Axis Title(XS)=Station
BEGIN DESCRIPTION:
LWE S 004
END DESCRIPTION:
DSS Export Rating Curves= 0
DSS Export Rating Curve Sorted= 0
DSS Export Volume Flow Curves= 0
DXF OffsetX= 0
DXF OffsetY= 0
DXF ScaleX= 1
DXF ScaleY= 10

--- LWE S 004.p01 (plan) ---

Plan Title=Multiple Run
Program Version=4.10
Short Identifier=Multiple
Geom File=g01
Flow File=f01
Subcritical Flow
K Sum by GR= 0
Std Step Tol= 0.01
Critical Tol= 0.01
Num of Std Step Trials= 20
Max Error Tol= 0.3
Flow Tol Ratio= 0.001
Split Flow NTrial= 30
Split Flow Tol= 0.02
Split Flow Ratio= 0.02
Log Output Level= 0
Friction Slope Method= 1
Unsteady Friction Slope Method= 2
Unsteady Bridges Friction Slope Method= 1
Parabolic Critical Depth
Global Vel Dist= 1 , 1 , 1
Global Log Level= 0
CheckData=True
Encroach Param=-1 ,0,0, 0
BEGIN DESCRIPTION:
Multiple Run
END DESCRIPTION:
Computation Interval=1HOUR
Output Interval=1HOUR
Run HTab= 0
Run UNet= 0
Run PostProcess= 0
Run WQNet= 0
UNET Theta= 1
UNET Theta Warmup= 1
UNET ZTol= 0.02
UNET ZSATol= 0.05
UNET MxIter= 20
UNET MaxInSteps= 0
UNET DtIC= 0
UNET DtMin= 0
UNET MaxCRTS= 20
UNET WFStab= 2
UNET SFStab= 1
UNET WFX= 1
UNET SFX= 1
UNET DSS MLevel= 4
UNET DZMax Abort= 100
UNET Convert EG Bridges= 0
UNET Use Existing IB Tables=-1
UNET Froude Reduction=False
UNET Froude Limit= 1
UNET Froude Power= 10
UNET Time Slicing=0,0, 5
UNET Junction Losses=0
Instantaneous Interval=1HOUR
Write IC File= 0
Write IC File at Sim End=0
Echo Input=False
Echo Parameters=False
Echo Output=False
Write Detailed= 0
WQ AD Non Conservative
WQ ULTIMATE=-1
WQ Max Comp Step=1HOUR
WQ Output Interval=15MIN
WQ Output Selected Increments= 0
WQ Output face flow=0
WQ Output face velocity=0
WQ Output face area=0
WQ Output face dispersion=0
WQ Output cell volume=0
WQ Output cell surface area=0
WQ Output cell continuity=0
WQ Output cumulative cell continuity=0
WQ Output face conc=0
WQ Output face dconc_dx=0
WQ Output face courant=0
WQ Output face peclet=0
WQ Output face adv mass=0
WQ Output face disp mass=0
WQ Output cell mass=0
WQ Output cell source sink temp=0
WQ Output cell source sink nsm=0
WQ Output MaxMinRange=-1
WQ Daily Max Min Mean=-1
WQ Daily Range=0
WQ Daily Time=0
WQ Create Restart=0
WQ Fixed Restart=0
WQ System Summary=0
WQ Use Fixed Temperature=0
Sorting and Armoring Iterations= 10
XS Update Threshold= 0.02
Hydraulics Update Threshold= 0.02
Energy Slope Method= 1
Volume Change Method= 0
XS Weighting Method= 0
Number of US Weighted Cross Sections= 1
Number of DS Weighted Cross Sections= 1
Upstream XS Weight=0.25
Main XS Weight=0.5
Downstream XS Weight=0.25
Number of DS XS's Weighted with US Boundary= 1
Upstream Boundary Weight= 1
Weight of XSs Associated with US Boundary= 0
Number of US XS's Weighted with DS Boundary= 1
Downstream Boundary Weight= 0.5
Weight of XSs Associated with DS Boundary= 0.5
Sediment Output Level= 4
Mass or Volume Output= 0
Output Increment Type= 1
Profile and TS Output Increment= 10
XS Output Flag= 0
XS Output Increment= 10
Disregard all LS=0
Disregard all Conn=0
Disregard all Breaches=0
Disregard all Pumps=0

--- LWE S 004.f01 (steady flow) ---

Flow Title=Multiple
Number of Profiles=7
Profile Names=10-year,25-year,50-year,1pct_min,100-year,1pct_plu,500-year
River Rch & RM= LWE S 004,Reach-1,2430
     508     687     835     504    1005    2006    1455
Boundary for River Rch & Prof#=LWE S 004,Reach-1,1
Up Type=0
Dn Type=3
Dn Slope=0.005
Boundary for River Rch & Prof#=LWE S 004,Reach-1,2
Up Type=0
Dn Type=3
Dn Slope=0.005
Boundary for River Rch & Prof#=LWE S 004,Reach-1,3
Up Type=0
Dn Type=3
Dn Slope=0.005
Boundary for River Rch & Prof#=LWE S 004,Reach-1,4
Up Type=0
Dn Type=3
Dn Slope=0.005
Boundary for River Rch & Prof#=LWE S 004,Reach-1,5
Up Type=0
Dn Type=3
Dn Slope=0.005
Boundary for River Rch & Prof#=LWE S 004,Reach-1,6
Up Type=0
Dn Type=3
Dn Slope=0.005
Boundary for River Rch & Prof#=LWE S 004,Reach-1,7
Up Type=0
Dn Type=3
Dn Slope=0.005

--- LWE S 004.g01 (geometry) ---

Geom Title=Existing Conditions
Program Version=4.10

River Reach=LWE S 004       ,Reach-1
Reach XY= 30
        2358729.        7036960.      2358675.82      7037002.37
      2358623.12      7036962.46       2358530.6      7036956.15
      2358473.02      7036912.36      2358376.57      7036904.48
      2358235.67       7036769.3      2358172.33       7036800.7
      2358042.63      7036673.21      2358020.85      7036603.93
       2357938.7      7036520.77      2357872.96      7036501.82
      2357781.29      7036415.85      2357726.81       7036403.9
       2357681.2      7036366.08       2357626.8      7036353.92
       2357581.2      7036316.08      2357530.74      7036305.81
       2357468.5       7036261.2      2357184.86      7036262.07
      2357077.53      7036356.44      2356934.94      7036362.27
      2356863.78      7036409.48       2356599.3       7036409.7
      2356584.62      7036404.38      2356575.42      7036368.58
      2356563.04      7036360.96      2356368.83      7036359.58
      2356326.41      7036365.14        2356279.        7036410.

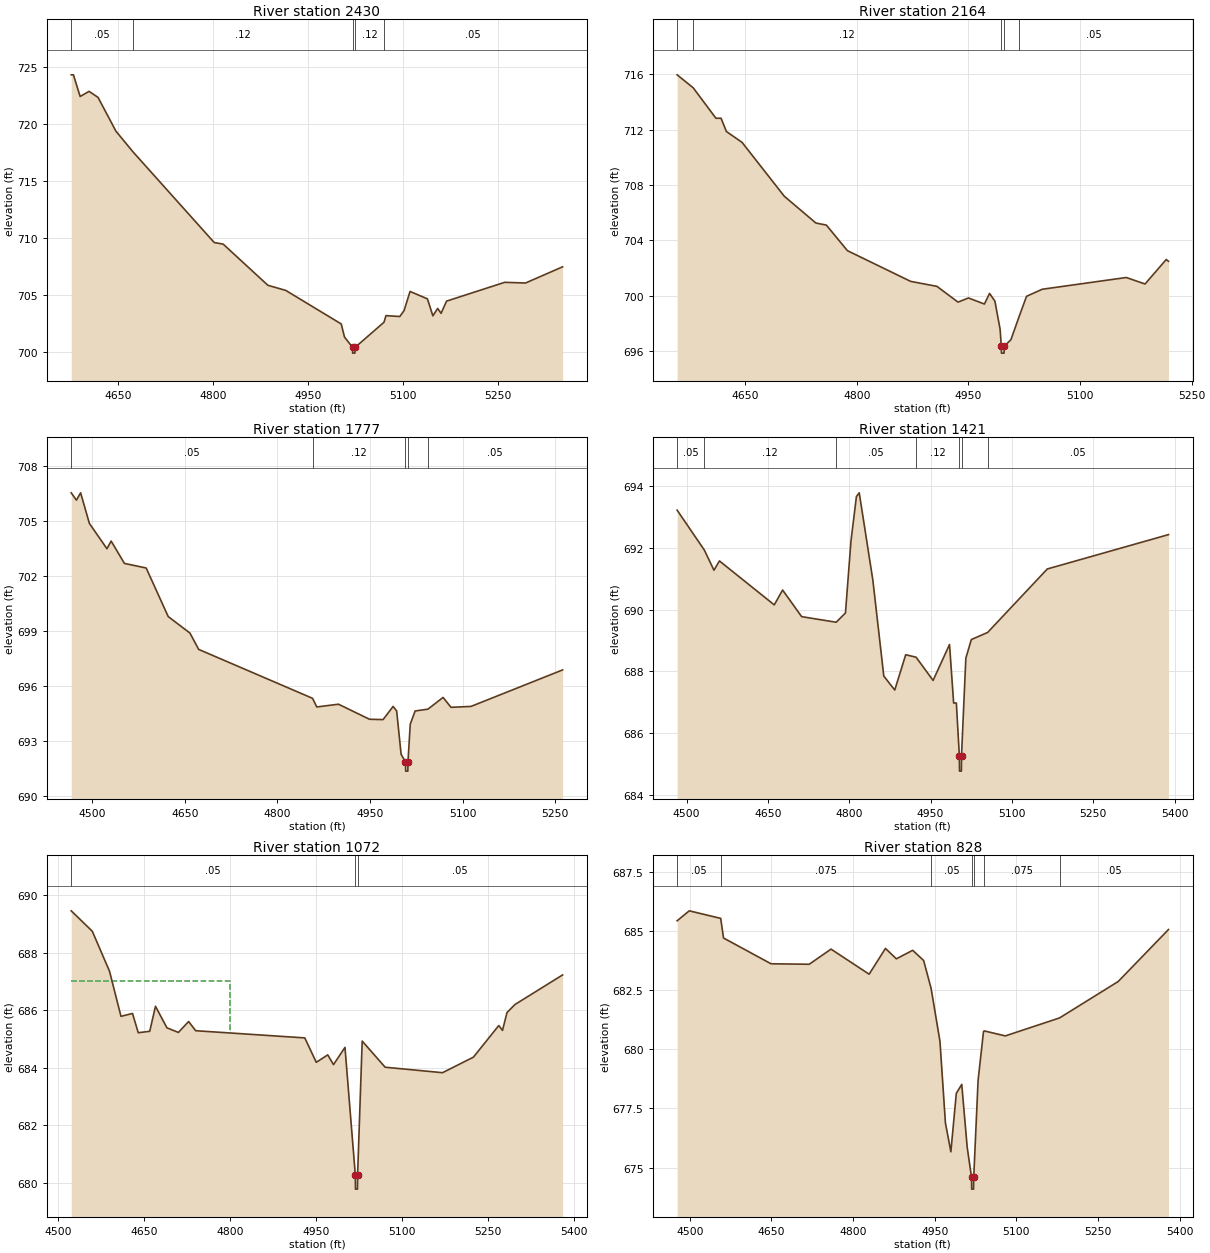
Type RM Length L Ch R = 1 ,2430    ,266,266,266
BEGIN DESCRIPTION:
LWE S 004 6.0
END DESCRIPTION:
XS GIS Cut Line= 4
      2358628.97      7036560.03        2358329.        7036860.
      2358254.05      7036998.34      2358199.34      7037186.28
#Sta/Elev= 30
  4575.5  724.32    4579  724.32  4589.6  722.42  4603.7  722.87  4617.9  722.34
  4646.2  719.38  4673.1  717.57  4801.7  709.61  4815.9  709.47  4886.6  705.86
  4914.9  705.41  5002.6  702.47  5007.8  701.32  5020.5  700.41  5020.7  699.91
  5024.2  699.91  5024.5  700.41  5070.3  702.62  5073.4   703.2  5095.3  703.12
  5102.1  703.65  5111.5  705.32    5139  704.67  5147.6  703.18  5155.2  703.83
  5160.6   703.4  5169.2  704.47  5261.2  706.12  5294.2  706.06  5352.8  707.48
#Mann= 5 ,-1 , 0
  4575.5     .05       0  4673.1     .12       0  5020.5     .07       0
  5024.5     .12       0  5070.3     .05       0
Bank Sta=5020.5,5024.5
XS Rating Curve= 0 ,0
Exp/Cntr=0.3,0.1

Type RM Length L Ch R = 1 ,2164    ,387,387,387
BEGIN DESCRIPTION:
LWE S 004 5.0
END DESCRIPTION:
XS GIS Cut Line= 4
      2358447.22      7036454.77        2358129.        7036760.
      2358076.03      7036838.81      2358053.98      7036961.04
#Sta/Elev= 30
  4558.7  715.97  4580.3  715.03  4610.8  712.83  4617.7  712.83  4624.9  711.87
    4646  711.08  4702.6  707.19  4745.1  705.25  4759.2   705.1  4787.5  703.25
  4872.4  701.03  4907.7  700.67    4936  699.53  4950.1  699.83  4971.5  699.39
  4978.4  700.16  4985.6   699.6  4992.6  697.56  4994.2  696.34  4994.4  695.84
  4997.9  695.84  4998.2  696.34  5007.1  696.81  5017.9  698.45  5028.1  699.95
  5049.2  700.46  5162.1  701.31  5187.3  700.84  5215.7  702.61  5218.8  702.48
#Mann= 5 ,-1 , 0
  4558.7     .05       0  4580.3     .12       0  4994.2     .07       0
  4998.2     .12       0  5017.9     .05       0
Bank Sta=4994.2,4998.2
XS Rating Curve= 0 ,0
Exp/Cntr=0.3,0.1

Type RM Length L Ch R = 1 ,1777    ,356,356,356
BEGIN DESCRIPTION:
LWE S 004 4.0
END DESCRIPTION:
XS GIS Cut Line= 4
      2358245.42      7036124.87        2357900.      7036443.12
      2357802.36      7036627.39      2357781.65      7036742.73
#Sta/Elev= 30
  4466.3  706.52  4474.7  706.12  4481.5  706.52  4495.7  704.85  4524.1  703.47
  4530.9  703.89  4552.4  702.67  4587.6  702.42  4623.3  699.77  4658.5  698.87
  4672.6  697.98    4857  695.31  4863.8  694.84  4898.9  694.99  4949.1  694.17
  4971.1  694.15  4987.4  694.87  4993.1  694.62  5000.3  692.26  5007.4  691.84
  5007.7  691.34  5011.2  691.34  5011.4  691.84  5015.1   693.9    5023  694.62
  5043.7  694.72  5068.2  695.36  5081.1  694.82  5113.5  694.87  5261.7  696.86
#Mann= 5 ,-1 , 0
  4466.3     .05       0    4857     .12       0  5007.4     .07       0
  5011.4     .12       0  5043.7     .05       0
Bank Sta=5007.4,5011.4
XS Rating Curve= 0 ,0
Exp/Cntr=0.3,0.1

Type RM Length L Ch R = 1 ,1421    ,349,349,349
BEGIN DESCRIPTION:
LWE S 004 3.0
END DESCRIPTION:
XS GIS Cut Line= 3
      2357651.61      7035802.76        2357579.        7036310.
      2357558.47      7036703.15
#Sta/Elev= 30
  4482.7  693.21  4532.9  691.92  4550.6  691.27  4560.7  691.57  4661.8  690.15
  4677.2  690.63  4712.3  689.77    4776  689.59  4793.1  689.89  4803.2   692.2
  4813.3  693.65  4818.5  693.77  4843.6  690.95  4863.8  687.85    4884   687.4
  4904.2  688.54  4923.3  688.46  4954.7  687.71    4985  688.87  4992.6  686.98
  4997.6  686.98  5003.1  685.28  5003.4  684.78  5006.9  684.78  5007.1  685.28
  5015.1  688.43  5025.2  689.03  5055.3  689.26  5165.3  691.31  5388.8  692.42
#Mann= 7 ,-1 , 0
  4482.7     .05       0  4532.9     .12       0    4776     .05       0
  4923.3     .12       0  5003.1     .07       0  5007.1     .12       0
  5055.3     .05       0
Bank Sta=5003.1,5007.1
XS Rating Curve= 0 ,0
Exp/Cntr=0.3,0.1

Type RM Length L Ch R = 1 ,1072    ,244,244,244
BEGIN DESCRIPTION:
LWE S 004 2.0
END DESCRIPTION:
XS GIS Cut Line= 4
      2357263.51      7035783.36      2357247.99        7036121.
      2357243.57      7036483.74      2357362.72      7036583.56
#Sta/Elev= 30
  4523.3  689.45    4560  688.74    4590  687.35    4610  685.78  4630.1  685.88
  4640.1  685.21  4660.1  685.26  4670.1  686.13  4690.1  685.38  4710.1  685.22
  4727.8   685.6  4740.2  685.28  4930.3  685.03  4950.3  684.18  4970.3  684.44
  4980.3   684.1  5000.3   684.7  5018.3  680.27  5018.6  679.77  5022.1  679.77
  5022.3  680.27  5030.3  684.92  5070.3  684.01  5170.3  683.82  5224.1  684.36
  5268.3  685.46  5274.8  685.29  5282.6  685.91  5296.4  686.19  5379.5  687.22
#Mann= 3 ,-1 , 0
  4523.3     .05       0  5018.3    .033       0  5022.3     .05       0
#XS Ineff= 2 , 0
       0    4800     687               0
Permanent Ineff=
       F       F
Bank Sta=5018.3,5022.3
XS Rating Curve= 0 ,0
Exp/Cntr=0.3,0.1

Type RM Length L Ch R = 1 ,828     ,295,295,295
BEGIN DESCRIPTION:
LWE S 004 1.8
END DESCRIPTION:
XS GIS Cut Line= 4
      2357057.82      7035837.72      2357042.29      7036175.33
      2357038.11      7036518.46      2357249.91       7036582.5
#Sta/Elev= 30
  4476.9  685.44  4499.2  685.86  4556.9  685.54  4562.1  684.71  4649.4  683.62
  4719.4   683.6  4759.5  684.24  4829.5  683.18  4859.5  684.27  4879.5  683.83
  4909.5  684.19  4929.6  683.76  4943.4  682.57  4959.6  680.34  4969.6  676.89
  4979.6  675.67  4989.6  678.14  4999.6  678.52  5009.6  675.86  5017.6  674.59
  5017.8  674.09  5021.3  674.09  5021.6  674.59  5029.6  678.69  5039.6  680.76
  5041.2  680.78  5079.6  680.57  5179.2  681.33  5286.9  682.87  5379.3  685.07
#Mann= 7 ,-1 , 0
  4476.9     .05       0  4556.9    .075       0  4943.4     .05       0
  5017.6    .033       0  5021.6     .05       0  5041.2    .075       0
  5179.2     .05       0
Bank Sta=5017.6,5021.6
XS Rating Curve= 0 ,0
Exp/Cntr=0.3,0.1

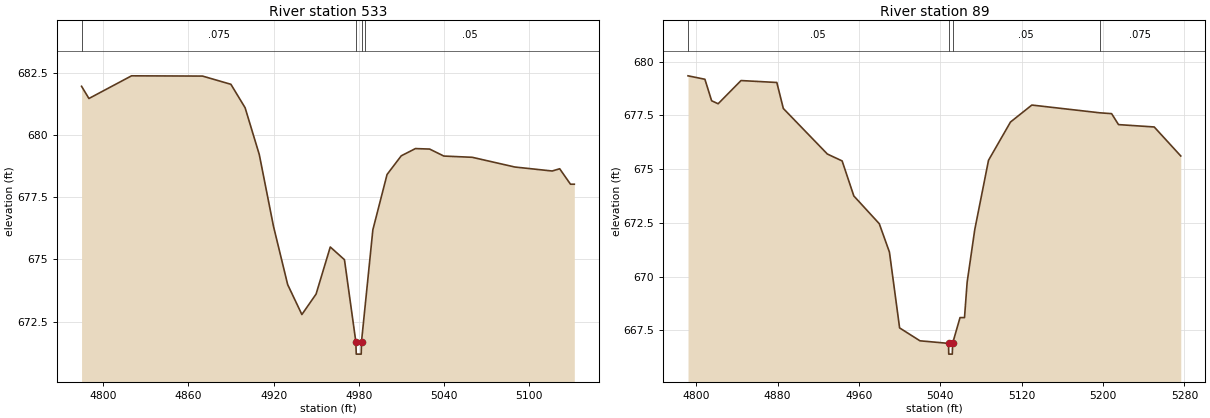
Type RM Length L Ch R = 1 ,533     ,444,444,444
BEGIN DESCRIPTION:
LWE S 004 1.0
END DESCRIPTION:
XS GIS Cut Line= 3
      2356762.86      7036194.78      2356759.64      7036514.11
      2356769.21      7036540.16
#Sta/Elev= 30
  4784.7  681.95  4789.9  681.46  4819.9  682.37  4869.9  682.36  4889.9  682.03
  4899.9  681.09  4909.9  679.21  4919.9  676.33  4929.9  673.99  4939.9  672.79
  4949.9  673.61  4959.9   675.5  4969.9  674.99  4977.9   671.7  4978.2   671.2
  4981.7   671.2  4981.9   671.7  4984.7  673.27  4989.9  676.19  4999.9  678.41
  5009.9  679.16  5019.9  679.45  5029.9  679.43  5039.9  679.15  5059.9   679.1
  5089.9  678.71  5116.2  678.55  5121.5  678.64  5129.1  678.02  5131.8  678.02
#Mann= 4 ,-1 , 0
  4784.7    .075       0  4977.9    .033       0  4981.9    .075       0
  4984.7     .05       0
Bank Sta=4977.9,4981.9
XS Rating Curve= 0 ,0
Exp/Cntr=0.3,0.1

Type RM Length L Ch R = 1 ,89      ,0,0,0
BEGIN DESCRIPTION:
LWE S 004 0.2
END DESCRIPTION:
XS GIS Cut Line= 4
       2356448.5      7036186.98      2356347.59      7036315.05
      2356351.47      7036423.72      2356509.32      7036566.16
#Sta/Elev= 30
    4792  679.34  4808.6  679.18  4815.2  678.18  4821.6  678.04  4844.1  679.12
  4879.3  679.03  4885.7  677.82    4929   675.7  4943.5  675.38    4955  673.75
    4980  672.46    4990  671.14    5000  667.61    5020  667.01  5048.1  666.89
  5048.3  666.39  5051.8  666.39  5052.1  666.89  5059.4  668.09  5063.8  668.09
  5066.4  669.74  5073.9  672.19  5087.4  675.41    5109  677.19    5130  677.98
  5196.6  677.62  5208.4  677.58  5215.2  677.07  5250.3  676.96  5276.4  675.61
#Mann= 4 ,-1 , 0
    4792     .05       0  5048.1    .033       0  5052.1     .05       0
  5196.6    .075       0
Bank Sta=5048.1,5052.1
XS Rating Curve= 0 ,0
Exp/Cntr=0.3,0.1

Chan Stop Cuts=-1
Use User Specified Reach Order=0
Composite Channel Slope=5