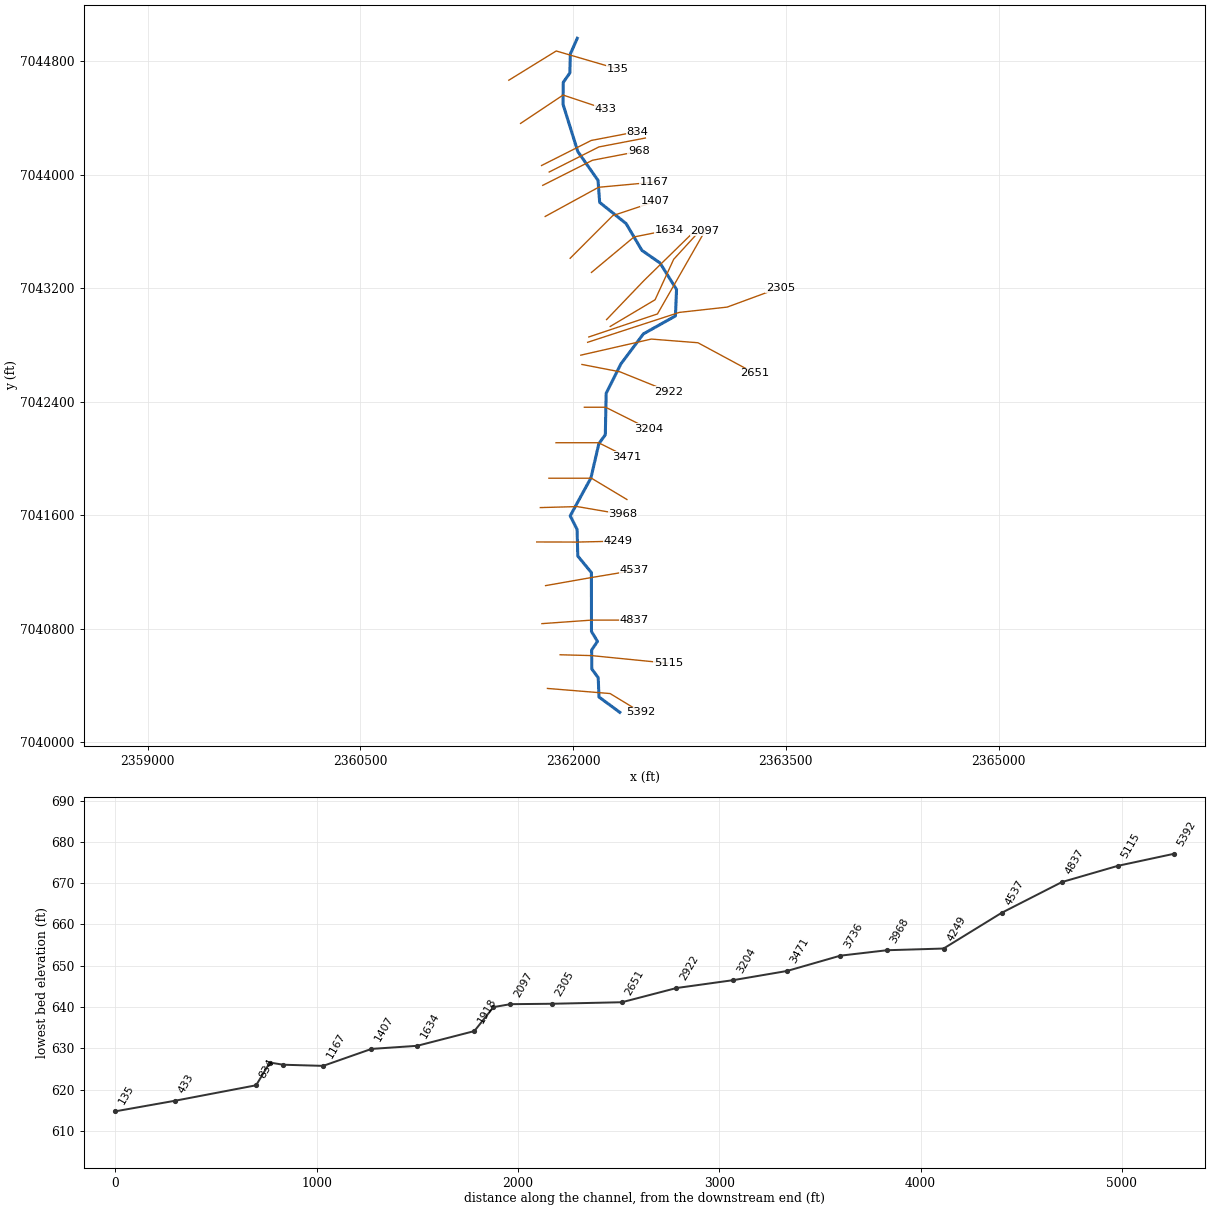
--- LWE S 006.prj (project) ---

Proj Title=LWE S 006 Base Level Engineering
Current Plan=p01
Default Exp/Contr=0.3,0.1
English Units
Geom File=g01
Flow File=f01
Plan File=p01
Y Axis Title=Elevation
X Axis Title(PF)=Main Channel Distance
X Axis Title(XS)=Station
BEGIN DESCRIPTION:
LWE S 006
END DESCRIPTION:
DSS Export Rating Curves= 0
DSS Export Rating Curve Sorted= 0
DSS Export Volume Flow Curves= 0
DXF OffsetX= 0
DXF OffsetY= 0
DXF ScaleX= 1
DXF ScaleY= 10

--- LWE S 006.p01 (plan) ---

Plan Title=Multiple Run
Program Version=4.10
Short Identifier=Multiple
Geom File=g01
Flow File=f01
Subcritical Flow
K Sum by GR= 0
Std Step Tol= 0.01
Critical Tol= 0.01
Num of Std Step Trials= 20
Max Error Tol= 0.3
Flow Tol Ratio= 0.001
Split Flow NTrial= 30
Split Flow Tol= 0.02
Split Flow Ratio= 0.02
Log Output Level= 0
Friction Slope Method= 1
Unsteady Friction Slope Method= 2
Unsteady Bridges Friction Slope Method= 1
Parabolic Critical Depth
Global Vel Dist= 1 , 1 , 1
Global Log Level= 0
CheckData=True
Encroach Param=-1 ,0,0, 0
BEGIN DESCRIPTION:
Multiple Run
END DESCRIPTION:
Computation Interval=1HOUR
Output Interval=1HOUR
Run HTab= 0
Run UNet= 0
Run PostProcess= 0
Run WQNet= 0
UNET Theta= 1
UNET Theta Warmup= 1
UNET ZTol= 0.02
UNET ZSATol= 0.05
UNET MxIter= 20
UNET MaxInSteps= 0
UNET DtIC= 0
UNET DtMin= 0
UNET MaxCRTS= 20
UNET WFStab= 2
UNET SFStab= 1
UNET WFX= 1
UNET SFX= 1
UNET DSS MLevel= 4
UNET DZMax Abort= 100
UNET Convert EG Bridges= 0
UNET Use Existing IB Tables=-1
UNET Froude Reduction=False
UNET Froude Limit= 1
UNET Froude Power= 10
UNET Time Slicing=0,0, 5
UNET Junction Losses=0
Instantaneous Interval=1HOUR
Write IC File= 0
Write IC File at Sim End=0
Echo Input=False
Echo Parameters=False
Echo Output=False
Write Detailed= 0
WQ AD Non Conservative
WQ ULTIMATE=-1
WQ Max Comp Step=1HOUR
WQ Output Interval=15MIN
WQ Output Selected Increments= 0
WQ Output face flow=0
WQ Output face velocity=0
WQ Output face area=0
WQ Output face dispersion=0
WQ Output cell volume=0
WQ Output cell surface area=0
WQ Output cell continuity=0
WQ Output cumulative cell continuity=0
WQ Output face conc=0
WQ Output face dconc_dx=0
WQ Output face courant=0
WQ Output face peclet=0
WQ Output face adv mass=0
WQ Output face disp mass=0
WQ Output cell mass=0
WQ Output cell source sink temp=0
WQ Output cell source sink nsm=0
WQ Output MaxMinRange=-1
WQ Daily Max Min Mean=-1
WQ Daily Range=0
WQ Daily Time=0
WQ Create Restart=0
WQ Fixed Restart=0
WQ System Summary=0
WQ Use Fixed Temperature=0
Sorting and Armoring Iterations= 10
XS Update Threshold= 0.02
Hydraulics Update Threshold= 0.02
Energy Slope Method= 1
Volume Change Method= 0
XS Weighting Method= 0
Number of US Weighted Cross Sections= 1
Number of DS Weighted Cross Sections= 1
Upstream XS Weight=0.25
Main XS Weight=0.5
Downstream XS Weight=0.25
Number of DS XS's Weighted with US Boundary= 1
Upstream Boundary Weight= 1
Weight of XSs Associated with US Boundary= 0
Number of US XS's Weighted with DS Boundary= 1
Downstream Boundary Weight= 0.5
Weight of XSs Associated with DS Boundary= 0.5
Sediment Output Level= 4
Mass or Volume Output= 0
Output Increment Type= 1
Profile and TS Output Increment= 10
XS Output Flag= 0
XS Output Increment= 10
Disregard all LS=0
Disregard all Conn=0
Disregard all Breaches=0
Disregard all Pumps=0

--- LWE S 006.f01 (steady flow) ---

Flow Title=Multiple
Number of Profiles=7
Profile Names=10-year,25-year,50-year,1pct_min,100-year,1pct_plu,500-year
River Rch & RM= LWE S 006,Reach-1,5392
     533     722     875     527    1052    2099    1518
River Rch & RM= LWE S 006,Reach-1,902
     552     748     909     548    1094    2183    1582
Boundary for River Rch & Prof#=LWE S 006,Reach-1,1
Up Type=0
Dn Type=3
Dn Slope=0.005
Boundary for River Rch & Prof#=LWE S 006,Reach-1,2
Up Type=0
Dn Type=3
Dn Slope=0.005
Boundary for River Rch & Prof#=LWE S 006,Reach-1,3
Up Type=0
Dn Type=3
Dn Slope=0.005
Boundary for River Rch & Prof#=LWE S 006,Reach-1,4
Up Type=0
Dn Type=3
Dn Slope=0.005
Boundary for River Rch & Prof#=LWE S 006,Reach-1,5
Up Type=0
Dn Type=3
Dn Slope=0.005
Boundary for River Rch & Prof#=LWE S 006,Reach-1,6
Up Type=0
Dn Type=3
Dn Slope=0.005
Boundary for River Rch & Prof#=LWE S 006,Reach-1,7
Up Type=0
Dn Type=3
Dn Slope=0.005

--- LWE S 006.g01 (geometry) ---

Geom Title=Existing Conditions

River Reach=LWE S 006,Reach-1
Reach XY= 30
      2362329.00      7040210.00      2362182.07      7040318.29
      2362176.72      7040454.05      2362131.25      7040515.94
      2362130.37      7040649.56      2362171.44      7040710.00
      2362129.18      7040779.98      2362128.61      7041194.84
      2362032.55      7041311.47      2362027.76      7041499.50
      2361979.08      7041594.61      2362125.17      7041861.58
      2362181.36      7042104.02      2362226.74      7042165.94
      2362232.75      7042458.45      2362337.14      7042666.06
      2362495.49      7042877.05      2362721.31      7043003.52
      2362729.04      7043190.02      2362612.36      7043376.70
      2362484.62      7043465.62      2362373.38      7043654.38
      2362186.82      7043803.81      2362175.45      7043958.53
      2362032.83      7044161.58      2361928.57      7044494.82
      2361930.22      7044649.49      2361976.73      7044715.94
      2361980.13      7044849.53      2362029.00      7044960.00

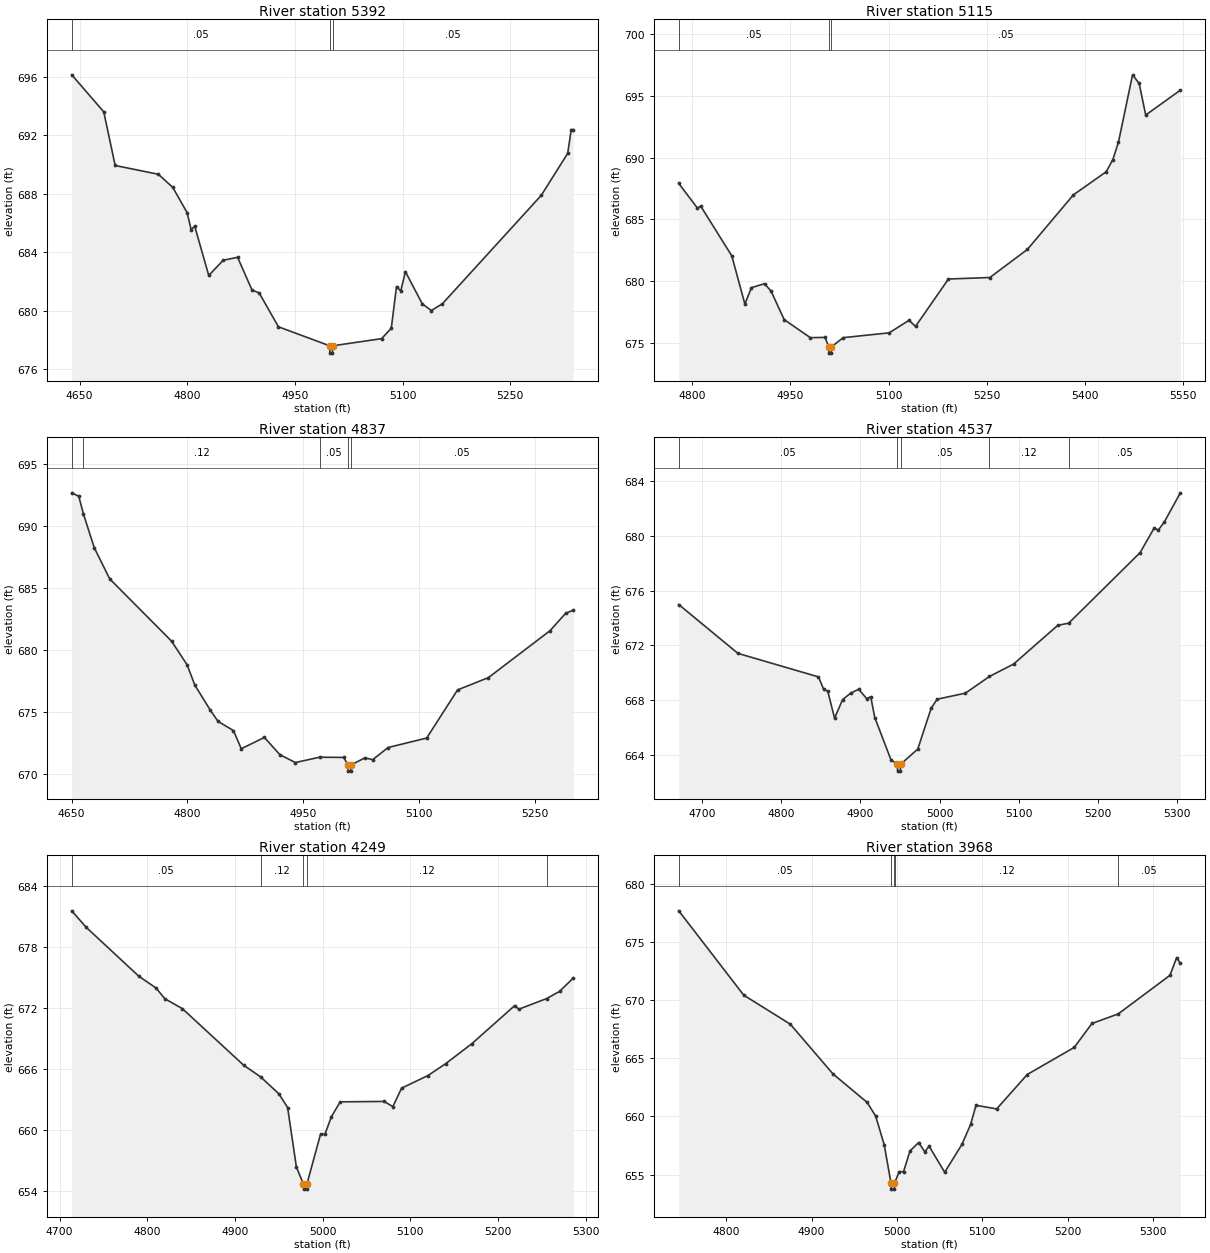
Type RM Length L Ch R = 1,5392,277,277,277
BEGIN DESCRIPTION:
LWE S 006 18.0
END DESCRIPTION:
XS GIS Cut Line= 3
      2361818.71      7040378.55      2362260.35      7040342.54
      2362479.01      7040210.00
#Sta/Elev= 30
  4639.1  696.13  4683.7  693.60  4699.6  689.93  4759.8  689.33  4779.9  688.43
  4799.9  686.70  4805.4  685.55  4810.4  685.78  4830.0  682.41  4850.1  683.45
  4870.2  683.65  4890.2  681.42  4900.3  681.21  4927.1  678.90  4998.6  677.60
  4998.8  677.10  5002.3  677.10  5002.6  677.60  5070.8  678.09  5084.3  678.80
  5091.6  681.65  5097.5  681.35  5104.0  682.67  5127.4  680.48  5140.1  680.01
  5155.6  680.48  5293.3  687.89  5330.1  690.76  5335.0  692.38  5337.9  692.38
#Mann=3,-1,0
  4639.1    0.05       0  4998.6   0.033       0  5002.6    0.05       0
Bank Sta=4998.6,5002.6
Exp/Cntr=0.3,0.1

Type RM Length L Ch R = 1,5115,278,278,278
BEGIN DESCRIPTION:
LWE S 006 17.0
END DESCRIPTION:
XS GIS Cut Line= 3
      2361908.06      7040615.82      2362129.00      7040610.00
      2362671.60      7040555.99
#Sta/Elev= 30
  4779.4  687.91  4807.9  685.92  4812.9  686.08  4860.4  682.06  4880.4  678.16
  4890.4  679.49  4910.4  679.81  4920.4  679.21  4940.4  676.91  4980.4  675.45
  5002.9  675.47  5008.5  674.70  5008.7  674.20  5012.2  674.20  5012.5  674.70
  5030.6  675.45  5100.9  675.84  5131.1  676.85  5141.1  676.36  5191.4  680.19
  5254.7  680.31  5312.0  682.58  5382.3  686.99  5432.5  688.86  5442.6  689.84
  5451.2  691.26  5472.7  696.69  5482.8  695.99  5492.8  693.44  5545.7  695.45
#Mann=3,-1,0
  4779.4    0.05       0  5008.5   0.033       0  5012.5    0.05       0
Bank Sta=5008.5,5012.5
Exp/Cntr=0.3,0.1

Type RM Length L Ch R = 1,4837,300,300,300
BEGIN DESCRIPTION:
LWE S 006 16.0
END DESCRIPTION:
XS GIS Cut Line= 3
      2361779.89      7040835.21      2362129.00      7040860.00
      2362429.01      7040860.00
#Sta/Elev= 30
  4650.1  692.65  4659.2  692.37  4665.2  690.96  4679.3  688.23  4699.3  685.73
  4779.5  680.72  4799.6  678.82  4809.6  677.19  4829.7  675.17  4839.7  674.27
  4859.7  673.53  4869.8  672.07  4899.8  672.98  4919.9  671.59  4939.9  670.96
  4971.3  671.39  5002.6  671.37  5008.1  670.77  5008.3  670.27  5011.8  670.27
  5012.1  670.77  5030.1  671.34  5040.1  671.19  5060.1  672.17  5110.1  672.93
  5150.1  676.80  5190.1  677.79  5270.1  681.57  5290.1  682.96  5300.1  683.21
#Mann=5,-1,0
  4650.1    0.05       0  4665.2    0.12       0  4971.3    0.05       0
  5008.1   0.033       0  5012.1    0.05       0
Bank Sta=5008.1,5012.1
Exp/Cntr=0.3,0.1

Type RM Length L Ch R = 1,4537,288,288,288
BEGIN DESCRIPTION:
LWE S 006 15.0
END DESCRIPTION:
XS GIS Cut Line= 3
      2361805.50      7041103.03      2362129.00      7041160.00
      2362428.98      7041210.00
#Sta/Elev= 30
  4671.1  674.98  4745.7  671.41  4847.3  669.69  4853.9  668.77  4859.0  668.64
  4867.6  666.67  4877.7  668.03  4887.9  668.50  4898.0  668.79  4908.1  668.10
  4913.2  668.24  4918.3  666.72  4938.7  663.63  4946.8  663.30  4947.1  662.80
  4950.6  662.80  4950.8  663.30  4972.5  664.41  4989.4  667.40  4997.0  668.06
  5032.5  668.50  5062.9  669.72  5093.4  670.63  5149.1  673.46  5162.9  673.62
  5253.0  678.78  5270.8  680.59  5275.8  680.42  5283.4  681.01  5303.7  683.15
#Mann=5,-1,0
  4671.1    0.05       0  4946.8   0.033       0  4950.8    0.05       0
  5062.9    0.12       0  5162.9    0.05       0
Bank Sta=4946.8,4950.8
Exp/Cntr=0.3,0.1

Type RM Length L Ch R = 1,4249,281,281,281
BEGIN DESCRIPTION:
LWE S 006 14.0
END DESCRIPTION:
XS GIS Cut Line= 3
      2361742.78      7041410.74      2362029.00      7041410.00
      2362314.71      7041416.42
#Sta/Elev= 30
  4713.8  681.58  4730.0  679.98  4790.0  675.16  4810.0  673.97  4820.0  672.92
  4840.0  671.94  4910.0  666.36  4929.2  665.22  4950.0  663.55  4960.0  662.20
  4970.0  656.34  4978.0  654.66  4978.3  654.16  4981.8  654.16  4982.0  654.66
  4997.5  659.56  5002.5  659.56  5010.0  661.31  5020.0  662.76  5070.0  662.80
  5080.0  662.29  5090.0  664.11  5120.0  665.35  5140.1  666.51  5170.1  668.49
  5218.8  672.23  5223.8  671.89  5255.5  672.94  5270.1  673.64  5285.8  674.96
#Mann=5,-1,0
  4713.8    0.05       0  4929.2    0.12       0  4978.0    0.07       0
  4982.0    0.12       0  5255.5    0.05       0
Bank Sta=4978,4982
Exp/Cntr=0.3,0.1

Type RM Length L Ch R = 1,3968,232,232,232
BEGIN DESCRIPTION:
LWE S 006 13.0
END DESCRIPTION:
XS GIS Cut Line= 3
      2361768.45      7041652.93      2362029.00      7041660.00
      2362351.05      7041604.74
#Sta/Elev= 30
  4744.5  677.69  4820.5  670.44  4875.1  667.94  4925.1  663.66  4965.1  661.21
  4975.1  660.03  4985.1  657.56  4993.1  654.25  4993.4  653.75  4996.9  653.75
  4997.1  654.25  4998.0  654.41  5002.6  655.25  5007.7  655.25  5015.3  657.04
  5025.4  657.76  5032.6  656.96  5037.7  657.44  5055.9  655.20  5076.2  657.61
  5086.3  659.32  5092.6  660.96  5116.8  660.65  5152.6  663.61  5207.6  665.94
  5228.4  668.00  5259.1  668.82  5319.7  672.14  5327.6  673.67  5331.9  673.16
#Mann=5,-1,0
  4744.5    0.05       0  4993.1    0.07       0  4997.1    0.05       0
  4998.0    0.12       0  5259.1    0.05       0
Bank Sta=4993.1,4997.1
Exp/Cntr=0.3,0.1

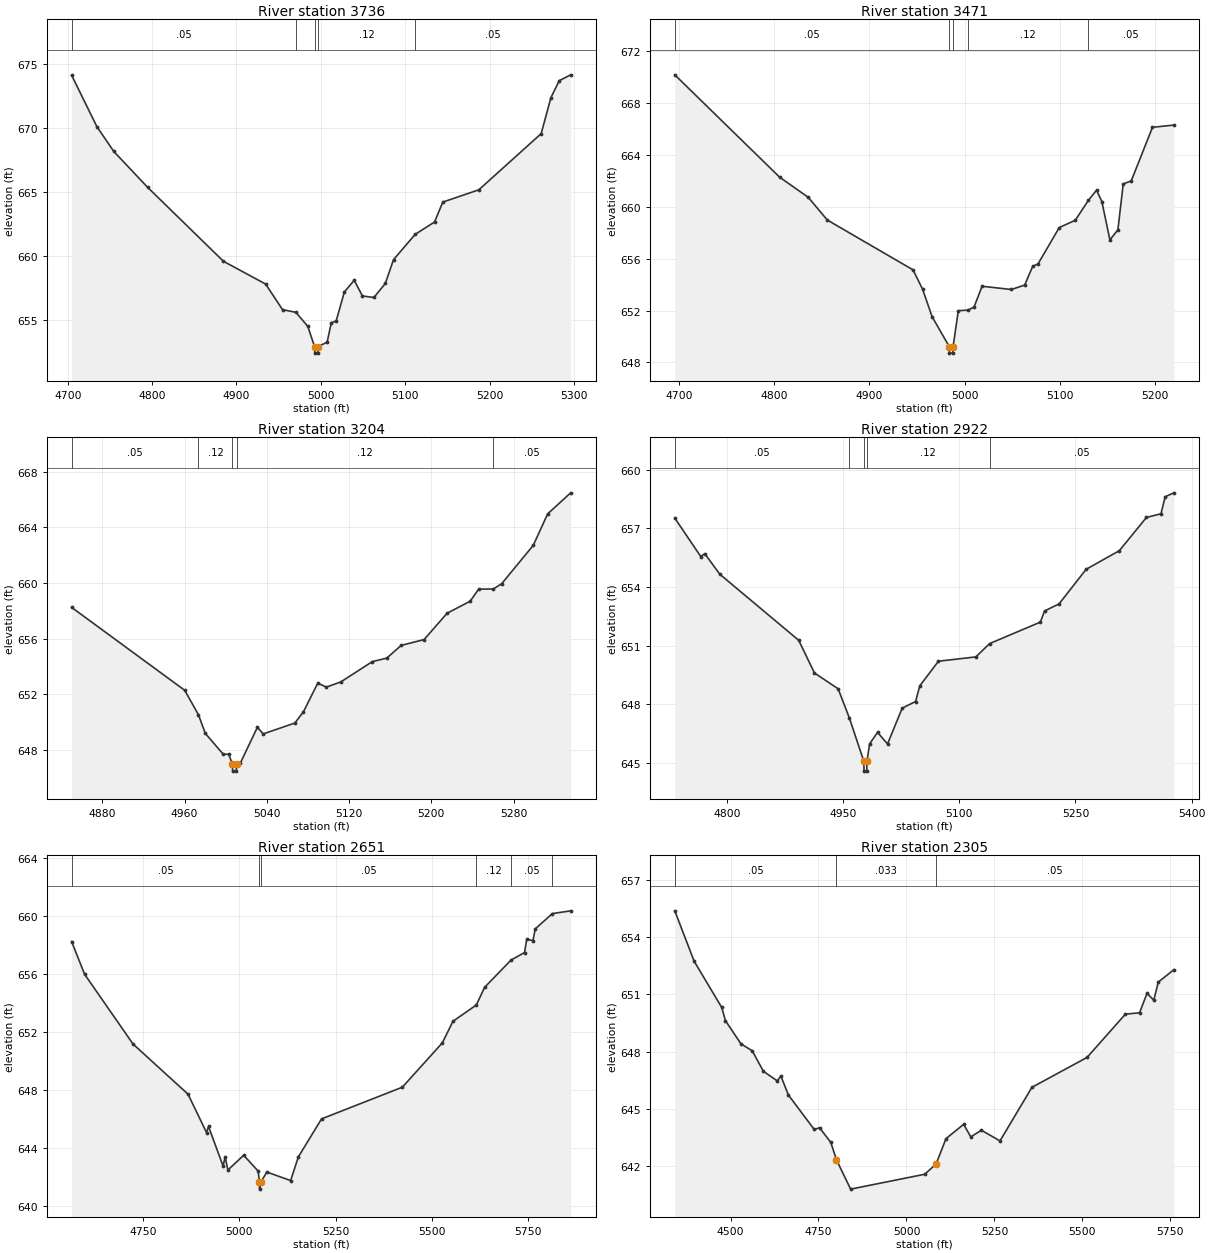
Type RM Length L Ch R = 1,3736,265,265,265
BEGIN DESCRIPTION:
LWE S 006 12.0
END DESCRIPTION:
XS GIS Cut Line= 3
      2361828.99      7041860.00      2362129.00      7041860.00
      2362379.03      7041709.98
#Sta/Elev= 30
  4704.6  674.16  4734.6  670.13  4754.6  668.20  4794.6  665.40  4884.6  659.61
  4934.6  657.83  4954.6  655.83  4970.5  655.62  4984.6  654.52  4992.6  652.93
  4992.9  652.43  4996.4  652.43  4996.6  652.93  5007.5  653.29  5012.4  654.80
  5018.2  654.94  5027.9  657.21  5039.6  658.13  5049.3  656.90  5062.9  656.78
  5076.5  657.88  5086.2  659.74  5111.9  661.72  5134.8  662.68  5144.6  664.24
  5187.3  665.20  5261.2  669.59  5272.8  672.41  5282.6  673.73  5296.2  674.19
#Mann=5,-1,0
  4704.6    0.05       0  4970.5    0.12       0  4992.6    0.07       0
  4996.6    0.12       0  5111.9    0.05       0
Bank Sta=4992.6,4996.6
Exp/Cntr=0.3,0.1

Type RM Length L Ch R = 1,3471,267,267,267
BEGIN DESCRIPTION:
LWE S 006 11.0
END DESCRIPTION:
XS GIS Cut Line= 3
      2361879.00      7042110.00      2362179.00      7042110.00
      2362379.00      7042010.00
#Sta/Elev= 30
  4695.8  670.15  4805.8  662.27  4835.8  660.72  4855.8  658.97  4945.8  655.13
  4955.8  653.64  4965.8  651.52  4983.8  649.22  4984.0  648.72  4987.5  648.72
  4987.8  649.22  4993.3  651.99  5003.5  652.03  5009.8  652.27  5018.2  653.87
  5048.9  653.62  5062.9  653.96  5071.3  655.40  5076.9  655.59  5099.2  658.39
  5116.0  658.95  5129.7  660.48  5138.3  661.27  5143.9  660.39  5152.3  657.44
  5160.7  658.21  5166.3  661.75  5174.7  661.98  5197.0  666.11  5219.4  666.28
#Mann=5,-1,0
  4695.8    0.05       0  4983.8    0.04       0  4987.8    0.05       0
  5003.5    0.12       0  5129.7    0.05       0
Bank Sta=4983.8,4987.8
Exp/Cntr=0.3,0.1

Type RM Length L Ch R = 1,3204,282,282,282
BEGIN DESCRIPTION:
LWE S 006 10.0
END DESCRIPTION:
XS GIS Cut Line= 3
      2362079.02      7042360.00      2362229.00      7042360.00
      2362529.01      7042209.99
#Sta/Elev= 30
  4850.1  658.25  4960.1  652.30  4973.5  650.54  4980.1  649.21  4997.6  647.71
  5002.9  647.71  5006.5  647.00  5006.7  646.50  5010.2  646.50  5010.5  647.00
  5014.1  647.06  5030.8  649.65  5036.4  649.17  5067.2  649.95  5075.5  650.75
  5089.5  652.81  5097.9  652.53  5111.9  652.90  5142.6  654.36  5156.6  654.61
  5170.6  655.52  5192.9  655.94  5215.3  657.83  5237.7  658.69  5246.0  659.56
  5260.2  659.57  5268.4  659.95  5299.1  662.70  5313.1  664.96  5335.5  666.47
#Mann=5,-1,0
  4850.1    0.05       0  4973.5    0.12       0  5006.5    0.07       0
  5010.5    0.12       0  5260.2    0.05       0
Bank Sta=5006.5,5010.5
Exp/Cntr=0.3,0.1

Type RM Length L Ch R = 1,2922,271,271,271
BEGIN DESCRIPTION:
LWE S 006 9.0
END DESCRIPTION:
XS GIS Cut Line= 3
      2362061.94      7042661.54      2362329.00      7042610.00
      2362674.28      7042470.73
#Sta/Elev= 30
  4732.7  657.53  4766.3  655.56  4771.4  655.71  4790.8  654.66  4892.7  651.28
  4913.0  649.61  4943.6  648.80  4958.0  647.32  4976.8  645.09  4977.0  644.59
  4980.5  644.59  4980.8  645.09  4984.3  645.99  4994.5  646.57  5007.4  645.98
  5026.3  647.81  5043.6  648.15  5049.0  648.95  5073.1  650.21  5121.4  650.43
  5139.1  651.11  5204.7  652.21  5210.1  652.78  5228.8  653.14  5263.8  654.91
  5306.6  655.86  5341.6  657.56  5360.4  657.75  5365.8  658.62  5377.0  658.82
#Mann=5,-1,0
  4732.7    0.05       0  4958.0    0.12       0  4976.8    0.07       0
  4980.8    0.12       0  5139.1    0.05       0
Bank Sta=4976.8,4980.8
Exp/Cntr=0.3,0.1

Type RM Length L Ch R = 1,2651,346,346,346
BEGIN DESCRIPTION:
LWE S 006 8.5
END DESCRIPTION:
XS GIS Cut Line= 4
      2362053.55      7042726.95      2362551.15      7042840.41
      2362880.21      7042814.48      2363280.60      7042598.88
#Sta/Elev= 30
  4564.8  658.25  4598.5  655.99  4724.2  651.17  4866.8  647.71  4914.9  645.06
  4920.1  645.48  4957.9  642.74  4963.1  643.38  4970.4  642.47  5011.4  643.49
  5049.1  642.39  5052.2  641.65  5052.5  641.15  5056.2  641.65  5071.5  642.33
  5133.2  641.74  5153.3  643.38  5213.4  646.00  5423.1  648.19  5526.9  651.25
  5554.5  652.74  5615.3  653.87  5636.4  655.08  5705.2  656.97  5740.3  657.49
  5746.0  658.42  5762.2  658.31  5767.9  659.12  5812.5  660.18  5860.0  660.37
#Mann=6,-1,0
  4564.8    0.05       0  5052.2    0.04       0  5056.2    0.05       0
  5615.3    0.12       0  5705.2    0.05       0  5812.5    0.12       0
Bank Sta=5052.2,5056.2
Exp/Cntr=0.3,0.1

Type RM Length L Ch R = 1,2305,208,208,208
BEGIN DESCRIPTION:
LWE S 006 8.0
END DESCRIPTION:
XS GIS Cut Line= 4
      2362102.11      7042817.71      2362748.91      7043028.45
      2363086.07      7043065.73      2363460.54      7043203.52
#Sta/Elev= 30
  4341.5  655.38  4396.7  652.73  4475.0  650.31  4485.5  649.62  4529.6  648.40
  4561.5  648.04  4593.5  646.96  4632.7  646.46  4643.2  646.71  4664.3  645.72
  4737.9  643.91  4753.0  644.00  4785.0  643.23  4801.0  642.32  4841.3  640.78
  5052.0  641.56  5084.3  642.10  5112.4  643.43  5162.7  644.18  5182.8  643.52
  5213.0  643.87  5265.9  643.31  5356.6  646.12  5513.3  647.69  5622.3  649.96
  5662.5  650.03  5683.8  651.05  5703.1  650.69  5715.7  651.64  5760.0  652.29
#Mann=3,-1,0
  4341.5    0.05       0  4801.0   0.033       0  5084.3    0.05       0
Bank Sta=4801,5084.3
Exp/Cntr=0.3,0.1

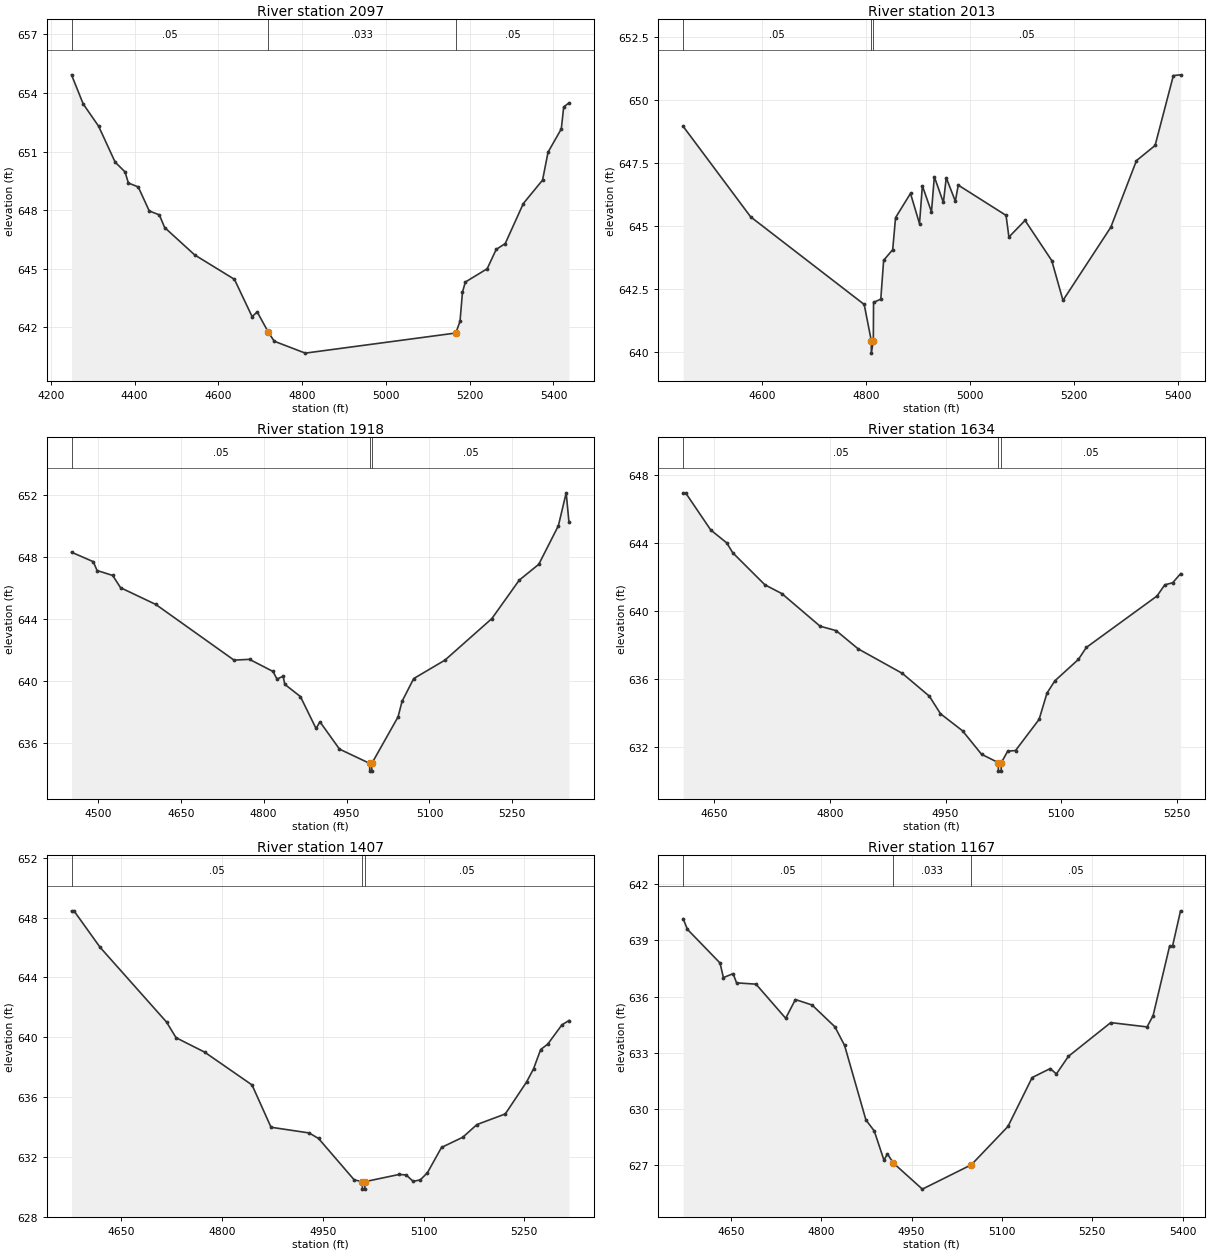
Type RM Length L Ch R = 1,2097,84,84,84
BEGIN DESCRIPTION:
LWE S 006 7.0
END DESCRIPTION:
XS GIS Cut Line= 3
      2362110.33      7042855.28      2362594.72      7043017.69
      2362930.92      7043604.62
#Sta/Elev= 30
  4249.7  654.93  4277.5  653.44  4314.3  652.30  4353.8  650.46  4377.4  649.96
  4385.4  649.39  4408.9  649.19  4435.2  647.96  4459.2  647.76  4472.0  647.11
  4543.6  645.71  4638.5  644.46  4680.7  642.55  4692.9  642.79  4719.2  641.76
  4733.5  641.29  4807.6  640.68  5166.9  641.71  5177.0  642.31  5182.8  643.80
  5189.7  644.32  5241.8  645.00  5263.3  645.99  5284.9  646.29  5328.1  648.34
  5374.0  649.54  5387.1  650.97  5418.7  652.16  5424.5  653.29  5437.0  653.49
#Mann=3,-1,0
  4249.7    0.05       0  4719.2   0.033       0  5166.9    0.05       0
Bank Sta=4719.2,5166.9
Exp/Cntr=0.3,0.1

Type RM Length L Ch R = 1,2013,95,95,95
BEGIN DESCRIPTION:
LWE S 006 6.3
END DESCRIPTION:
XS GIS Cut Line= 4
      2362261.34      7042929.35      2362577.62      7043117.41
      2362708.69      7043402.33      2362893.85      7043604.59
#Sta/Elev= 30
  4448.4  648.96  4578.2  645.37  4796.3  641.90  4809.9  640.47  4810.1  639.97
  4813.9  640.47  4814.3  641.98  4828.2  642.11  4833.7  643.65  4851.1  644.07
  4856.6  645.34  4885.3  646.30  4902.6  645.10  4908.1  646.60  4925.6  645.57
  4931.1  646.96  4948.5  645.94  4954.0  646.92  4971.5  645.99  4977.0  646.63
  5068.9  645.43  5074.4  644.57  5105.4  645.23  5156.7  643.64  5178.3  642.06
  5270.2  644.96  5319.5  647.60  5355.3  648.20  5390.4  650.97  5404.2  651.00
#Mann=3,-1,0
  4448.4    0.05       0  4809.9    0.04       0  4813.9    0.05       0
Bank Sta=4809.9,4813.9
Exp/Cntr=0.3,0.1

Type RM Length L Ch R = 1,1918,284,284,284
BEGIN DESCRIPTION:
LWE S 006 6.0
END DESCRIPTION:
XS GIS Cut Line= 3
      2362235.72      7042977.80      2362500.70      7043254.17
      2362870.60      7043615.54
#Sta/Elev= 30
  4452.4  648.28  4491.7  647.67  4498.6  647.10  4526.9  646.78  4541.1  645.99
  4604.9  644.91  4746.4  641.32  4774.4  641.37  4816.9  640.59  4824.1  640.10
  4835.3  640.28  4838.2  639.76  4866.5  638.97  4894.8  636.91  4901.9  637.34
  4937.2  635.58  4991.8  634.66  4992.0  634.16  4995.5  634.16  4995.8  634.66
  5043.2  637.66  5050.4  638.66  5071.5  640.13  5128.1  641.32  5212.9  644.00
  5262.5  646.48  5297.8  647.50  5333.3  649.99  5347.4  652.11  5352.4  650.22
#Mann=3,-1,0
  4452.4    0.05       0  4991.8    0.04       0  4995.8    0.05       0
Bank Sta=4991.8,4995.8
Exp/Cntr=0.3,0.1

Type RM Length L Ch R = 1,1634,227,227,227
BEGIN DESCRIPTION:
LWE S 006 5.0
END DESCRIPTION:
XS GIS Cut Line= 3
      2362129.02      7043310.02      2362429.00      7043560.00
      2362678.96      7043609.99
#Sta/Elev= 30
  4609.5  646.93  4612.7  646.93  4645.3  644.75  4666.1  643.99  4673.9  643.41
  4715.6  641.53  4737.7  641.01  4787.2  639.10  4808.0  638.84  4836.6  637.77
  4893.9  636.33  4929.0  634.99  4943.4  633.96  4972.0  632.96  4996.7  631.58
  5018.4  631.09  5018.6  630.59  5022.1  630.59  5022.4  631.09  5030.6  631.76
  5040.8  631.80  5071.4  633.63  5081.6  635.17  5091.8  635.89  5122.4  637.15
  5132.6  637.85  5224.3  640.87  5234.5  641.53  5244.7  641.65  5254.9  642.18
#Mann=3,-1,0
  4609.5    0.05       0  5018.4    0.04       0  5022.4    0.05       0
Bank Sta=5018.4,5022.4
Exp/Cntr=0.3,0.1

Type RM Length L Ch R = 1,1407,240,240,240
BEGIN DESCRIPTION:
LWE S 006 4.0
END DESCRIPTION:
XS GIS Cut Line= 3
      2361978.98      7043409.98      2362279.00      7043710.00
      2362578.98      7043809.99
#Sta/Elev= 30
  4575.9  648.46  4579.5  648.46  4618.4  646.02  4717.3  641.02  4731.5  639.97
  4773.9  639.01  4844.6  636.81  4872.9  633.98  4929.5  633.60  4943.6  633.23
  4996.7  630.46  5008.7  630.34  5009.0  629.84  5012.5  629.84  5012.7  630.34
  5063.4  630.82  5074.0  630.79  5084.5  630.36  5095.1  630.46  5105.6  630.93
  5126.7  632.63  5158.3  633.31  5179.4  634.16  5221.6  634.87  5253.2  637.00
  5263.7  637.89  5274.3  639.18  5284.8  639.54  5305.9  640.83  5316.4  641.12
#Mann=3,-1,0
  4575.9    0.05       0  5008.7    0.04       0  5012.7    0.05       0
Bank Sta=5008.7,5012.7
Exp/Cntr=0.3,0.1

Type RM Length L Ch R = 1,1167,199,199,199
BEGIN DESCRIPTION:
LWE S 006 3.0
END DESCRIPTION:
XS GIS Cut Line= 3
      2361802.67      7043704.36      2362179.00      7043910.00
      2362574.37      7043946.49
#Sta/Elev= 30
  4570.8  640.15  4578.0  639.58  4632.0  637.79  4637.7  637.01  4653.8  637.22
  4659.5  636.73  4691.8  636.66  4741.1  634.84  4757.2  635.84  4784.8  635.55
  4822.7  634.39  4838.8  633.40  4874.3  629.42  4888.2  628.83  4904.3  627.27
  4910.0  627.61  4919.9  627.12  4968.0  625.73  5049.4  627.03  5110.1  629.07
  5150.3  631.68  5180.4  632.16  5190.5  631.87  5210.5  632.81  5280.8  634.61
  5341.1  634.38  5351.1  634.98  5378.4  638.67  5383.4  638.69  5396.7  640.57
#Mann=3,-1,0
  4570.8    0.05       0  4919.9   0.033       0  5049.4    0.05       0
Bank Sta=4919.9,5049.4
Exp/Cntr=0.3,0.1

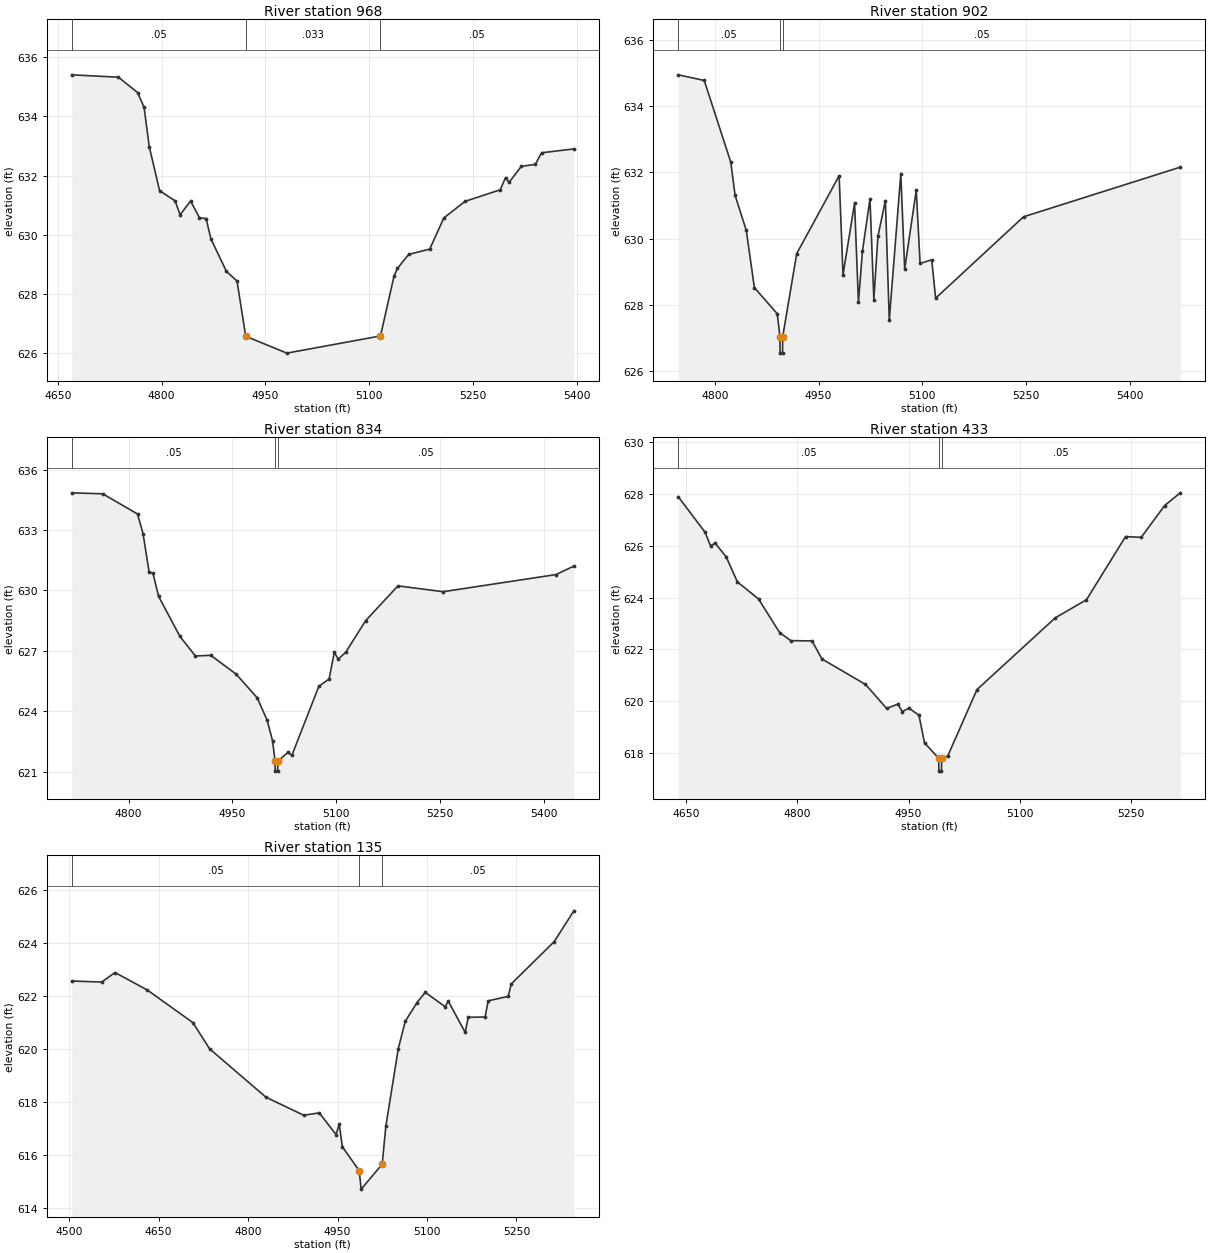
Type RM Length L Ch R = 1,968,66,66,66
BEGIN DESCRIPTION:
LWE S 006 2.3
END DESCRIPTION:
XS GIS Cut Line= 3
      2361785.58      7043923.75      2362136.00      7044100.39
      2362463.64      7044163.07
#Sta/Elev= 30
  4670.0  635.40  4737.4  635.32  4765.3  634.80  4774.6  634.30  4782.0  632.98
  4797.0  631.49  4819.4  631.15  4826.6  630.68  4841.8  631.14  4854.6  630.58
  4864.2  630.55  4871.3  629.86  4893.6  628.77  4909.0  628.44  4921.5  626.58
  4981.0  626.01  5116.4  626.59  5135.9  628.60  5141.0  628.87  5157.1  629.34
  5187.6  629.52  5208.0  630.57  5238.6  631.13  5289.5  631.52  5297.2  631.93
  5302.3  631.77  5320.0  632.31  5340.4  632.38  5349.3  632.77  5396.0  632.90
#Mann=3,-1,0
  4670.0    0.05       0  4921.5   0.033       0  5116.4    0.05       0
Bank Sta=4921.5,5116.4
Exp/Cntr=0.3,0.1

Type RM Length L Ch R = 1,902,68,68,68
BEGIN DESCRIPTION:
LWE S 006 2.2
END DESCRIPTION:
XS GIS Cut Line= 3
      2361831.13      7044017.76      2362181.58      7044194.41
      2362509.29      7044257.10
#Sta/Elev= 30
  4747.0  634.95  4784.6  634.78  4823.0  632.31  4829.2  631.31  4845.4  630.25
  4857.1  628.52  4890.2  627.73  4894.1  627.04  4894.3  626.54  4897.8  626.54
  4898.1  627.04  4918.4  629.55  4979.7  631.90  4985.3  628.91  5002.0  631.07
  5007.6  628.07  5013.4  629.62  5024.3  631.20  5029.9  628.16  5035.8  630.07
  5046.6  631.15  5052.2  627.54  5068.9  631.96  5074.5  629.08  5091.2  631.46
  5096.8  629.25  5113.6  629.36  5119.2  628.20  5246.4  630.66  5473.1  632.16
#Mann=3,-1,0
  4747.0    0.05       0  4894.1   0.033       0  4898.1    0.05       0
Bank Sta=4894.1,4898.1
Exp/Cntr=0.3,0.1

Type RM Length L Ch R = 1,834,401,401,401
BEGIN DESCRIPTION:
LWE S 006 2.0
END DESCRIPTION:
XS GIS Cut Line= 3
      2361777.00      7044063.35      2362127.45      7044240.00
      2362454.57      7044302.58
#Sta/Elev= 30
  4717.9  634.85  4762.7  634.80  4812.9  633.80  4820.9  632.82  4829.6  630.93
  4835.2  630.86  4843.3  629.71  4874.2  627.72  4896.5  626.75  4918.8  626.78
  4955.3  625.85  4985.7  624.68  5000.1  623.57  5008.0  622.54  5011.6  621.53
  5011.9  621.03  5015.4  621.03  5015.6  621.53  5030.3  621.96  5035.9  621.81
  5075.0  625.25  5089.7  625.60  5097.3  626.94  5102.9  626.59  5113.7  626.93
  5142.5  628.50  5189.2  630.23  5254.5  629.94  5417.4  630.79  5443.4  631.21
#Mann=3,-1,0
  4717.9    0.05       0  5011.6    0.04       0  5015.6    0.05       0
Bank Sta=5011.6,5015.6
Exp/Cntr=0.3,0.1

Type RM Length L Ch R = 1,433,298,298,298
BEGIN DESCRIPTION:
LWE S 006 1.0
END DESCRIPTION:
XS GIS Cut Line= 3
      2361628.98      7044359.98      2361929.00      7044560.00
      2362228.99      7044460.00
#Sta/Elev= 30
  4639.6  627.90  4675.7  626.53  4683.2  626.00  4689.2  626.11  4704.2  625.58
  4719.3  624.61  4747.8  623.95  4776.3  622.65  4791.4  622.34  4819.9  622.33
  4833.4  621.63  4892.0  620.65  4920.6  619.72  4935.6  619.89  4941.6  619.60
  4950.6  619.73  4964.1  619.46  4971.6  618.39  4990.7  617.80  4990.9  617.30
  4994.4  617.30  4994.7  617.80  5002.8  617.88  5042.3  620.45  5147.8  623.22
  5189.9  623.92  5242.6  626.36  5263.7  626.33  5295.3  627.56  5316.4  628.05
#Mann=3,-1,0
  4639.6    0.05       0  4990.7    0.04       0  4994.7    0.05       0
Bank Sta=4990.7,4994.7
Exp/Cntr=0.3,0.1

Type RM Length L Ch R = 1,135,0,0,0
BEGIN DESCRIPTION:
LWE S 006 0.5
END DESCRIPTION:
XS GIS Cut Line= 3
      2361546.21      7044664.52      2361880.56      7044870.56
      2362311.50      7044744.64
#Sta/Elev= 30
  4504.5  622.58  4554.8  622.54  4577.0  622.90  4631.1  622.24  4707.5  621.01
  4735.5  620.02  4830.1  618.19  4893.4  617.51  4919.4  617.60  4947.6  616.78
  4952.8  617.18  4958.1  616.32  4986.3  615.42  4989.7  614.72  5024.9  615.66
  5031.0  617.09  5051.9  620.03  5063.6  621.06  5083.1  621.76  5097.1  622.15
  5130.5  621.61  5135.7  621.82  5164.0  620.64  5169.2  621.21  5197.4  621.22
  5202.6  621.83  5236.1  622.00  5241.3  622.47  5313.4  624.07  5346.2  625.23
#Mann=3,-1,0
  4504.5    0.05       0  4986.3   0.033       0  5024.9    0.05       0
Bank Sta=4986.3,5024.9
Exp/Cntr=0.3,0.1

Chan Stop Cuts=-1