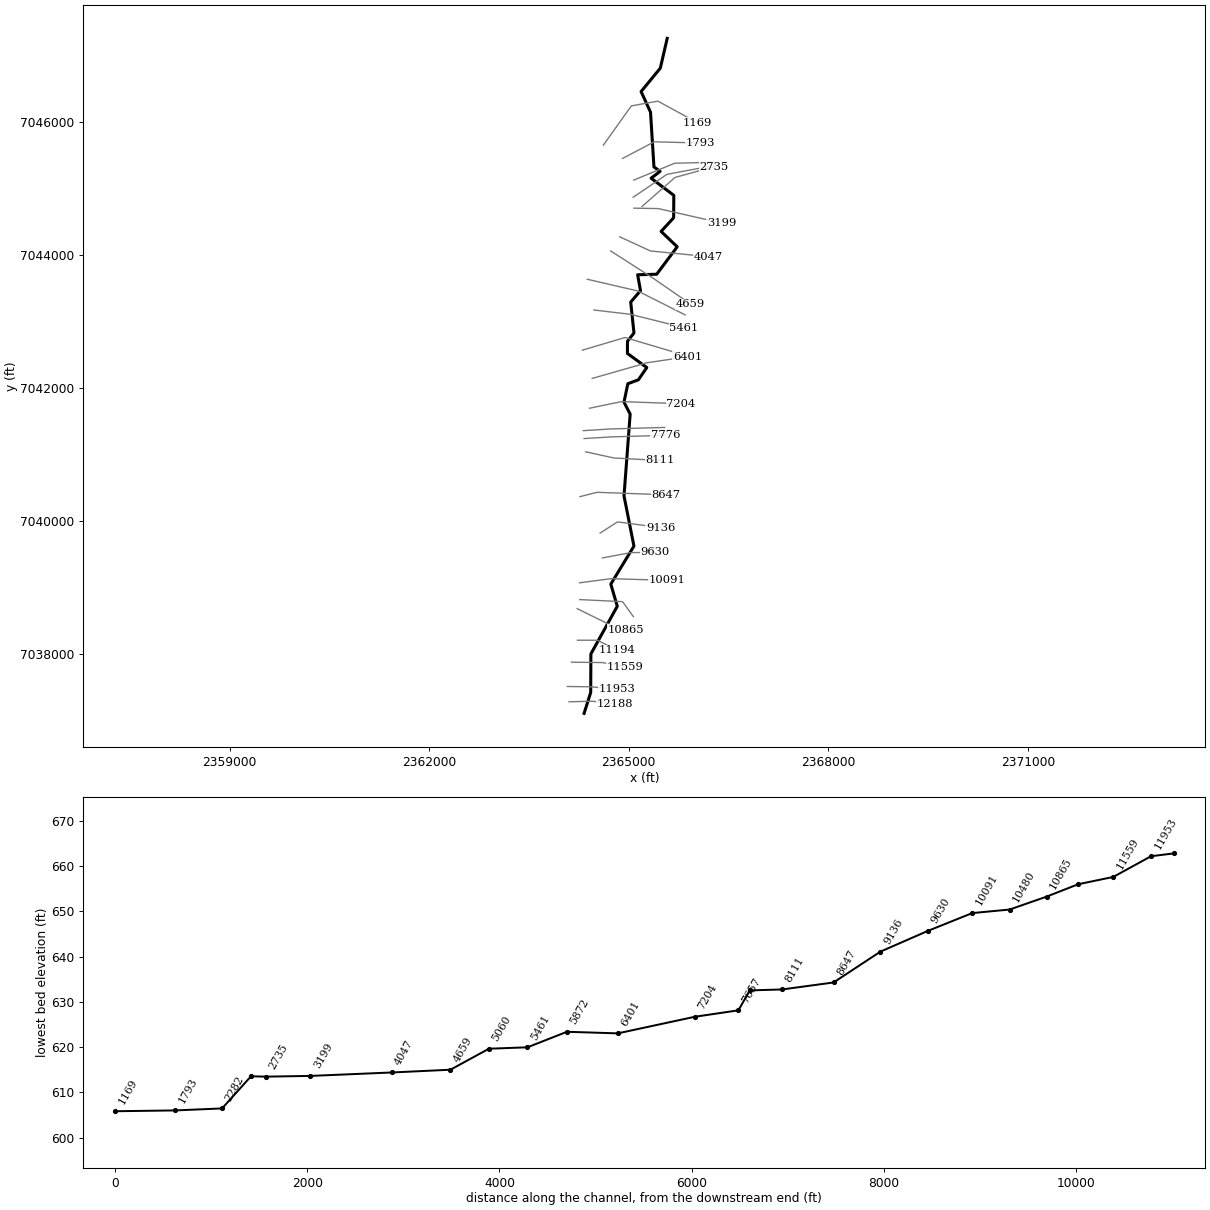
--- LWE S 007.prj (project) ---

Proj Title=LWE S 007 Base Level Engineering
Current Plan=p01
Default Exp/Contr=0.3,0.1
English Units
Geom File=g01
Flow File=f01
Plan File=p01
Y Axis Title=Elevation
X Axis Title(PF)=Main Channel Distance
X Axis Title(XS)=Station
BEGIN DESCRIPTION:
LWE S 007
END DESCRIPTION:
DSS Export Rating Curves= 0
DSS Export Rating Curve Sorted= 0
DSS Export Volume Flow Curves= 0
DXF OffsetX= 0
DXF OffsetY= 0
DXF ScaleX= 1
DXF ScaleY= 10

--- LWE S 007.p01 (plan) ---

Plan Title=Multiple Run
Program Version=4.10
Short Identifier=Multiple
Geom File=g01
Flow File=f01
Subcritical Flow
K Sum by GR= 0
Std Step Tol= 0.01
Critical Tol= 0.01
Num of Std Step Trials= 20
Max Error Tol= 0.3
Flow Tol Ratio= 0.001
Split Flow NTrial= 30
Split Flow Tol= 0.02
Split Flow Ratio= 0.02
Log Output Level= 0
Friction Slope Method= 1
Unsteady Friction Slope Method= 2
Unsteady Bridges Friction Slope Method= 1
Parabolic Critical Depth
Global Vel Dist= 1 , 1 , 1
Global Log Level= 0
CheckData=True
Encroach Param=-1 ,0,0, 0
BEGIN DESCRIPTION:
Multiple Run
END DESCRIPTION:
Computation Interval=1HOUR
Output Interval=1HOUR
Run HTab= 0
Run UNet= 0
Run PostProcess= 0
Run WQNet= 0
UNET Theta= 1
UNET Theta Warmup= 1
UNET ZTol= 0.02
UNET ZSATol= 0.05
UNET MxIter= 20
UNET MaxInSteps= 0
UNET DtIC= 0
UNET DtMin= 0
UNET MaxCRTS= 20
UNET WFStab= 2
UNET SFStab= 1
UNET WFX= 1
UNET SFX= 1
UNET DSS MLevel= 4
UNET DZMax Abort= 100
UNET Convert EG Bridges= 0
UNET Use Existing IB Tables=-1
UNET Froude Reduction=False
UNET Froude Limit= 1
UNET Froude Power= 10
UNET Time Slicing=0,0, 5
UNET Junction Losses=0
Instantaneous Interval=1HOUR
Write IC File= 0
Write IC File at Sim End=0
Echo Input=False
Echo Parameters=False
Echo Output=False
Write Detailed= 0
WQ AD Non Conservative
WQ ULTIMATE=-1
WQ Max Comp Step=1HOUR
WQ Output Interval=15MIN
WQ Output Selected Increments= 0
WQ Output face flow=0
WQ Output face velocity=0
WQ Output face area=0
WQ Output face dispersion=0
WQ Output cell volume=0
WQ Output cell surface area=0
WQ Output cell continuity=0
WQ Output cumulative cell continuity=0
WQ Output face conc=0
WQ Output face dconc_dx=0
WQ Output face courant=0
WQ Output face peclet=0
WQ Output face adv mass=0
WQ Output face disp mass=0
WQ Output cell mass=0
WQ Output cell source sink temp=0
WQ Output cell source sink nsm=0
WQ Output MaxMinRange=-1
WQ Daily Max Min Mean=-1
WQ Daily Range=0
WQ Daily Time=0
WQ Create Restart=0
WQ Fixed Restart=0
WQ System Summary=0
WQ Use Fixed Temperature=0
Sorting and Armoring Iterations= 10
XS Update Threshold= 0.02
Hydraulics Update Threshold= 0.02
Energy Slope Method= 1
Volume Change Method= 0
XS Weighting Method= 0
Number of US Weighted Cross Sections= 1
Number of DS Weighted Cross Sections= 1
Upstream XS Weight=0.25
Main XS Weight=0.5
Downstream XS Weight=0.25
Number of DS XS's Weighted with US Boundary= 1
Upstream Boundary Weight= 1
Weight of XSs Associated with US Boundary= 0
Number of US XS's Weighted with DS Boundary= 1
Downstream Boundary Weight= 0.5
Weight of XSs Associated with DS Boundary= 0.5
Sediment Output Level= 4
Mass or Volume Output= 0
Output Increment Type= 1
Profile and TS Output Increment= 10
XS Output Flag= 0
XS Output Increment= 10
Disregard all LS=0
Disregard all Conn=0
Disregard all Breaches=0
Disregard all Pumps=0

--- LWE S 007.f01 (steady flow) ---

Flow Title=Multiple
Number of Profiles=7
Profile Names=10-year,25-year,50-year,1pct_min,100-year,1pct_plu,500-year
River Rch & RM= LWE S 007,Reach-1,12188
     675     931    1143     697    1391    2775    2057
River Rch & RM= LWE S 007,Reach-1,10480
    1203    1710    2144    1330    2655    5297    4071
River Rch & RM= LWE S 007,Reach-1,5461
    1364    1942    2436    1512    3017    6019    4627
Boundary for River Rch & Prof#=LWE S 007,Reach-1,1
Up Type=0
Dn Type=3
Dn Slope=0.005
Boundary for River Rch & Prof#=LWE S 007,Reach-1,2
Up Type=0
Dn Type=3
Dn Slope=0.005
Boundary for River Rch & Prof#=LWE S 007,Reach-1,3
Up Type=0
Dn Type=3
Dn Slope=0.005
Boundary for River Rch & Prof#=LWE S 007,Reach-1,4
Up Type=0
Dn Type=3
Dn Slope=0.005
Boundary for River Rch & Prof#=LWE S 007,Reach-1,5
Up Type=0
Dn Type=3
Dn Slope=0.005
Boundary for River Rch & Prof#=LWE S 007,Reach-1,6
Up Type=0
Dn Type=3
Dn Slope=0.005
Boundary for River Rch & Prof#=LWE S 007,Reach-1,7
Up Type=0
Dn Type=3
Dn Slope=0.005

--- LWE S 007.g01 (geometry) ---

Geom Title=Existing Conditions

River Reach=LWE S 007,Reach-1
Reach XY= 30
      2364329.00      7037110.00      2364428.48      7037425.22
      2364431.23      7038004.07      2364827.91      7038720.54
      2364730.82      7039053.88      2365078.61      7039625.16
      2364929.07      7040380.03      2365021.67      7041610.10
      2364928.90      7041789.90      2364986.81      7042066.23
      2365146.04      7042126.24      2365271.92      7042310.00
      2364980.62      7042521.81      2364981.06      7042704.14
      2365079.06      7042829.99      2365029.92      7043294.06
      2365177.37      7043466.04      2365134.02      7043704.92
      2365420.66      7043712.98      2365729.01      7044125.47
      2365486.82      7044356.73      2365675.46      7044561.46
      2365677.96      7044899.57      2365336.51      7045156.85
      2365472.07      7045259.99      2365379.56      7045325.89
      2365327.78      7046149.50      2365186.08      7046460.01
      2365475.17      7046811.58      2365579.00      7047260.00

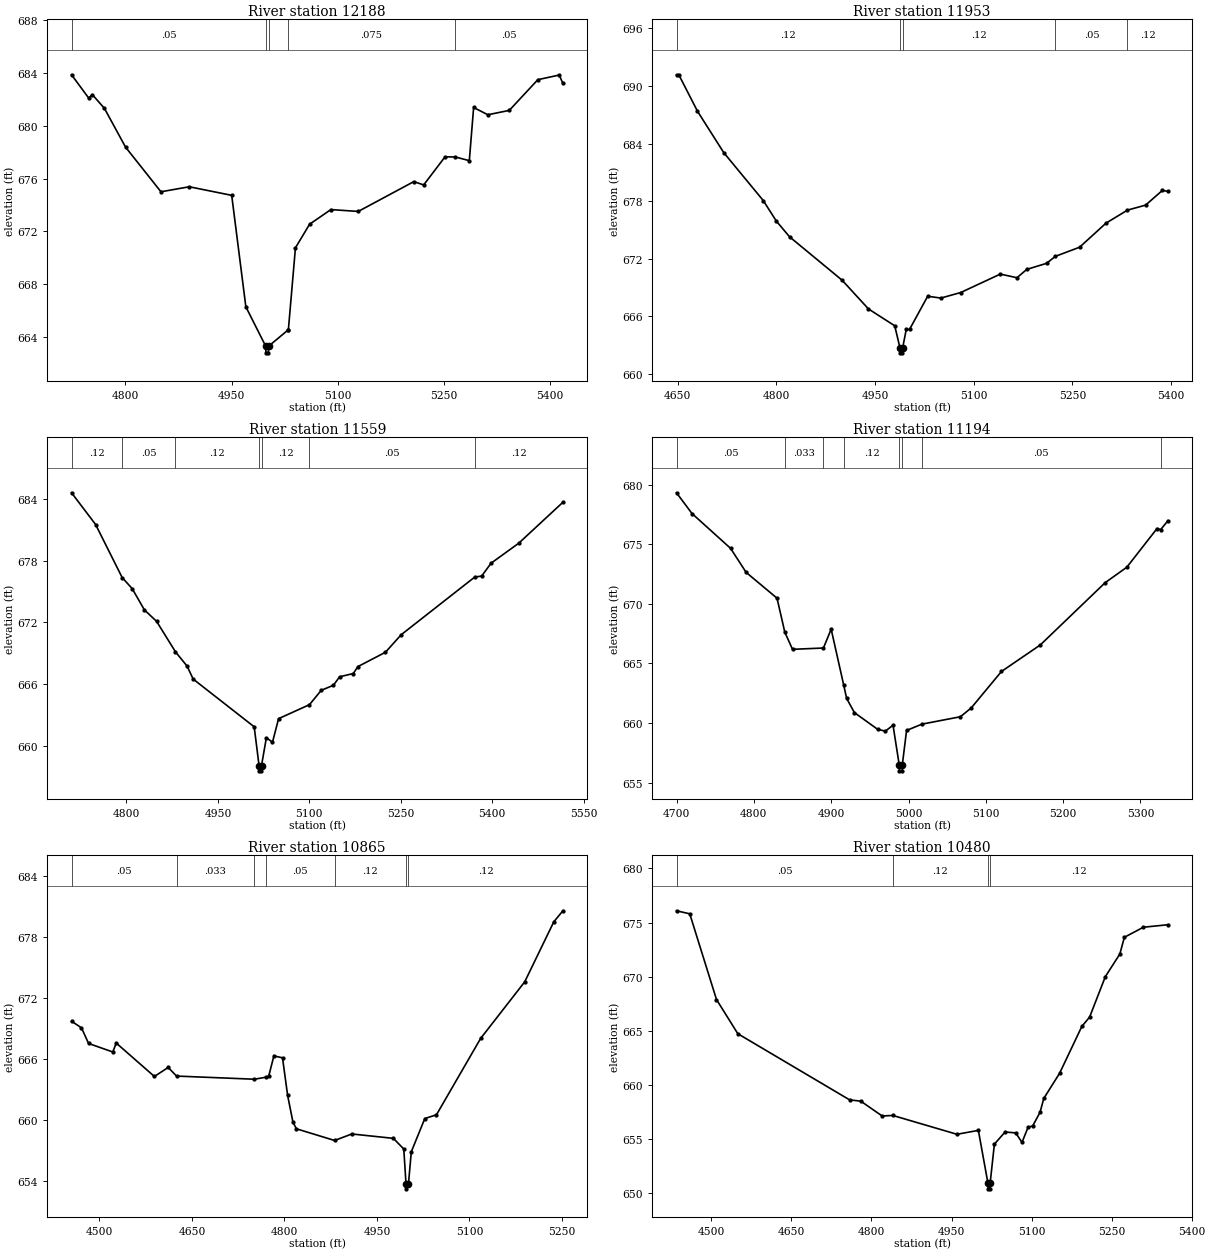
Type RM Length L Ch R = 1,12188,235,235,235
BEGIN DESCRIPTION:
LWE S 007 21.0
END DESCRIPTION:
XS GIS Cut Line= 3
      2364102.62      7037284.34      2364451.33      7037292.84
      2364794.14      7037247.51
#Sta/Elev= 30
  4723.8  683.88  4748.1  682.11  4753.1  682.38  4770.2  681.34  4800.2  678.39
  4850.2  675.01  4890.2  675.39  4950.2  674.74  4970.2  666.29  4998.3  663.30
  4998.5  662.80  5002.0  662.80  5002.3  663.30  5029.4  664.51  5030.3  664.54
  5040.3  670.76  5060.3  672.55  5090.4  673.66  5129.1  673.52  5207.6  675.78
  5221.6  675.53  5251.8  677.66  5266.2  677.65  5286.1  677.37  5292.2  681.40
  5312.3  680.85  5342.6  681.18  5383.0  683.51  5413.2  683.86  5418.4  683.22
#Mann=5,-1,0
  4723.8    0.05       0  4998.3    0.05       0  5002.3    0.05       0
  5029.4   0.075       0  5266.2    0.05       0
Bank Sta=4998.3,5002.3
Exp/Cntr=0.3,0.1

Type RM Length L Ch R = 1,11953,394,394,394
BEGIN DESCRIPTION:
LWE S 007 20.0
END DESCRIPTION:
XS GIS Cut Line= 3
      2364077.10      7037513.97      2364429.00      7037510.00
      2364822.76      7037474.28
#Sta/Elev= 30
  4648.0  691.17  4651.5  691.17  4679.9  687.37  4719.9  683.05  4779.9  678.06
  4799.9  675.91  4819.9  674.28  4899.9  669.75  4939.9  666.76  4979.9  665.00
  4987.9  662.68  4988.2  662.18  4991.7  662.18  4991.9  662.68  4997.4  664.62
  5002.4  664.62  5030.0  668.08  5050.1  667.89  5080.3  668.47  5140.5  670.39
  5165.8  670.01  5180.7  670.88  5210.8  671.51  5224.2  672.24  5261.0  673.19
  5301.2  675.70  5333.9  677.06  5361.4  677.58  5386.9  679.11  5395.3  679.02
#Mann=5,-1,0
  4648.0    0.12       0  4987.9    0.07       0  4991.9    0.12       0
  5224.2    0.05       0  5333.9    0.12       0
Bank Sta=4987.9,4991.9
Exp/Cntr=0.3,0.1

Type RM Length L Ch R = 1,11559,365,365,365
BEGIN DESCRIPTION:
LWE S 007 19.0
END DESCRIPTION:
XS GIS Cut Line= 3
      2364139.47      7037879.68      2364601.59      7037874.01
      2364940.29      7037814.74
#Sta/Elev= 30
  4709.9  684.57  4749.4  681.49  4792.9  676.35  4809.4  675.27  4829.4  673.21
  4849.4  672.10  4880.4  669.14  4899.4  667.76  4909.4  666.50  5009.5  661.87
  5017.5  658.10  5017.7  657.60  5021.2  657.60  5021.5  658.10  5029.5  660.82
  5039.5  660.37  5049.5  662.66  5100.2  664.02  5119.5  665.41  5139.5  665.90
  5149.5  666.72  5172.1  667.04  5179.6  667.71  5224.8  669.10  5250.6  670.80
  5371.4  676.40  5382.6  676.49  5398.1  677.74  5443.5  679.68  5515.9  683.65
#Mann=7,-1,0
  4709.9    0.12       0  4792.9    0.05       0  4880.4    0.12       0
  5017.5    0.07       0  5021.5    0.12       0  5100.2    0.05       0
  5371.4    0.12       0
Bank Sta=5017.5,5021.5
Exp/Cntr=0.3,0.1

Type RM Length L Ch R = 1,11194,329,329,329
BEGIN DESCRIPTION:
LWE S 007 18.0
END DESCRIPTION:
XS GIS Cut Line= 3
      2364229.00      7038210.00      2364529.00      7038210.00
      2364828.99      7038060.00
#Sta/Elev= 30
  4700.0  679.33  4720.0  677.59  4770.0  674.66  4790.0  672.65  4830.0  670.48
  4840.0  667.64  4850.0  666.19  4890.0  666.30  4900.0  667.88  4916.3  663.16
  4920.0  662.07  4930.0  660.88  4960.0  659.48  4970.0  659.32  4980.0  659.82
  4988.0  656.49  4988.3  655.99  4991.8  655.99  4992.0  656.49  4997.5  659.38
  5017.4  659.91  5067.1  660.53  5081.1  661.27  5120.2  664.33  5170.5  666.56
  5254.4  671.79  5282.3  673.08  5321.4  676.33  5326.1  676.24  5335.4  676.98
#Mann=8,-1,0
  4700.0    0.05       0  4840.0   0.033       0  4890.0    0.05       0
  4916.3    0.12       0  4988.0    0.07       0  4992.0    0.12       0
  5017.4    0.05       0  5326.1    0.12       0
Bank Sta=4988,4992
Exp/Cntr=0.3,0.1

Type RM Length L Ch R = 1,10865,385,385,385
BEGIN DESCRIPTION:
LWE S 007 17.0
END DESCRIPTION:
XS GIS Cut Line= 3
      2364224.51      7038684.83      2364743.34      7038429.67
      2364953.09      7038367.31
#Sta/Elev= 30
  4454.7  669.75  4470.8  669.10  4482.3  667.56  4521.6  666.72  4527.2  667.60
  4589.1  664.31  4611.5  665.20  4625.0  664.35  4751.2  664.04  4770.3  664.24
  4774.4  664.32  4782.9  666.33  4796.9  666.15  4805.2  662.44  4813.8  659.82
  4819.4  659.16  4881.4  658.01  4909.3  658.65  4976.7  658.22  4993.6  657.17
  4997.2  653.75  4997.4  653.25  5001.2  653.75  5005.8  656.90  5027.7  660.17
  5046.6  660.54  5118.2  668.05  5189.8  673.63  5237.0  679.54  5251.7  680.62
#Mann=7,-1,0
  4454.7    0.05       0  4625.0   0.033       0  4751.2    0.12       0
  4770.3    0.05       0  4881.4    0.12       0  4997.2    0.07       0
  5001.2    0.12       0
Bank Sta=4997.2,5001.2
Exp/Cntr=0.3,0.1

Type RM Length L Ch R = 1,10480,389,389,389
BEGIN DESCRIPTION:
LWE S 007 16.0
END DESCRIPTION:
XS GIS Cut Line= 3
      2364264.20      7038820.89      2364907.77      7038789.71
      2365069.36      7038565.74
#Sta/Elev= 30
  4434.8  676.09  4459.6  675.81  4509.7  667.89  4549.7  664.73  4759.1  658.62
  4780.0  658.50  4820.1  657.13  4840.0  657.18  4960.2  655.44  5000.3  655.80
  5018.3  650.90  5018.5  650.40  5022.0  650.40  5022.3  650.90  5030.3  654.53
  5050.3  655.65  5070.3  655.57  5082.0  654.69  5093.5  656.10  5102.1  656.21
  5115.8  657.47  5122.9  658.76  5152.4  661.07  5194.1  665.40  5208.8  666.28
  5238.2  670.01  5265.3  672.09  5273.8  673.64  5309.4  674.57  5355.3  674.80
#Mann=4,-1,0
  4434.8    0.05       0  4840.0    0.12       0  5018.3    0.07       0
  5022.3    0.12       0
Bank Sta=5018.3,5022.3
Exp/Cntr=0.3,0.1

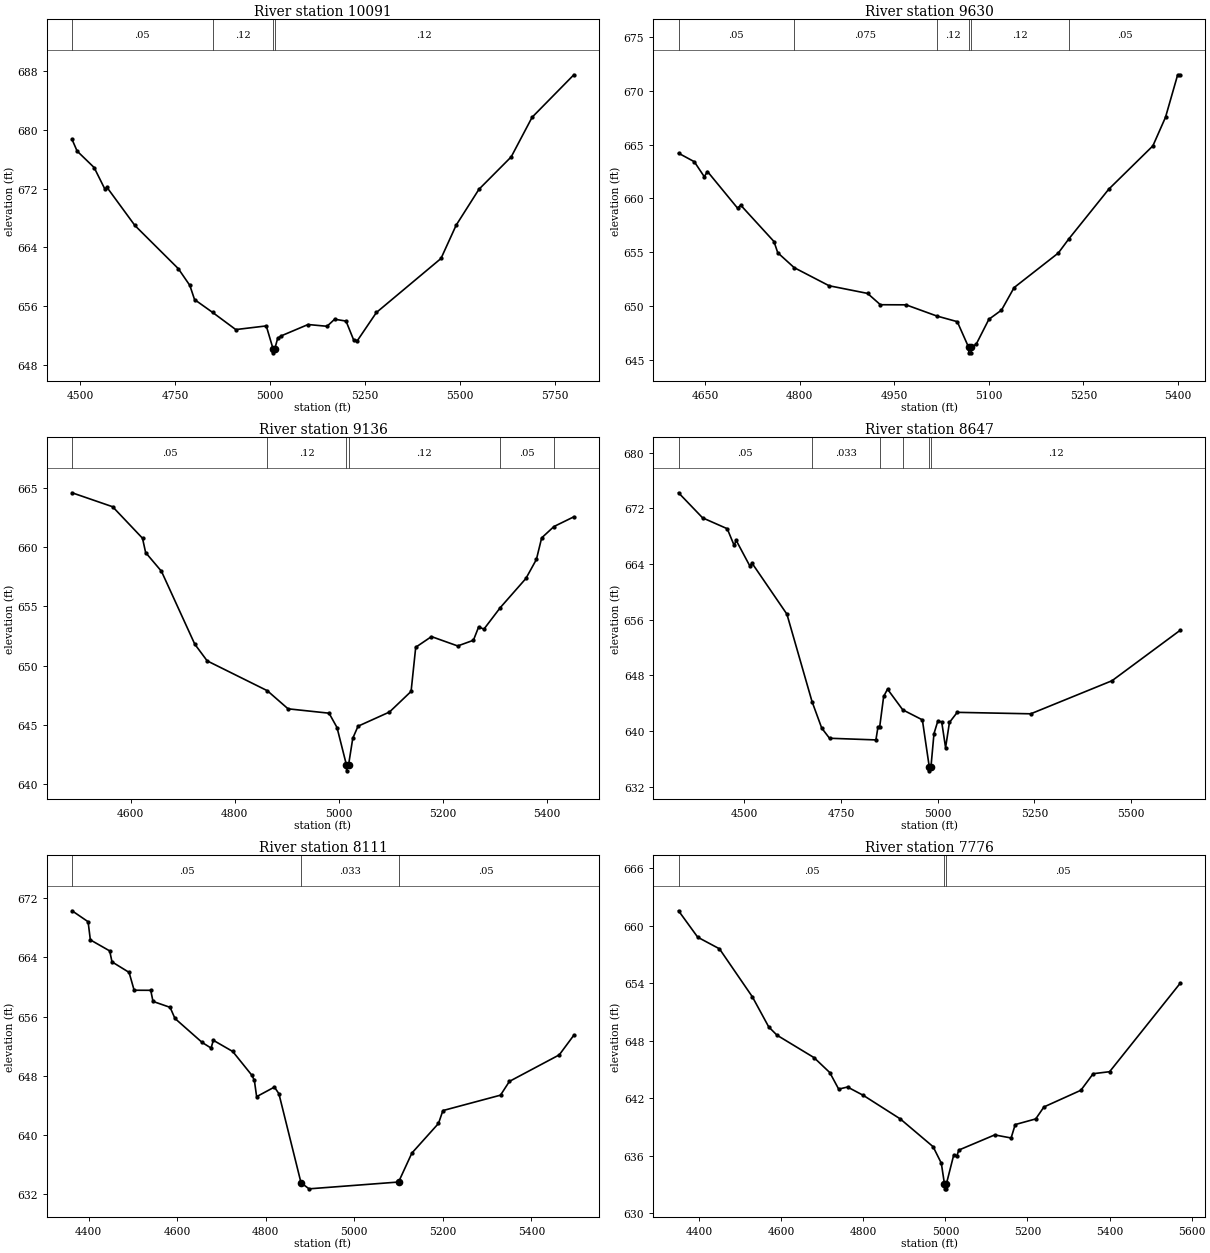
Type RM Length L Ch R = 1,10091,461,461,461
BEGIN DESCRIPTION:
LWE S 007 15.0
END DESCRIPTION:
XS GIS Cut Line= 3
      2364261.36      7039073.20      2364734.83      7039135.57
      2365578.99      7039110.00
#Sta/Elev= 30
  4478.3  678.70  4491.6  677.12  4536.4  674.88  4565.1  671.90  4570.2  672.18
  4643.8  666.98  4758.3  661.09  4788.6  658.81  4801.0  656.88  4848.6  655.13
  4909.6  652.79  4990.0  653.29  5008.1  650.12  5008.3  649.62  5012.1  650.12
  5020.1  651.61  5030.1  651.95  5100.1  653.48  5150.1  653.24  5170.1  654.20
  5200.1  653.95  5220.1  651.39  5230.2  651.30  5280.2  655.12  5450.3  662.48
  5490.3  667.02  5550.3  671.91  5635.3  676.33  5690.4  681.73  5800.4  687.52
#Mann=4,-1,0
  4478.3    0.05       0  4848.6    0.12       0  5008.1    0.07       0
  5012.1    0.12       0
Bank Sta=5008.1,5012.1
Exp/Cntr=0.3,0.1

Type RM Length L Ch R = 1,9630,494,494,494
BEGIN DESCRIPTION:
LWE S 007 14.0
END DESCRIPTION:
XS GIS Cut Line= 3
      2364604.40      7039447.42      2365029.67      7039526.80
      2365392.51      7039532.47
#Sta/Elev= 30
  4608.2  664.20  4633.2  663.41  4649.0  662.02  4654.1  662.50  4701.7  659.11
  4706.8  659.38  4759.5  656.01  4765.5  654.97  4791.5  653.59  4846.9  651.91
  4907.9  651.20  4928.2  650.15  4968.9  650.14  5017.4  649.11  5050.1  648.58
  5068.2  646.19  5068.4  645.69  5071.9  645.69  5072.2  646.19  5080.2  646.50
  5100.2  648.80  5120.2  649.65  5140.2  651.74  5210.2  654.94  5226.9  656.25
  5290.2  660.86  5360.2  664.88  5380.2  667.53  5399.5  671.47  5403.7  671.47
#Mann=6,-1,0
  4608.2    0.05       0  4791.5   0.075       0  5017.4    0.12       0
  5068.2    0.07       0  5072.2    0.12       0  5226.9    0.05       0
Bank Sta=5068.2,5072.2
Exp/Cntr=0.3,0.1

Type RM Length L Ch R = 1,9136,489,489,489
BEGIN DESCRIPTION:
LWE S 007 13.0
END DESCRIPTION:
XS GIS Cut Line= 3
      2364570.39      7039821.63      2364831.22      7039988.90
      2365480.42      7039903.85
#Sta/Elev= 30
  4487.2  664.60  4565.2  663.42  4622.6  660.76  4628.6  659.55  4659.0  657.97
  4723.1  651.81  4746.9  650.40  4862.5  647.88  4902.4  646.35  4981.2  645.98
  4996.5  644.77  5014.6  641.61  5014.9  641.11  5018.7  641.61  5026.8  643.86
  5036.9  644.88  5097.4  646.08  5138.9  647.82  5147.8  651.55  5178.1  652.45
  5228.5  651.66  5258.7  652.14  5268.8  653.27  5278.9  653.08  5310.4  654.90
  5359.6  657.36  5379.8  658.97  5389.9  660.79  5413.6  661.75  5451.8  662.57
#Mann=6,-1,0
  4487.2    0.05       0  4862.5    0.12       0  5014.6    0.07       0
  5018.7    0.12       0  5310.4    0.05       0  5413.6    0.12       0
Bank Sta=5014.6,5018.7
Exp/Cntr=0.3,0.1

Type RM Length L Ch R = 1,8647,536,536,536
BEGIN DESCRIPTION:
LWE S 007 12.0
END DESCRIPTION:
XS GIS Cut Line= 3
      2364267.03      7040368.78      2364522.21      7040433.99
      2365555.47      7040397.19
#Sta/Elev= 30
  4329.9  674.22  4392.1  670.62  4455.8  669.06  4473.7  666.66  4478.9  667.39
  4514.6  663.67  4519.7  664.13  4610.1  656.79  4675.0  644.24  4700.1  640.43
  4720.2  638.97  4840.2  638.73  4845.6  640.62  4850.0  640.62  4860.2  644.97
  4870.2  646.02  4909.6  643.05  4960.3  641.61  4978.3  634.79  4978.6  634.29
  4982.4  634.79  4990.3  639.63  5000.3  641.45  5010.3  641.31  5020.3  637.62
  5030.3  641.24  5050.4  642.69  5240.5  642.48  5450.6  647.23  5627.2  654.49
#Mann=6,-1,0
  4329.9    0.05       0  4675.0   0.033       0  4850.0    0.05       0
  4909.6    0.12       0  4978.3    0.07       0  4982.4    0.12       0
Bank Sta=4978.3,4982.4
Exp/Cntr=0.3,0.1

Type RM Length L Ch R = 1,8111,335,335,335
BEGIN DESCRIPTION:
LWE S 007 11.0
END DESCRIPTION:
XS GIS Cut Line= 3
      2364352.06      7041043.52      2364777.36      7040949.96
      2365474.42      7040913.12
#Sta/Elev= 30
  4362.6  670.30  4398.8  668.82  4403.9  666.37  4447.6  664.88  4452.8  663.40
  4491.4  661.98  4502.8  659.57  4540.3  659.56  4545.4  658.06  4584.0  657.26
  4595.0  655.76  4656.4  652.52  4676.6  651.76  4681.7  652.81  4725.5  651.30
  4769.0  648.07  4774.4  647.39  4779.5  645.20  4819.7  646.49  4829.8  645.60
  4879.8  633.56  4898.0  632.75  5100.1  633.67  5130.2  637.58  5190.3  641.58
  5200.3  643.32  5330.4  645.40  5350.5  647.26  5463.1  650.84  5496.1  653.50
#Mann=3,-1,0
  4362.6    0.05       0  4879.8   0.033       0  5100.1    0.05       0
Bank Sta=4879.8,5100.1
Exp/Cntr=0.3,0.1

Type RM Length L Ch R = 1,7776,119,119,119
BEGIN DESCRIPTION:
LWE S 007 10.2
END DESCRIPTION:
XS GIS Cut Line= 3
      2364329.48      7041241.96      2364740.50      7041267.47
      2365551.27      7041290.15
#Sta/Elev= 30
  4349.6  661.57  4396.4  658.81  4449.3  657.60  4529.5  652.59  4569.5  649.44
  4589.6  648.58  4679.8  646.24  4718.2  644.68  4739.9  642.95  4761.4  643.17
  4799.9  642.30  4890.0  639.84  4970.0  636.94  4990.0  635.22  4997.7  633.04
  4998.2  632.54  5001.8  632.54  5002.3  633.04  5020.0  636.03  5027.8  635.98
  5032.8  636.59  5120.1  638.17  5160.1  637.85  5170.1  639.25  5220.1  639.84
  5240.1  641.09  5330.1  642.83  5360.1  644.56  5400.2  644.77  5572.5  654.02
#Mann=3,-1,0
  4349.6    0.05       0  4997.7   0.033       0  5002.3    0.05       0
Bank Sta=4997.7,5002.3
Exp/Cntr=0.3,0.1

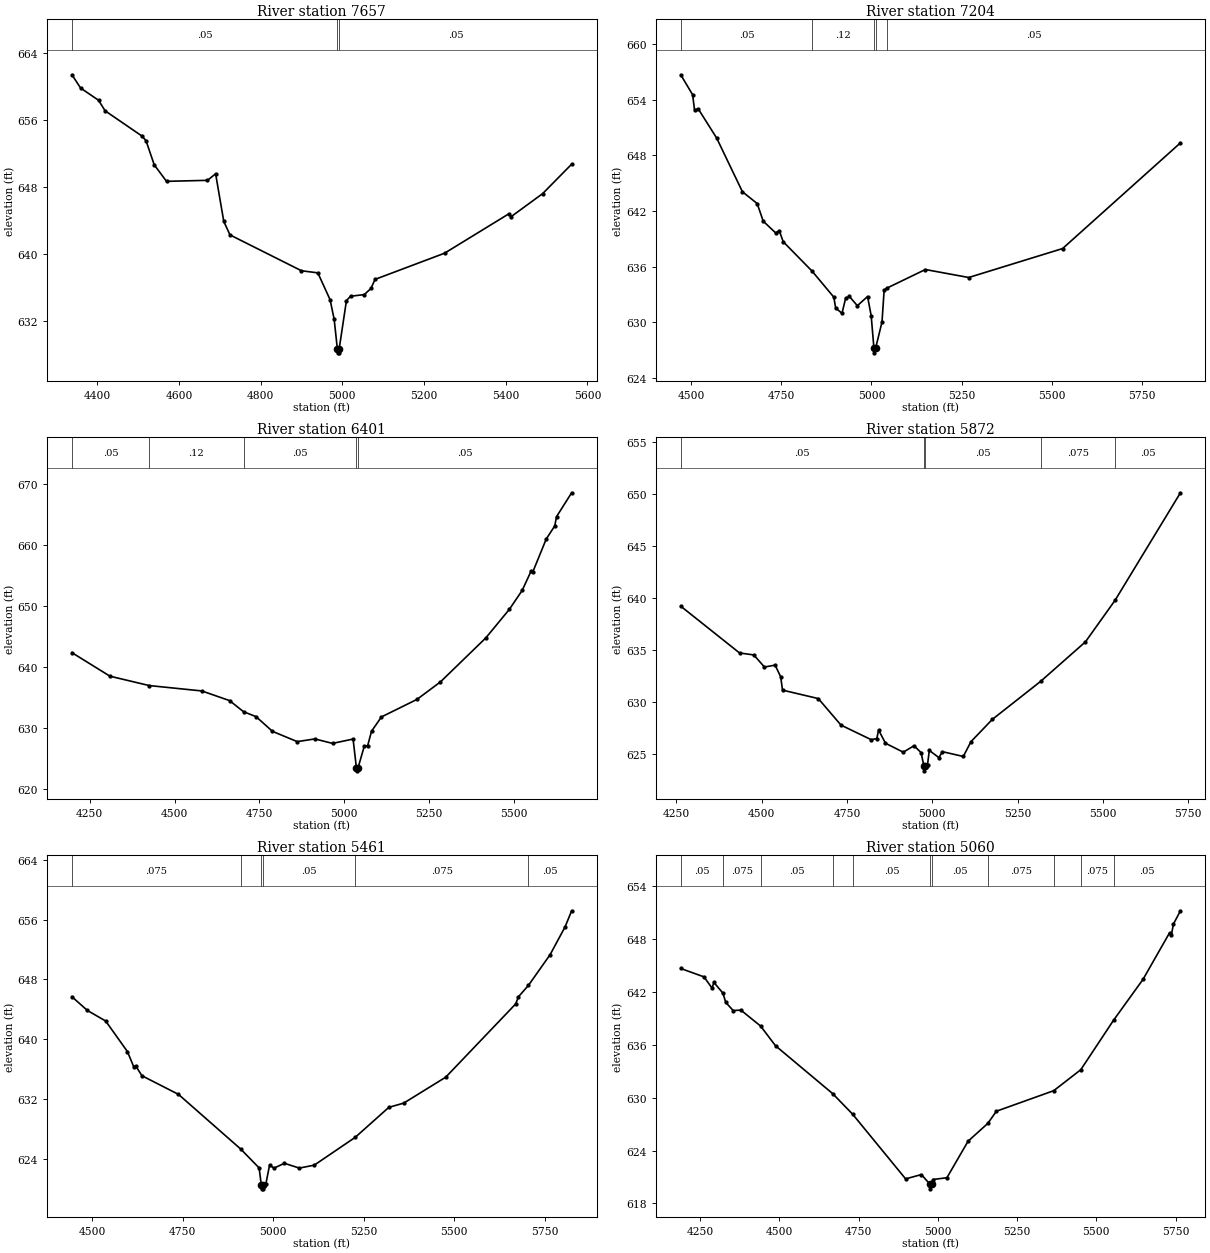
Type RM Length L Ch R = 1,7657,453,453,453
BEGIN DESCRIPTION:
LWE S 007 10.0
END DESCRIPTION:
XS GIS Cut Line= 3
      2364318.07      7041361.03      2364729.16      7041386.54
      2365539.96      7041409.22
#Sta/Elev= 30
  4338.2  661.41  4359.2  659.83  4403.3  658.36  4419.3  657.10  4509.5  654.08
  4519.5  653.52  4539.5  650.64  4569.6  648.66  4669.8  648.78  4689.8  649.56
  4709.8  643.86  4725.0  642.25  4900.0  637.96  4940.0  637.71  4970.0  634.49
  4980.0  632.14  4987.7  628.64  4988.2  628.14  4991.9  628.14  4992.3  628.64
  5010.0  634.39  5020.0  634.91  5053.8  635.11  5070.0  635.85  5080.0  636.93
  5250.1  640.06  5407.7  644.78  5412.7  644.42  5490.2  647.19  5561.2  650.71
#Mann=3,-1,0
  4338.2    0.05       0  4987.7   0.033       0  4992.3    0.05       0
Bank Sta=4987.7,4992.3
Exp/Cntr=0.3,0.1

Type RM Length L Ch R = 1,7204,803,803,803
BEGIN DESCRIPTION:
LWE S 007 9.0
END DESCRIPTION:
XS GIS Cut Line= 3
      2364411.60      7041698.38      2364890.76      7041797.61
      2365785.29      7041766.47
#Sta/Elev= 30
  4471.8  656.69  4504.7  654.54  4510.0  652.89  4520.2  653.02  4571.3  649.87
  4642.7  644.08  4683.6  642.81  4700.3  640.91  4734.7  639.65  4744.9  639.87
  4755.6  638.70  4835.8  635.52  4895.9  632.72  4901.0  631.55  4918.5  630.98
  4928.7  632.61  4938.9  632.80  4961.1  631.80  4989.4  632.79  4999.4  630.72
  5007.0  627.22  5007.5  626.72  5011.7  627.22  5029.4  630.05  5035.3  633.48
  5042.1  633.68  5149.5  635.70  5269.6  634.84  5529.7  637.96  5856.2  649.35
#Mann=5,-1,0
  4471.8    0.05       0  4835.8    0.12       0  5007.0    0.07       0
  5011.7    0.12       0  5042.1    0.05       0
Bank Sta=5007,5011.7
Exp/Cntr=0.3,0.1

Type RM Length L Ch R = 1,6401,529,529,529
BEGIN DESCRIPTION:
LWE S 007 8.0
END DESCRIPTION:
XS GIS Cut Line= 3
      2364451.34      7042146.32      2365273.48      7042381.62
      2365883.01      7042472.34
#Sta/Elev= 30
  4198.0  642.38  4310.0  638.53  4425.7  637.00  4580.4  636.12  4662.1  634.54
  4703.3  632.72  4740.0  631.92  4788.5  629.51  4861.3  627.83  4913.3  628.27
  4965.3  627.54  5025.8  628.25  5035.6  623.55  5036.2  623.05  5040.5  623.55
  5058.7  627.08  5068.8  627.18  5080.1  629.53  5109.3  631.87  5213.7  634.73
  5283.1  637.60  5416.7  644.80  5486.1  649.48  5523.8  652.57  5550.4  655.78
  5555.4  655.64  5594.6  660.98  5619.7  663.12  5624.9  664.63  5669.4  668.54
#Mann=5,-1,0
  4198.0    0.05       0  4425.7    0.12       0  4703.3    0.05       0
  5035.6    0.04       0  5040.5    0.05       0
Bank Sta=5035.6,5040.5
Exp/Cntr=0.3,0.1

Type RM Length L Ch R = 1,5872,411,411,411
BEGIN DESCRIPTION:
LWE S 007 7.0
END DESCRIPTION:
XS GIS Cut Line= 3
      2364303.92      7042571.56      2364944.62      7042761.50
      2365707.25      7042534.70
#Sta/Elev= 30
  4263.1  639.21  4435.3  634.72  4477.0  634.53  4508.3  633.37  4539.6  633.55
  4555.9  632.43  4561.2  631.15  4666.1  630.34  4732.6  627.79  4821.2  626.39
  4837.5  626.50  4842.7  627.32  4862.9  626.05  4915.1  625.19  4946.4  625.81
  4967.2  625.15  4975.2  623.90  4975.8  623.40  4980.1  623.90  4986.1  624.00
  4991.3  625.36  5019.3  624.67  5029.8  625.24  5090.9  624.78  5113.3  626.20
  5175.9  628.34  5317.4  631.99  5448.8  635.79  5535.6  639.78  5727.0  650.10
#Mann=5,-1,0
  4263.1    0.05       0  4975.2   0.033       0  4980.1    0.05       0
  5317.4   0.075       0  5535.6    0.05       0
Bank Sta=4975.2,4980.1
Exp/Cntr=0.3,0.1

Type RM Length L Ch R = 1,5461,401,401,401
BEGIN DESCRIPTION:
LWE S 007 6.0
END DESCRIPTION:
XS GIS Cut Line= 3
      2364476.88      7043175.41      2365029.00      7043110.00
      2365829.00      7042910.00
#Sta/Elev= 30
  4444.1  645.69  4486.5  643.86  4537.2  642.44  4597.3  638.35  4615.0  636.29
  4620.0  636.44  4637.6  635.11  4738.3  632.62  4910.3  625.30  4961.2  622.77
  4967.3  620.47  4968.0  619.97  4971.8  619.97  4972.4  620.47  4979.9  620.64
  4990.0  623.13  5002.7  622.75  5031.0  623.39  5072.2  622.75  5113.5  623.14
  5226.6  626.86  5319.6  630.88  5360.8  631.45  5476.8  634.92  5670.1  644.73
  5677.8  645.69  5705.3  647.21  5765.4  651.34  5806.7  655.06  5824.7  657.20
#Mann=6,-1,0
  4444.1   0.075       0  4910.3    0.05       0  4967.3   0.033       0
  4972.4    0.05       0  5226.6   0.075       0  5705.3    0.05       0
Bank Sta=4967.3,4972.4
Exp/Cntr=0.3,0.1

Type RM Length L Ch R = 1,5060,401,401,401
BEGIN DESCRIPTION:
LWE S 007 5.0
END DESCRIPTION:
XS GIS Cut Line= 3
      2364377.67      7043637.50      2365134.56      7043461.74
      2365848.94      7043101.72
#Sta/Elev= 30
  4188.5  644.67  4261.7  643.72  4287.7  642.43  4292.8  643.10  4321.9  641.86
  4330.3  640.83  4354.1  639.89  4378.1  639.95  4440.4  638.14  4487.6  635.90
  4668.5  630.45  4731.0  628.13  4898.2  620.79  4947.8  621.28  4975.7  620.16
  4976.4  619.66  4980.9  620.16  4983.9  620.72  5028.5  620.92  5095.4  625.07
  5157.4  627.08  5184.7  628.47  5365.6  630.80  5451.0  633.18  5554.5  638.80
  5647.5  643.44  5731.2  648.72  5736.8  648.42  5743.2  649.70  5765.5  651.22
#Mann=11,-1,0
  4188.5    0.05       0  4321.9   0.075       0  4440.4    0.05       0
  4668.5   0.075       0  4731.0    0.05       0  4975.7    0.05       0
  4980.9    0.05       0  5157.4   0.075       0  5365.6     0.1       0
  5451.0   0.075       0  5554.5    0.05       0
Bank Sta=4975.7,4980.9
Exp/Cntr=0.3,0.1

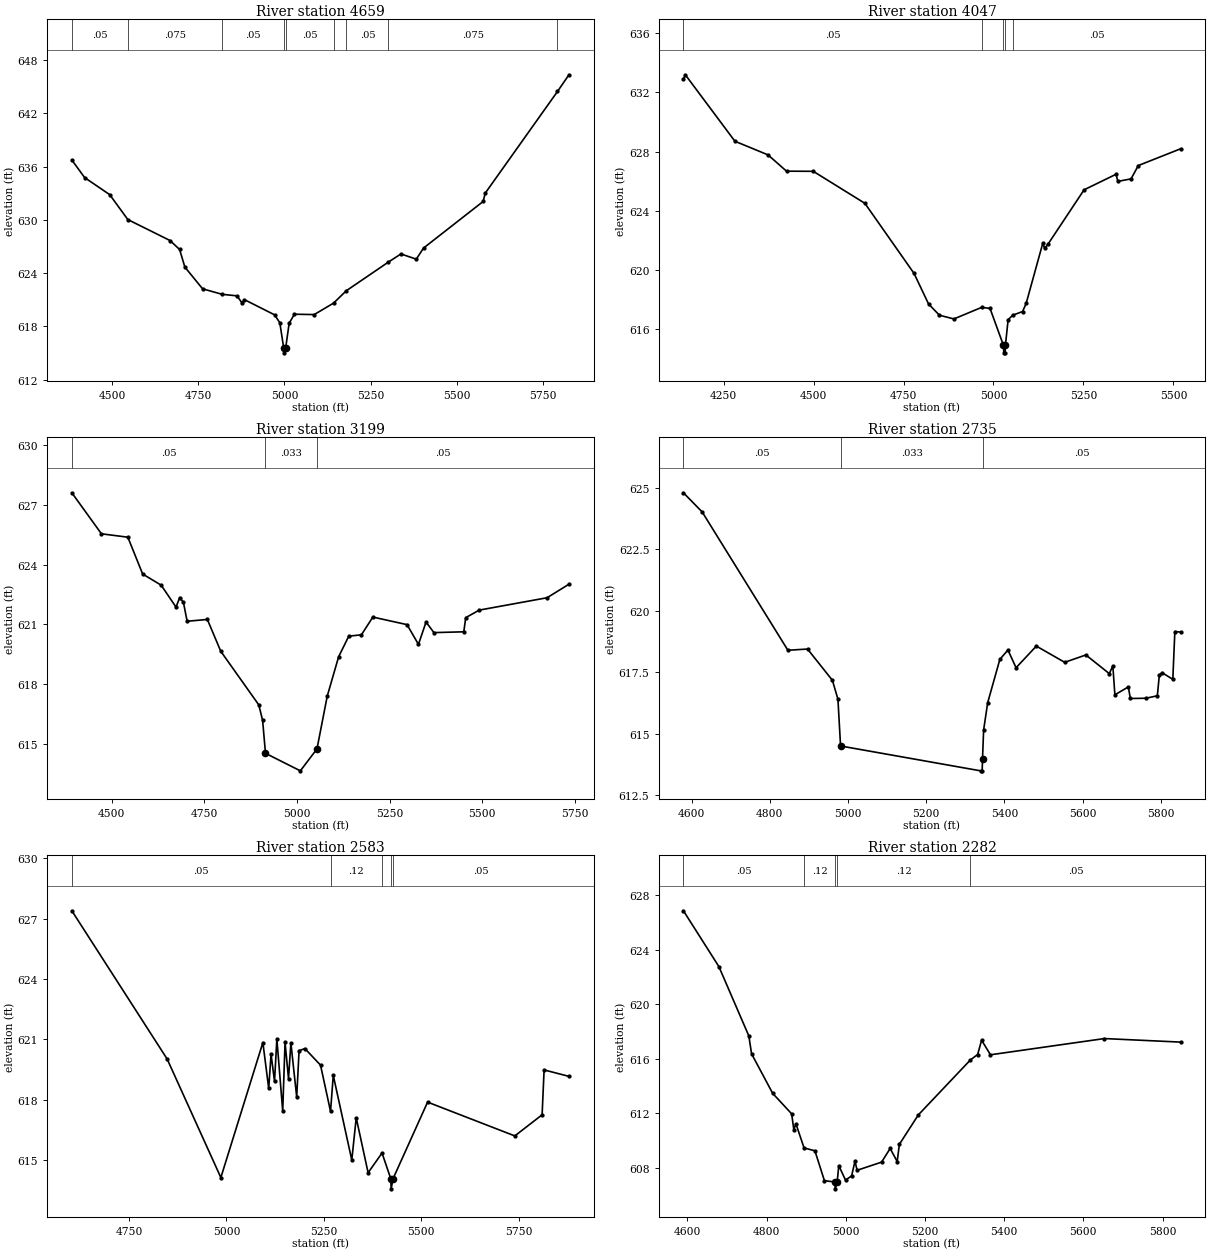
Type RM Length L Ch R = 1,4659,612,612,612
BEGIN DESCRIPTION:
LWE S 007 4.5
END DESCRIPTION:
XS GIS Cut Line= 3
      2364729.18      7044062.75      2365361.36      7043657.35
      2365929.95      7043264.15
#Sta/Elev= 30
  4383.3  636.74  4420.4  634.76  4493.1  632.84  4545.8  630.03  4668.2  627.67
  4696.0  626.66  4711.2  624.68  4762.7  622.23  4819.6  621.61  4862.5  621.44
  4877.7  620.60  4883.6  621.02  4971.5  619.30  4986.7  618.41  4998.2  615.52
  4998.9  615.02  5003.5  615.52  5013.8  618.35  5029.0  619.37  5086.5  619.33
  5142.6  620.62  5179.5  622.01  5302.0  625.25  5338.1  626.16  5382.6  625.57
  5403.6  626.82  5576.6  632.07  5582.7  633.01  5792.3  644.46  5825.6  646.34
#Mann=9,-1,0
  4383.3    0.05       0  4545.8   0.075       0  4819.6    0.05       0
  4998.2   0.033       0  5003.5    0.05       0  5142.6   0.075       0
  5179.5    0.05       0  5302.0   0.075       0  5792.3    0.05       0
Bank Sta=4998.2,5003.5
Exp/Cntr=0.3,0.1

Type RM Length L Ch R = 1,4047,848,848,848
BEGIN DESCRIPTION:
LWE S 007 4.0
END DESCRIPTION:
XS GIS Cut Line= 3
      2364865.26      7044275.37      2365327.34      7044062.76
      2366195.85      7043977.89
#Sta/Elev= 30
  4138.5  632.90  4143.8  633.19  4281.6  628.70  4373.5  627.78  4424.9  626.68
  4499.3  626.67  4642.6  624.51  4779.4  619.77  4819.6  617.71  4849.8  616.95
  4890.0  616.70  4967.1  617.48  4990.4  617.41  5027.8  614.91  5028.6  614.41
  5032.4  614.41  5033.1  614.91  5040.7  616.65  5053.4  616.95  5080.9  617.20
  5090.9  617.76  5137.2  621.83  5142.2  621.46  5151.2  621.74  5251.7  625.42
  5340.5  626.47  5345.5  625.99  5382.3  626.16  5402.4  627.06  5519.8  628.19
#Mann=5,-1,0
  4138.5    0.05       0  4967.1    0.12       0  5027.8    0.07       0
  5033.1    0.12       0  5053.4    0.05       0
Bank Sta=5027.8,5033.1
Exp/Cntr=0.3,0.1

Type RM Length L Ch R = 1,3199,464,464,464
BEGIN DESCRIPTION:
LWE S 007 3.0
END DESCRIPTION:
XS GIS Cut Line= 3
      2365077.83      7044706.30      2365443.57      7044700.62
      2366395.02      7044482.59
#Sta/Elev= 30
  4392.5  627.61  4472.4  625.55  4543.7  625.38  4583.7  623.53  4633.7  622.97
  4673.7  621.87  4683.7  622.35  4693.7  622.11  4703.7  621.16  4758.3  621.25
  4794.6  619.65  4897.2  616.96  4907.5  616.18  4915.2  614.53  5009.3  613.65
  5054.2  614.75  5081.9  617.40  5112.7  619.38  5140.0  620.41  5174.2  620.48
  5205.0  621.37  5297.3  620.99  5328.1  620.00  5348.6  621.12  5369.9  620.59
  5450.5  620.63  5455.7  621.34  5492.3  621.72  5675.3  622.34  5734.4  623.02
#Mann=3,-1,0
  4392.5    0.05       0  4915.2   0.033       0  5054.2    0.05       0
Bank Sta=4915.2,5054.2
Exp/Cntr=0.3,0.1

Type RM Length L Ch R = 1,2735,152,152,152
BEGIN DESCRIPTION:
LWE S 007 2.4
END DESCRIPTION:
XS GIS Cut Line= 3
      2365199.73      7044731.78      2365695.89      7045168.40
      2366284.76      7045329.77
#Sta/Elev= 30
  4579.1  624.79  4627.1  624.01  4846.3  618.39  4896.5  618.44  4960.1  617.17
  4974.3  616.40  4981.0  614.50  5339.3  613.49  5343.2  613.49  5344.1  613.99
  5346.9  615.15  5357.3  616.26  5388.4  618.02  5409.1  618.40  5429.9  617.68
  5481.7  618.56  5554.3  617.90  5608.4  618.20  5668.4  617.44  5677.4  617.76
  5682.6  616.58  5717.0  616.90  5722.2  616.43  5761.9  616.44  5791.2  616.54
  5796.3  617.38  5803.1  617.48  5830.8  617.21  5836.0  619.15  5850.6  619.13
#Mann=3,-1,0
  4579.1    0.05       0  4981.0   0.033       0  5344.1    0.05       0
Bank Sta=4981,5344.1
Exp/Cntr=0.3,0.1

Type RM Length L Ch R = 1,2583,301,301,301
BEGIN DESCRIPTION:
LWE S 007 2.2
END DESCRIPTION:
XS GIS Cut Line= 3
      2365067.22      7044870.64      2365574.60      7045214.93
      2366225.49      7045336.98
#Sta/Elev= 30
  4603.4  627.39  4848.0  620.02  4985.7  614.13  5093.5  620.84  5108.5  618.56
  5114.5  620.26  5123.4  618.91  5129.4  621.02  5144.4  617.44  5150.4  620.85
  5159.3  619.05  5165.4  620.82  5180.3  618.13  5186.4  620.44  5201.3  620.54
  5241.4  619.72  5267.1  617.42  5274.1  619.21  5321.6  615.00  5333.0  617.10
  5363.5  614.37  5399.2  615.35  5421.7  614.07  5422.6  613.57  5427.4  614.07
  5516.1  617.88  5739.9  616.20  5809.9  617.25  5815.0  619.48  5878.8  619.16
#Mann=5,-1,0
  4603.4    0.05       0  5267.1    0.12       0  5399.2    0.05       0
  5421.7    0.04       0  5427.4    0.05       0
Bank Sta=5421.7,5427.4
Exp/Cntr=0.3,0.1

Type RM Length L Ch R = 1,2282,489,489,489
BEGIN DESCRIPTION:
LWE S 007 2.0
END DESCRIPTION:
XS GIS Cut Line= 3
      2365076.28      7045128.86      2365692.38      7045382.54
      2366281.24      7045396.13
#Sta/Elev= 30
  4590.1  626.86  4679.6  622.77  4755.3  617.68  4762.2  616.37  4815.5  613.47
  4863.4  611.97  4868.8  610.82  4874.3  611.23  4894.7  609.47  4922.1  609.26
  4946.1  607.07  4972.6  606.97  4973.5  606.47  4978.3  606.97  4982.4  608.17
  4999.4  607.11  5014.8  607.42  5023.3  608.50  5028.7  607.83  5090.5  608.43
  5112.1  609.43  5129.9  608.47  5135.3  609.73  5183.2  611.89  5314.7  615.92
  5333.0  616.32  5343.0  617.37  5365.4  616.30  5653.1  617.49  5845.4  617.23
#Mann=5,-1,0
  4590.1    0.05       0  4894.7    0.12       0  4972.6    0.07       0
  4978.3    0.12       0  5314.7    0.05       0
Bank Sta=4972.6,4978.3
Exp/Cntr=0.3,0.1

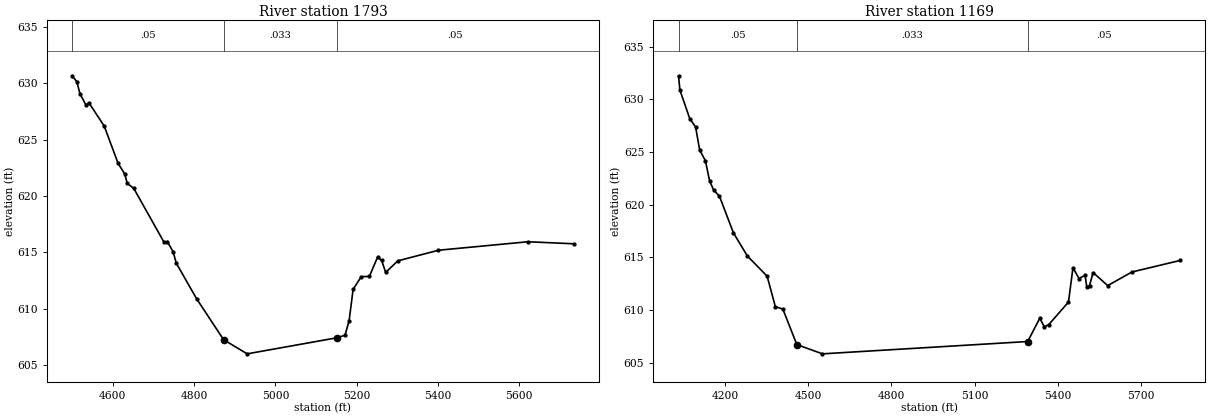
Type RM Length L Ch R = 1,1793,624,624,624
BEGIN DESCRIPTION:
LWE S 007 1.0
END DESCRIPTION:
XS GIS Cut Line= 3
      2364908.72      7045455.04      2365384.34      7045704.18
      2366081.98      7045686.05
#Sta/Elev= 30
  4499.7  630.64  4511.3  630.13  4519.1  629.06  4533.9  628.05  4541.1  628.25
  4579.0  626.18  4613.0  622.88  4629.4  621.95  4635.5  621.11  4651.4  620.68
  4725.8  615.92  4734.1  615.97  4748.4  615.06  4756.1  614.06  4805.9  610.92
  4872.6  607.28  4930.6  606.03  5151.3  607.45  5171.3  607.68  5181.3  608.93
  5191.3  611.74  5211.3  612.86  5231.3  612.88  5251.4  614.58  5261.4  614.30
  5271.4  613.24  5301.4  614.26  5401.4  615.20  5621.5  615.95  5734.5  615.77
#Mann=3,-1,0
  4499.7    0.05       0  4872.6   0.033       0  5151.3    0.05       0
Bank Sta=4872.6,5151.3
Exp/Cntr=0.3,0.1

Type RM Length L Ch R = 1,1169,0,0,0
BEGIN DESCRIPTION:
LWE S 007 0.5
END DESCRIPTION:
XS GIS Cut Line= 4
      2364618.75      7045654.32      2365039.25      7046244.20
      2365438.70      7046315.73      2366035.30      7045990.31
#Sta/Elev= 30
  4032.0  632.25  4036.9  630.90  4072.6  628.17  4093.5  627.39  4108.2  625.21
  4129.1  624.17  4143.9  622.28  4158.6  621.40  4179.5  620.82  4229.9  617.34
  4280.3  615.14  4351.6  613.22  4381.1  610.33  4408.2  610.10  4458.6  606.73
  4551.2  605.85  5291.3  607.02  5335.0  609.24  5351.1  608.41  5367.2  608.62
  5438.4  610.77  5454.6  614.03  5476.4  613.00  5498.2  613.31  5504.3  612.22
  5514.4  612.33  5527.1  613.57  5579.9  612.33  5667.2  613.62  5841.8  614.72
#Mann=3,-1,0
  4032.0    0.05       0  4458.6   0.033       0  5291.3    0.05       0
Bank Sta=4458.6,5291.3
Exp/Cntr=0.3,0.1

Chan Stop Cuts=-1