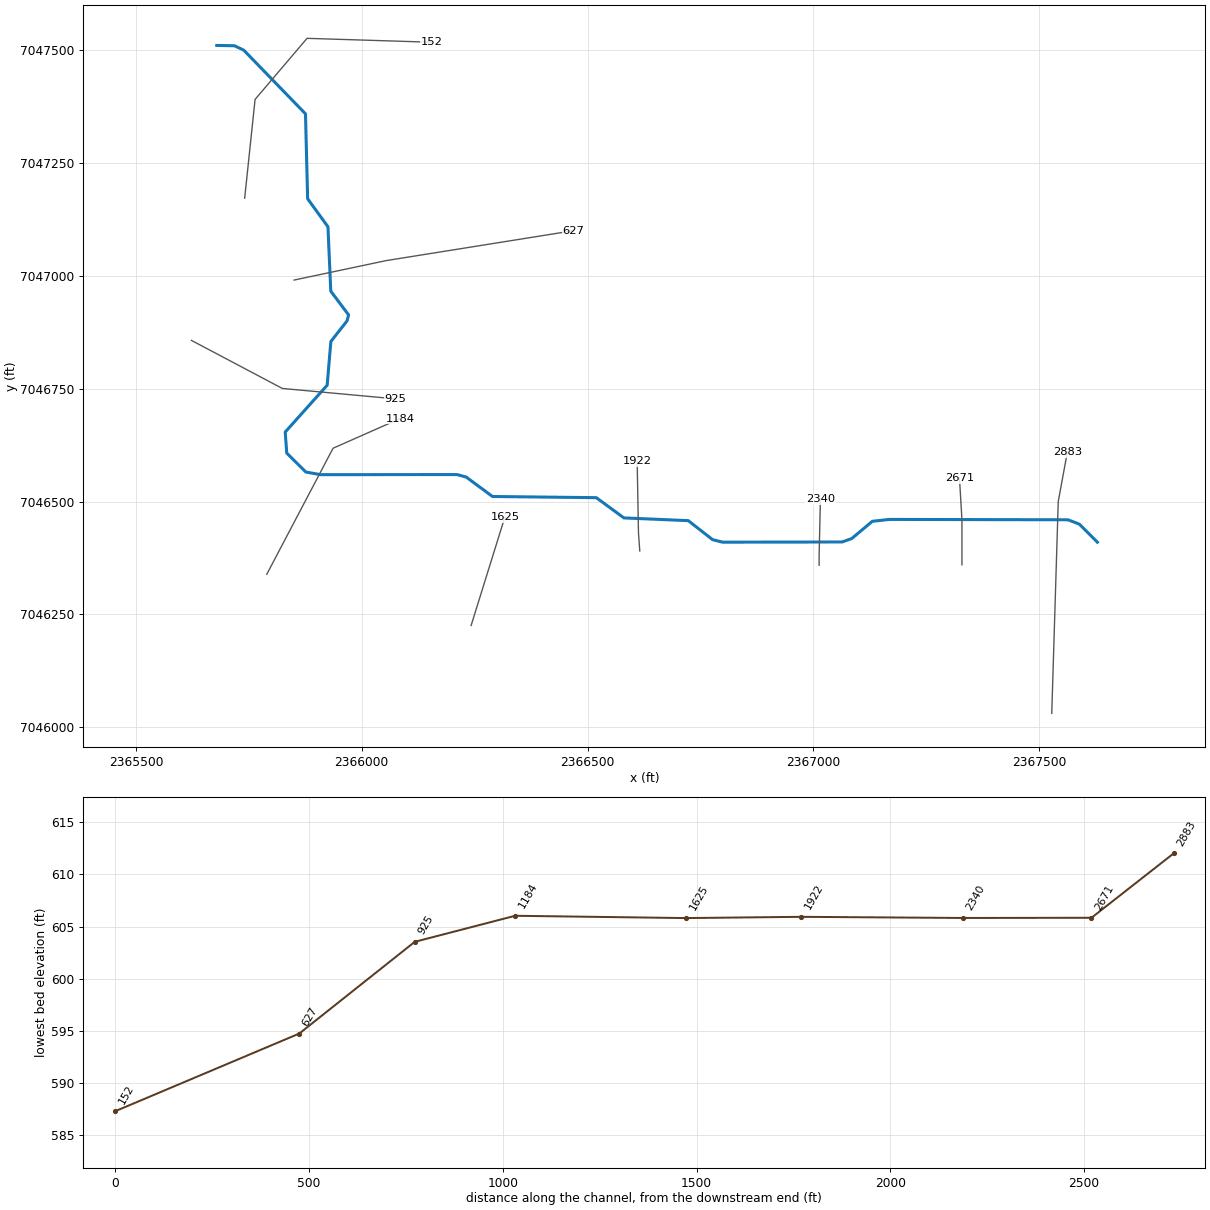
--- LWE S 008.prj (project) ---

Proj Title=LWE S 008 Base Level Engineering
Current Plan=p01
Default Exp/Contr=0.3,0.1
English Units
Geom File=g01
Flow File=f01
Plan File=p01
Y Axis Title=Elevation
X Axis Title(PF)=Main Channel Distance
X Axis Title(XS)=Station
BEGIN DESCRIPTION:
LWE S 008
END DESCRIPTION:
DSS Export Rating Curves= 0
DSS Export Rating Curve Sorted= 0
DSS Export Volume Flow Curves= 0
DXF OffsetX= 0
DXF OffsetY= 0
DXF ScaleX= 1
DXF ScaleY= 10

--- LWE S 008.p01 (plan) ---

Plan Title=Multiple Run
Program Version=4.10
Short Identifier=Multiple
Geom File=g01
Flow File=f01
Subcritical Flow
K Sum by GR= 0
Std Step Tol= 0.01
Critical Tol= 0.01
Num of Std Step Trials= 20
Max Error Tol= 0.3
Flow Tol Ratio= 0.001
Split Flow NTrial= 30
Split Flow Tol= 0.02
Split Flow Ratio= 0.02
Log Output Level= 0
Friction Slope Method= 1
Unsteady Friction Slope Method= 2
Unsteady Bridges Friction Slope Method= 1
Parabolic Critical Depth
Global Vel Dist= 1 , 1 , 1
Global Log Level= 0
CheckData=True
Encroach Param=-1 ,0,0, 0
BEGIN DESCRIPTION:
Multiple Run
END DESCRIPTION:
Computation Interval=1HOUR
Output Interval=1HOUR
Run HTab= 0
Run UNet= 0
Run PostProcess= 0
Run WQNet= 0
UNET Theta= 1
UNET Theta Warmup= 1
UNET ZTol= 0.02
UNET ZSATol= 0.05
UNET MxIter= 20
UNET MaxInSteps= 0
UNET DtIC= 0
UNET DtMin= 0
UNET MaxCRTS= 20
UNET WFStab= 2
UNET SFStab= 1
UNET WFX= 1
UNET SFX= 1
UNET DSS MLevel= 4
UNET DZMax Abort= 100
UNET Convert EG Bridges= 0
UNET Use Existing IB Tables=-1
UNET Froude Reduction=False
UNET Froude Limit= 1
UNET Froude Power= 10
UNET Time Slicing=0,0, 5
UNET Junction Losses=0
Instantaneous Interval=1HOUR
Write IC File= 0
Write IC File at Sim End=0
Echo Input=False
Echo Parameters=False
Echo Output=False
Write Detailed= 0
WQ AD Non Conservative
WQ ULTIMATE=-1
WQ Max Comp Step=1HOUR
WQ Output Interval=15MIN
WQ Output Selected Increments= 0
WQ Output face flow=0
WQ Output face velocity=0
WQ Output face area=0
WQ Output face dispersion=0
WQ Output cell volume=0
WQ Output cell surface area=0
WQ Output cell continuity=0
WQ Output cumulative cell continuity=0
WQ Output face conc=0
WQ Output face dconc_dx=0
WQ Output face courant=0
WQ Output face peclet=0
WQ Output face adv mass=0
WQ Output face disp mass=0
WQ Output cell mass=0
WQ Output cell source sink temp=0
WQ Output cell source sink nsm=0
WQ Output MaxMinRange=-1
WQ Daily Max Min Mean=-1
WQ Daily Range=0
WQ Daily Time=0
WQ Create Restart=0
WQ Fixed Restart=0
WQ System Summary=0
WQ Use Fixed Temperature=0
Sorting and Armoring Iterations= 10
XS Update Threshold= 0.02
Hydraulics Update Threshold= 0.02
Energy Slope Method= 1
Volume Change Method= 0
XS Weighting Method= 0
Number of US Weighted Cross Sections= 1
Number of DS Weighted Cross Sections= 1
Upstream XS Weight=0.25
Main XS Weight=0.5
Downstream XS Weight=0.25
Number of DS XS's Weighted with US Boundary= 1
Upstream Boundary Weight= 1
Weight of XSs Associated with US Boundary= 0
Number of US XS's Weighted with DS Boundary= 1
Downstream Boundary Weight= 0.5
Weight of XSs Associated with DS Boundary= 0.5
Sediment Output Level= 4
Mass or Volume Output= 0
Output Increment Type= 1
Profile and TS Output Increment= 10
XS Output Flag= 0
XS Output Increment= 10
Disregard all LS=0
Disregard all Conn=0
Disregard all Breaches=0
Disregard all Pumps=0

--- LWE S 008.f01 (steady flow) ---

Flow Title=Multiple
Number of Profiles=7
Profile Names=10-year,25-year,50-year,1pct_min,100-year,1pct_plu,500-year
River Rch & RM= LWE S 008,Reach-1,2883
      51      57      60      32      65     129      73
Boundary for River Rch & Prof#=LWE S 008,Reach-1,1
Up Type=0
Dn Type=3
Dn Slope=0.005
Boundary for River Rch & Prof#=LWE S 008,Reach-1,2
Up Type=0
Dn Type=3
Dn Slope=0.005
Boundary for River Rch & Prof#=LWE S 008,Reach-1,3
Up Type=0
Dn Type=3
Dn Slope=0.005
Boundary for River Rch & Prof#=LWE S 008,Reach-1,4
Up Type=0
Dn Type=3
Dn Slope=0.005
Boundary for River Rch & Prof#=LWE S 008,Reach-1,5
Up Type=0
Dn Type=3
Dn Slope=0.005
Boundary for River Rch & Prof#=LWE S 008,Reach-1,6
Up Type=0
Dn Type=3
Dn Slope=0.005
Boundary for River Rch & Prof#=LWE S 008,Reach-1,7
Up Type=0
Dn Type=3
Dn Slope=0.005

--- LWE S 008.g01 (geometry) ---

Geom Title=Existing Conditions
Program Version=4.10

River Reach=LWE S 008       ,Reach-1
Reach XY= 30
        2367629.        7046410.      2367588.98      7046449.95
      2367563.85      7046459.64      2367168.81      7046460.45
      2367130.57      7046456.22      2367085.06      7046418.14
      2367063.78      7046410.52      2366799.03      7046410.07
      2366776.67      7046415.75      2366723.06      7046457.73
      2366580.57      7046463.79      2366519.34      7046508.62
       2366289.5      7046511.22      2366231.33      7046554.25
      2366210.73      7046559.79      2365908.74      7046559.54
      2365876.22      7046565.36      2365833.95      7046607.42
      2365830.57      7046653.91      2365923.46      7046757.58
      2365931.67      7046854.51      2365967.53      7046900.09
      2365970.92       7046913.3      2365931.47      7046965.86
      2365925.21      7047108.43      2365880.22      7047170.51
      2365875.46      7047358.54      2365738.79      7047499.49
      2365718.25      7047509.25        2365679.        7047510.

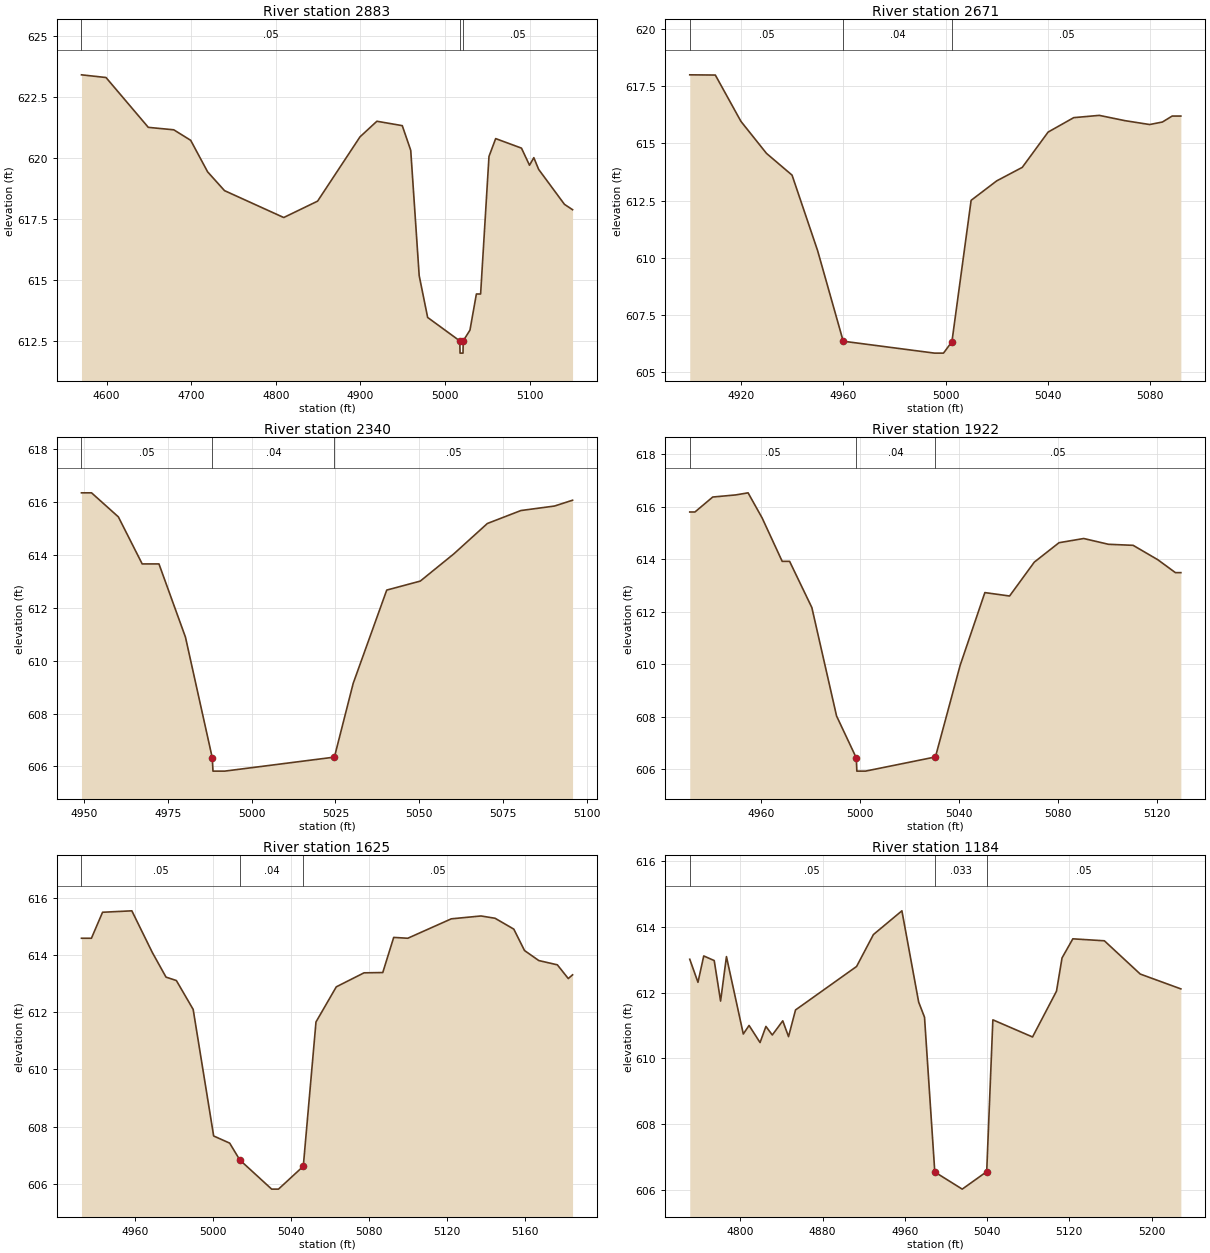
Type RM Length L Ch R = 1 ,2883    ,212,212,212
BEGIN DESCRIPTION:
LWE S 008 5.0
END DESCRIPTION:
XS GIS Cut Line= 3
      2367527.87      7046030.99      2367542.25      7046500.08
       2367562.4      7046609.43
#Sta/Elev= 30
  4570.4  623.41  4599.4   623.3  4649.4  621.26  4679.5  621.16  4699.5  620.73
  4719.5  619.44  4739.5  618.67  4809.5  617.57  4849.5  618.24  4899.6  620.87
  4919.6  621.51  4949.6  621.33  4959.6  620.32  4969.6  615.19  4979.6  613.48
  5017.6  612.52  5017.9  612.02  5021.4  612.02  5021.6  612.52  5029.6  612.96
  5037.2  614.44  5042.2  614.44  5052.1  620.07    5060   620.8  5090.5  620.41
    5100  619.71  5105.1  620.02  5110.8  619.54  5141.3  618.11  5150.9  617.89
#Mann= 3 ,-1 , 0
  4570.4     .05       0  5017.6    .033       0  5021.6     .05       0
Bank Sta=5017.6,5021.6
XS Rating Curve= 0 ,0
Exp/Cntr=0.3,0.1

Type RM Length L Ch R = 1 ,2671    ,331,331,331
BEGIN DESCRIPTION:
LWE S 008 4.0
END DESCRIPTION:
XS GIS Cut Line= 3
        2367329.      7046360.01        2367329.        7046460.
      2367323.55      7046551.85
#Sta/Elev= 21
    4900  617.99    4910  617.98    4920  615.96    4930  614.56    4940  613.61
    4950  610.31    4960  606.36  4995.7  605.84  4999.2  605.84  5002.5  606.34
    5010  612.51    5020  613.36    5030  613.95  5040.1  615.49  5050.1  616.12
  5060.1  616.22  5070.1  615.99  5079.8  615.82  5084.8  615.93  5088.6  616.19
    5092  616.19
#Mann= 3 ,-1 , 0
    4900     .05       0    4960     .04       0  5002.5     .05       0
Bank Sta=4960,5002.5
XS Rating Curve= 0 ,0
Exp/Cntr=0.3,0.1

Type RM Length L Ch R = 1 ,2340    ,418,418,418
BEGIN DESCRIPTION:
LWE S 008 3.5
END DESCRIPTION:
XS GIS Cut Line= 3
      2367012.76      7046359.02      2367012.76      7046379.22
      2367015.63      7046505.39
#Sta/Elev= 19
  4949.3  616.35  4952.3  616.35  4960.3  615.44  4967.4  613.66  4969.5  613.66
  4972.4  613.66  4980.3  610.89  4988.3  606.32  4988.5  605.82    4992  605.82
  5024.7  606.35  5030.3  609.14  5040.3  612.67  5050.3  613.01  5060.3  614.04
  5070.3  615.19  5080.3  615.68  5090.3  615.85  5095.7  616.07
#Mann= 3 ,-1 , 0
  4949.3     .05       0  4988.3     .04       0  5024.7     .05       0
Bank Sta=4988.3,5024.7
XS Rating Curve= 0 ,0
Exp/Cntr=0.3,0.1

Type RM Length L Ch R = 1 ,1922    ,297,297,297
BEGIN DESCRIPTION:
LWE S 008 3.0
END DESCRIPTION:
XS GIS Cut Line= 3
      2366615.64      7046390.75      2366612.76      7046431.01
      2366609.88      7046589.32
#Sta/Elev= 25
    4931   615.8  4933.1   615.8  4940.3  616.37  4949.6  616.45  4954.6  616.53
  4960.3  615.57  4968.4  613.92  4971.4  613.92  4980.4  612.16  4990.4  608.03
  4998.4  606.43  4998.6  605.93  5002.1  605.93  5030.4  606.47  5040.4  609.96
  5050.4  612.73  5060.4   612.6  5070.4  613.89  5080.4  614.63  5090.4  614.79
  5100.4  614.57  5110.4  614.53  5120.4  613.98  5127.5  613.49  5129.7  613.49
#Mann= 3 ,-1 , 0
    4931     .05       0  4998.4     .04       0  5030.4     .05       0
Bank Sta=4998.4,5030.4
XS Rating Curve= 0 ,0
Exp/Cntr=0.3,0.1

Type RM Length L Ch R = 1 ,1625    ,441,441,441
BEGIN DESCRIPTION:
LWE S 008 2.0
END DESCRIPTION:
XS GIS Cut Line= 2
      2366242.27      7046225.75      2366316.98       7046465.9
#Sta/Elev= 29
  4932.7  614.59  4937.8  614.59  4943.5   615.5  4958.5  615.55    4969  614.09
    4976  613.23  4981.3  613.11  4989.9   612.1  5000.4  607.67  5008.6  607.42
  5013.8  606.83  5030.1  605.81  5033.6  605.81  5046.3  606.61  5052.8  611.66
  5063.2  612.89  5077.4  613.38    5087  613.39  5092.6  614.62  5099.8  614.59
  5122.1  615.27  5137.3  615.37  5144.5  615.29  5154.1  614.91  5159.6  614.16
  5166.9  613.81  5176.4  613.66    5182  613.18  5184.2  613.31
#Mann= 3 ,-1 , 0
  4932.7     .05       0  5013.8     .04       0  5046.3     .05       0
Bank Sta=5013.8,5046.3
XS Rating Curve= 0 ,0
Exp/Cntr=0.3,0.1

Type RM Length L Ch R = 1 ,1184    ,259,259,259
BEGIN DESCRIPTION:
LWE S 008 1.5
END DESCRIPTION:
XS GIS Cut Line= 3
      2365789.76      7046338.96       2365936.5      7046618.06
      2366085.09      7046683.78
#Sta/Elev= 30
  4750.7  613.01  4758.7  612.31  4764.3  613.11  4774.5  612.97  4780.7  611.74
  4786.4  613.09  4802.8  610.74  4808.4     611  4819.1  610.48  4824.8  610.97
    4831  610.71  4841.2  611.14  4846.8  610.66  4853.6  611.47    4913  612.79
  4929.4  613.76  4957.1  614.48  4973.4  611.71  4979.1  611.25  4989.1  606.55
  5015.8  606.03  5039.6  606.56  5045.6  611.17  5084.2  610.65  5107.5  612.04
  5112.9  613.05  5123.4  613.63  5154.1  613.57    5189  612.56  5228.5  612.11
#Mann= 3 ,-1 , 0
  4750.7     .05       0  4989.1    .033       0  5039.6     .05       0
Bank Sta=4989.1,5039.6
XS Rating Curve= 0 ,0
Exp/Cntr=0.3,0.1

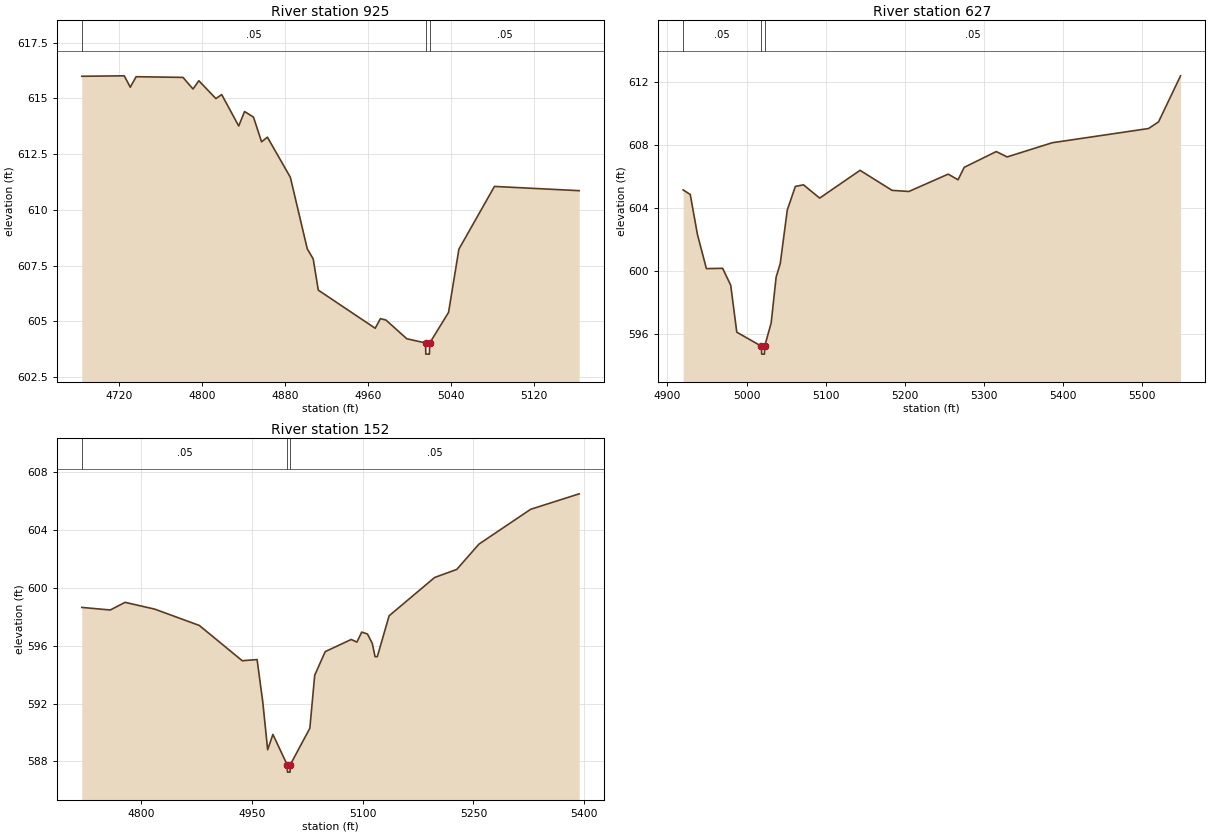
Type RM Length L Ch R = 1 ,925     ,298,298,298
BEGIN DESCRIPTION:
LWE S 008 1.0
END DESCRIPTION:
XS GIS Cut Line= 3
      2365622.87      7046856.89      2365824.27      7046750.44
      2366074.31      7046727.45
#Sta/Elev= 30
  4684.4  615.99  4725.3  616.01  4731.1   615.5  4736.7  615.97  4781.8  615.94
  4791.5  615.42  4797.1  615.79  4813.5  614.99  4819.1  615.17  4835.5  613.76
  4841.1  614.41  4849.7  614.16  4857.5  613.05  4863.1  613.26  4885.2  611.46
  4901.5  608.25  4907.2   607.8  4912.1   606.4  4966.9  604.69  4971.9  605.12
  4977.2  605.06  4997.3  604.22  5015.4  604.03  5015.6  603.53  5019.1  603.53
  5019.4  604.03  5037.5   605.4  5047.5  608.24  5081.7  611.05  5163.3  610.86
#Mann= 3 ,-1 , 0
  4684.4     .05       0  5015.4    .033       0  5019.4     .05       0
Bank Sta=5015.4,5019.4
XS Rating Curve= 0 ,0
Exp/Cntr=0.3,0.1

Type RM Length L Ch R = 1 ,627     ,475,475,475
BEGIN DESCRIPTION:
LWE S 008 0.5
END DESCRIPTION:
XS GIS Cut Line= 3
      2365850.22      7046990.45      2366054.49       7047033.6
      2366468.85      7047099.79
#Sta/Elev= 30
  4919.8  605.13  4928.8  604.84  4937.9   602.3  4949.2  600.14  4969.7  600.16
  4979.9  599.09  4987.6  596.11  5018.8  595.22    5019  594.72  5022.5  594.72
  5022.8  595.22    5031  596.69  5037.3   599.6  5042.5  600.46  5051.4  603.86
  5061.6  605.35  5071.9  605.45  5092.3  604.61  5143.3  606.37  5183.8   605.1
    5205  605.03  5254.7  606.13  5267.1  605.77  5274.9  606.56  5315.4  607.56
  5329.1  607.22  5386.2  608.12  5507.8  609.02  5520.4  609.44  5548.2  612.36
#Mann= 3 ,-1 , 0
  4919.8     .05       0  5018.8     .04       0  5022.8     .05       0
Bank Sta=5018.8,5022.8
XS Rating Curve= 0 ,0
Exp/Cntr=0.3,0.1

Type RM Length L Ch R = 1 ,152     ,0,0,0
BEGIN DESCRIPTION:
LWE S 008 0.2
END DESCRIPTION:
XS GIS Cut Line= 4
      2365740.82      7047171.76      2365763.84      7047390.44
      2365878.95      7047525.69      2366154.62      7047517.07
#Sta/Elev= 30
  4719.9  598.66  4758.4  598.48  4778.5  599.01  4818.7  598.54    4879  597.41
  4937.1  594.97  4957.2  595.05  4964.9  592.11  4971.5  588.81  4978.6  589.87
    4998  587.76  4998.3  587.26  5001.8  587.26    5002  587.76  5028.6   590.3
  5035.2  593.97  5049.4   595.6  5084.6  596.44  5092.3  596.26  5098.8  596.95
  5106.6  596.82  5113.1  596.17  5116.9  595.25  5119.9  595.25  5135.9  598.08
  5197.5  600.73  5227.5  601.29  5257.5  603.04  5327.5  605.45  5393.2  606.52
#Mann= 3 ,-1 , 0
  4719.9     .05       0    4998    .033       0    5002     .05       0
Bank Sta=4998,5002
XS Rating Curve= 0 ,0
Exp/Cntr=0.3,0.1

Chan Stop Cuts=-1
Use User Specified Reach Order=0
Composite Channel Slope=5