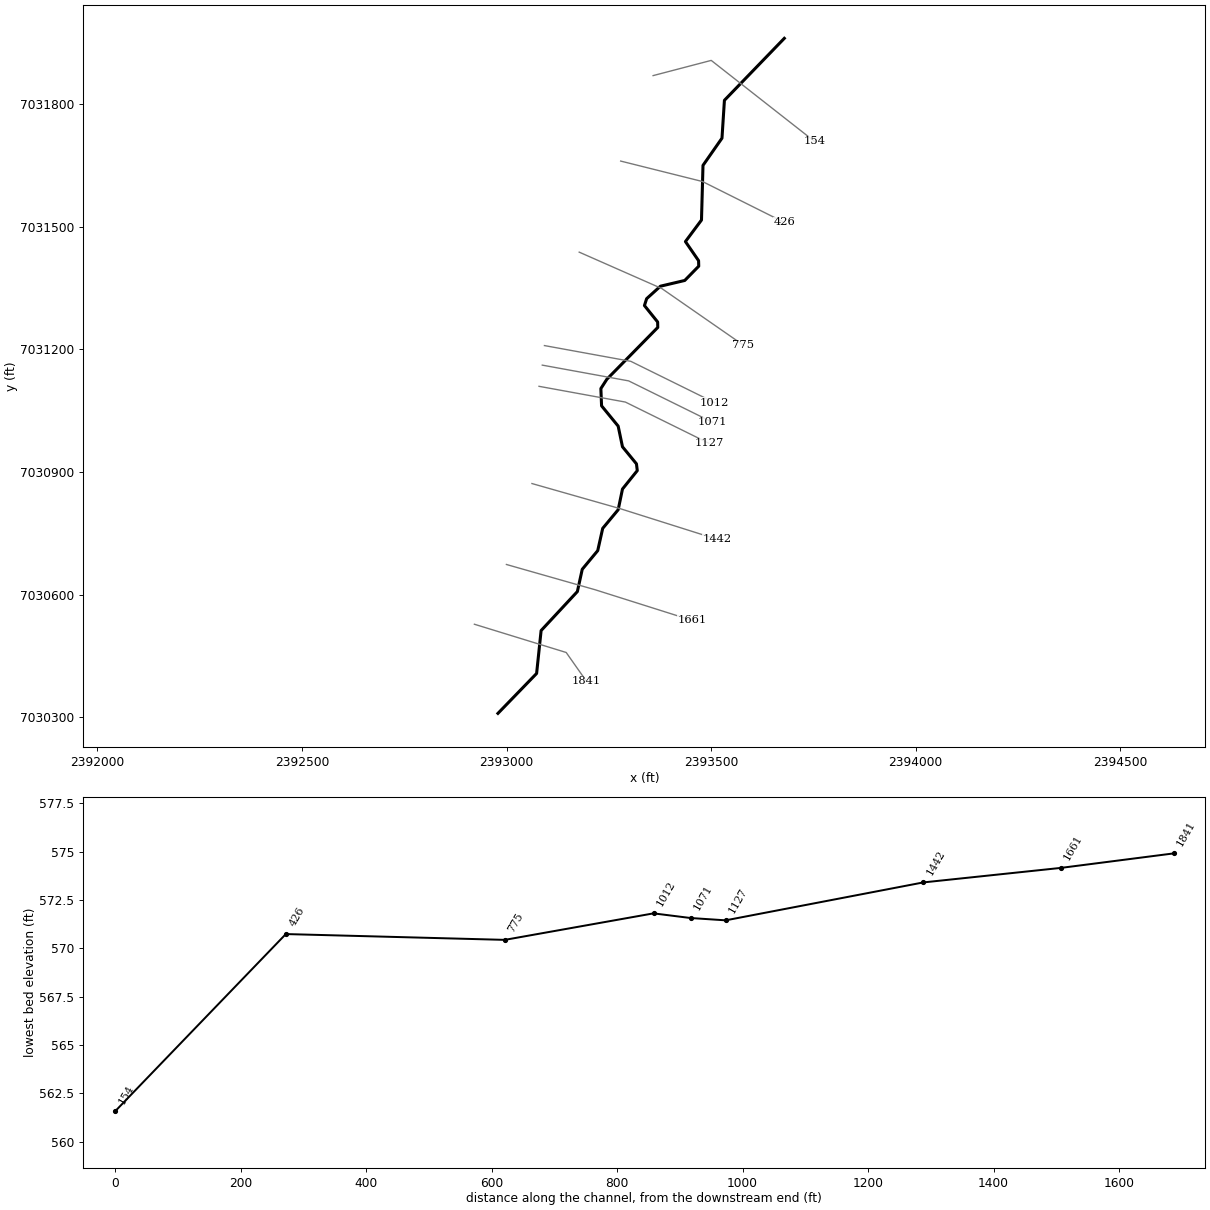
--- LWE S 013.prj (project) ---

Proj Title=LWE S 013 Base Level Engineering
Current Plan=p01
Default Exp/Contr=0.3,0.1
English Units
Geom File=g01
Flow File=f01
Plan File=p01
Y Axis Title=Elevation
X Axis Title(PF)=Main Channel Distance
X Axis Title(XS)=Station
BEGIN DESCRIPTION:
LWE S 013
END DESCRIPTION:
DSS Export Rating Curves= 0
DSS Export Rating Curve Sorted= 0
DSS Export Volume Flow Curves= 0
DXF OffsetX= 0
DXF OffsetY= 0
DXF ScaleX= 1
DXF ScaleY= 10

--- LWE S 013.p01 (plan) ---

Plan Title=Multiple Run
Program Version=4.10
Short Identifier=Multiple
Geom File=g01
Flow File=f01
Subcritical Flow
K Sum by GR= 0
Std Step Tol= 0.01
Critical Tol= 0.01
Num of Std Step Trials= 20
Max Error Tol= 0.3
Flow Tol Ratio= 0.001
Split Flow NTrial= 30
Split Flow Tol= 0.02
Split Flow Ratio= 0.02
Log Output Level= 0
Friction Slope Method= 1
Unsteady Friction Slope Method= 2
Unsteady Bridges Friction Slope Method= 1
Parabolic Critical Depth
Global Vel Dist= 1 , 1 , 1
Global Log Level= 0
CheckData=True
Encroach Param=-1 ,0,0, 0
BEGIN DESCRIPTION:
Multiple Run
END DESCRIPTION:
Computation Interval=1HOUR
Output Interval=1HOUR
Run HTab= 0
Run UNet= 0
Run PostProcess= 0
Run WQNet= 0
UNET Theta= 1
UNET Theta Warmup= 1
UNET ZTol= 0.02
UNET ZSATol= 0.05
UNET MxIter= 20
UNET MaxInSteps= 0
UNET DtIC= 0
UNET DtMin= 0
UNET MaxCRTS= 20
UNET WFStab= 2
UNET SFStab= 1
UNET WFX= 1
UNET SFX= 1
UNET DSS MLevel= 4
UNET DZMax Abort= 100
UNET Convert EG Bridges= 0
UNET Use Existing IB Tables=-1
UNET Froude Reduction=False
UNET Froude Limit= 1
UNET Froude Power= 10
UNET Time Slicing=0,0, 5
UNET Junction Losses=0
Instantaneous Interval=1HOUR
Write IC File= 0
Write IC File at Sim End=0
Echo Input=False
Echo Parameters=False
Echo Output=False
Write Detailed= 0
WQ AD Non Conservative
WQ ULTIMATE=-1
WQ Max Comp Step=1HOUR
WQ Output Interval=15MIN
WQ Output Selected Increments= 0
WQ Output face flow=0
WQ Output face velocity=0
WQ Output face area=0
WQ Output face dispersion=0
WQ Output cell volume=0
WQ Output cell surface area=0
WQ Output cell continuity=0
WQ Output cumulative cell continuity=0
WQ Output face conc=0
WQ Output face dconc_dx=0
WQ Output face courant=0
WQ Output face peclet=0
WQ Output face adv mass=0
WQ Output face disp mass=0
WQ Output cell mass=0
WQ Output cell source sink temp=0
WQ Output cell source sink nsm=0
WQ Output MaxMinRange=-1
WQ Daily Max Min Mean=-1
WQ Daily Range=0
WQ Daily Time=0
WQ Create Restart=0
WQ Fixed Restart=0
WQ System Summary=0
WQ Use Fixed Temperature=0
Sorting and Armoring Iterations= 10
XS Update Threshold= 0.02
Hydraulics Update Threshold= 0.02
Energy Slope Method= 1
Volume Change Method= 0
XS Weighting Method= 0
Number of US Weighted Cross Sections= 1
Number of DS Weighted Cross Sections= 1
Upstream XS Weight=0.25
Main XS Weight=0.5
Downstream XS Weight=0.25
Number of DS XS's Weighted with US Boundary= 1
Upstream Boundary Weight= 1
Weight of XSs Associated with US Boundary= 0
Number of US XS's Weighted with DS Boundary= 1
Downstream Boundary Weight= 0.5
Weight of XSs Associated with DS Boundary= 0.5
Sediment Output Level= 4
Mass or Volume Output= 0
Output Increment Type= 1
Profile and TS Output Increment= 10
XS Output Flag= 0
XS Output Increment= 10
Disregard all LS=0
Disregard all Conn=0
Disregard all Breaches=0
Disregard all Pumps=0

--- LWE S 013.f01 (steady flow) ---

Flow Title=Multiple
Number of Profiles=7
Profile Names=10-year,25-year,50-year,1pct_min,100-year,1pct_plu,500-year
River Rch & RM= LWE S 013,Reach-1,1841
     499     670     807     483     963    1921    1369
Boundary for River Rch & Prof#=LWE S 013,Reach-1,1
Up Type=0
Dn Type=3
Dn Slope=0.005
Boundary for River Rch & Prof#=LWE S 013,Reach-1,2
Up Type=0
Dn Type=3
Dn Slope=0.005
Boundary for River Rch & Prof#=LWE S 013,Reach-1,3
Up Type=0
Dn Type=3
Dn Slope=0.005
Boundary for River Rch & Prof#=LWE S 013,Reach-1,4
Up Type=0
Dn Type=3
Dn Slope=0.005
Boundary for River Rch & Prof#=LWE S 013,Reach-1,5
Up Type=0
Dn Type=3
Dn Slope=0.005
Boundary for River Rch & Prof#=LWE S 013,Reach-1,6
Up Type=0
Dn Type=3
Dn Slope=0.005
Boundary for River Rch & Prof#=LWE S 013,Reach-1,7
Up Type=0
Dn Type=3
Dn Slope=0.005

--- LWE S 013.g01 (geometry) ---

Geom Title=Existing Conditions
Program Version=4.10

River Reach=LWE S 013       ,Reach-1
Reach XY= 30
        2392979.        7030310.      2393073.54      7030407.55
      2393084.54      7030512.42      2393173.15      7030607.71
       2393185.1      7030662.19      2393222.92       7030707.8
      2393235.08       7030762.2      2393272.95      7030807.81
      2393283.43      7030858.36      2393319.61      7030903.39
       2393317.6      7030919.92      2393283.42      7030961.64
      2393272.87      7031012.19      2393232.31      7031061.74
      2393230.61      7031103.96      2393245.22      7031126.68
      2393369.69      7031253.34      2393369.38      7031266.68
      2393337.09      7031306.85      2393342.51      7031323.68
      2393376.22      7031354.14      2393435.63      7031368.16
      2393469.82      7031403.05      2393469.46       7031416.5
      2393437.29      7031463.21      2393476.54      7031515.86
      2393480.23      7031649.49      2393526.64      7031715.98
      2393532.61      7031808.51        2393679.        7031960.

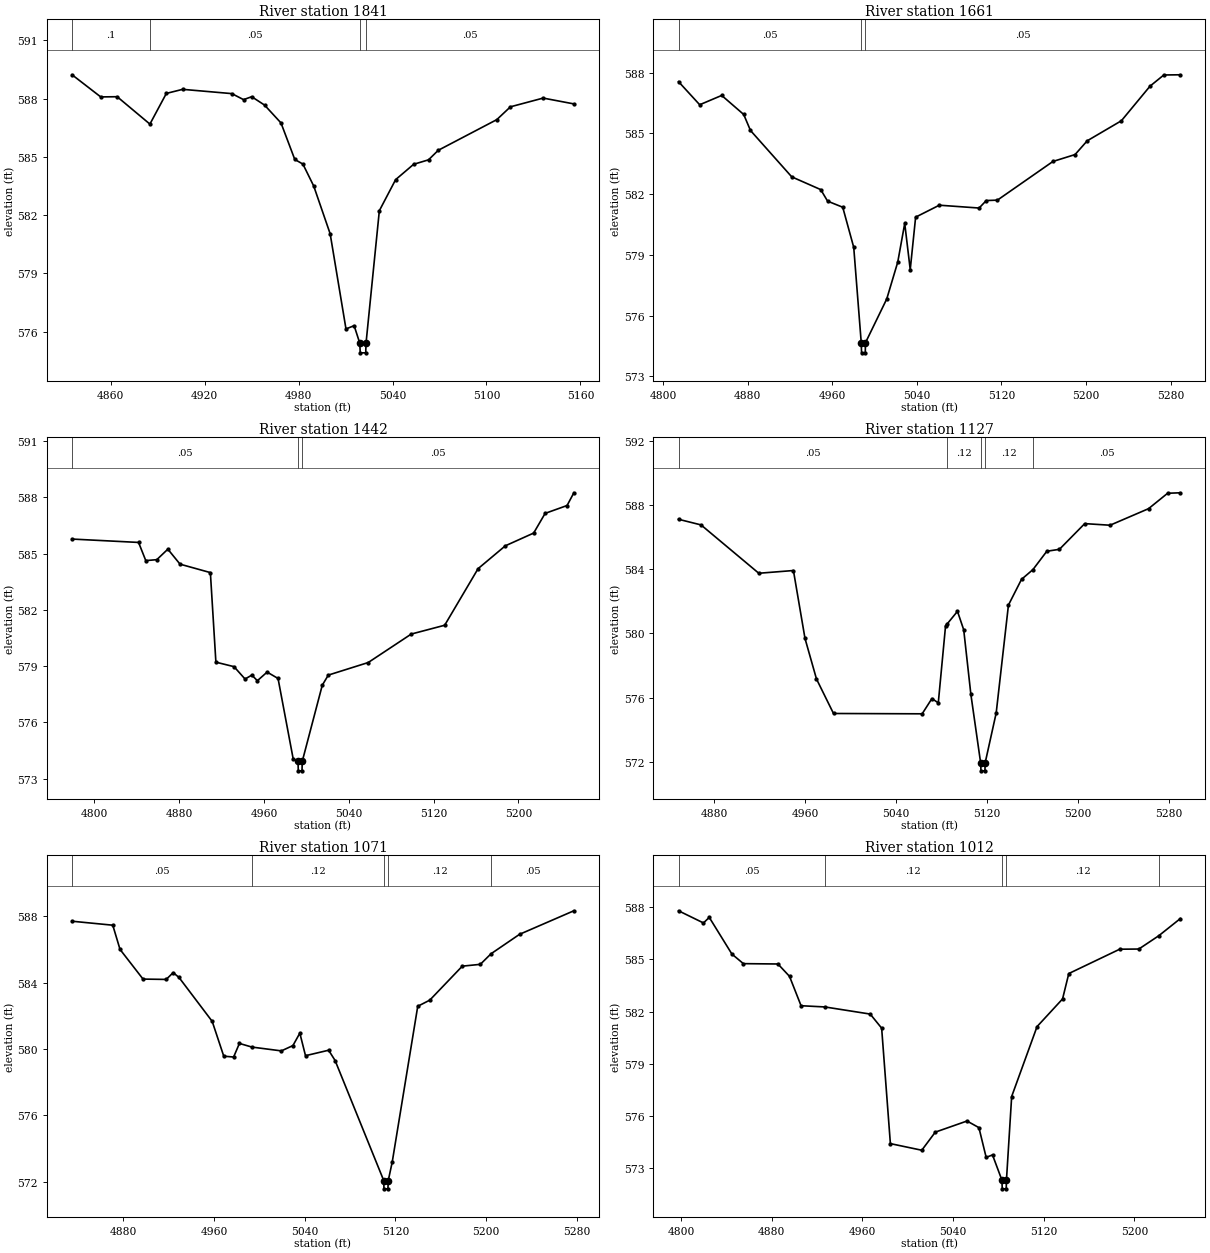
Type RM Length L Ch R = 1 ,1841    ,180,180,180
BEGIN DESCRIPTION:
LWE S 013 5.0
END DESCRIPTION:
XS GIS Cut Line= 3
       2392921.5      7030527.87      2393145.84      7030458.84
      2393195.14      7030388.77
#Sta/Elev= 30
  4835.4  589.23  4853.7  588.09  4864.2   588.1  4885.1  586.69  4895.6  588.27
    4906  588.48  4937.4  588.26  4944.9  587.95  4950.1   588.1  4958.3  587.67
  4968.8  586.75  4977.6  584.87  4982.8  584.63  4989.7   583.5  5000.2  581.04
  5010.3  576.14  5015.5  576.31  5019.1  575.41  5019.4  574.91  5022.9  574.91
  5023.1  575.41  5031.6  582.23    5042  583.83  5053.5  584.62    5063  584.85
  5069.2  585.34  5106.6  586.92  5115.3  587.58  5136.2  588.03  5155.8  587.73
#Mann= 4 ,-1 , 0
  4835.4      .1       0  4885.1     .05       0  5019.1     .05       0
  5023.1     .05       0
Bank Sta=5019.1,5023.1
XS Rating Curve= 0 ,0
Exp/Cntr=0.3,0.1

Type RM Length L Ch R = 1 ,1661    ,219,219,219
BEGIN DESCRIPTION:
LWE S 013 4.5
END DESCRIPTION:
XS GIS Cut Line= 3
      2392999.75      7030673.94       2393216.6      7030612.17
      2393453.86      7030537.18
#Sta/Elev= 30
  4814.8  587.55  4834.8  586.41  4855.6  586.87  4876.4  585.93  4882.8  585.14
  4921.8  582.85  4949.2  582.22  4955.7  581.65    4970  581.35  4980.4  579.37
  4987.5  574.66  4987.8  574.16  4991.3  574.16  4991.5  574.66  5011.6  576.82
    5022  578.64  5028.6  580.55  5033.8  578.27  5038.9  580.86  5061.3  581.45
  5098.9  581.31  5105.7  581.68  5116.2   581.7  5168.7  583.61  5189.6  583.95
  5201.1  584.63  5233.4  585.62  5260.5  587.33  5273.5  587.88  5289.1  587.89
#Mann= 3 ,-1 , 0
  4814.8     .05       0  4987.5    .033       0  4991.5     .05       0
Bank Sta=4987.5,4991.5
XS Rating Curve= 0 ,0
Exp/Cntr=0.3,0.1

Type RM Length L Ch R = 1 ,1442    ,315,315,315
BEGIN DESCRIPTION:
LWE S 013 4.0
END DESCRIPTION:
XS GIS Cut Line= 3
      2393062.18      7030871.77        2393279.        7030810.
      2393515.14      7030735.37
#Sta/Elev= 30
  4779.1  585.78  4841.8   585.6  4848.6  584.63    4859  584.68  4869.4  585.24
  4880.9  584.44  4909.5  583.99  4914.7  579.21  4931.8  578.97  4942.2  578.31
  4948.6  578.52  4953.8  578.22    4963  578.68  4973.3  578.34  4987.6  574.04
  4992.1  573.91  4992.4  573.41  4995.9  573.41  4996.1  573.91    5015  577.98
  5020.7  578.52  5058.3  579.19  5098.9  580.71  5130.4  581.18  5161.9   584.2
  5187.6  585.42  5214.3   586.1  5225.1  587.15  5245.8  587.57  5252.2  588.25
#Mann= 3 ,-1 , 0
  4779.1     .05       0  4992.1     .05       0  4996.1     .05       0
Bank Sta=4992.1,4996.1
XS Rating Curve= 0 ,0
Exp/Cntr=0.3,0.1

Type RM Length L Ch R = 1 ,1127    ,56,56,56
BEGIN DESCRIPTION:
LWE S 013 3.2
END DESCRIPTION:
XS GIS Cut Line= 3
      2393079.43      7031109.43      2393290.56      7031070.92
      2393494.47      7030970.29
#Sta/Elev= 30
  4848.4  587.11  4868.2  586.76  4919.1  583.75  4949.6  583.92  4959.8  579.69
  4969.9  577.17  4984.9  575.02    5063     575  5071.6  575.95  5077.2  575.68
  5083.6  580.47  5085.2  580.61  5094.1  581.38  5099.6  580.23  5105.9  576.21
  5114.5  571.95  5114.8  571.45  5118.3  571.45  5118.5  571.95  5128.2  575.05
    5139  581.77  5150.5  583.37  5160.6  583.98  5172.8  585.12  5183.9  585.24
  5206.2  586.84  5228.5  586.74  5262.4  587.77  5279.2  588.73  5290.4  588.76
#Mann= 5 ,-1 , 0
  4848.4     .05       0  5085.2     .12       0  5114.5    .033       0
  5118.5     .12       0  5160.6     .05       0
Bank Sta=5114.5,5118.5
XS Rating Curve= 0 ,0
Exp/Cntr=0.3,0.1

Type RM Length L Ch R = 1 ,1071    ,59,59,59
BEGIN DESCRIPTION:
LWE S 013 3.0
END DESCRIPTION:
XS GIS Cut Line= 3
      2393087.38      7031161.22      2393298.52      7031122.71
      2393502.96      7031021.82
#Sta/Elev= 30
  4834.8  587.71  4870.7  587.47  4877.1  586.01  4897.4  584.22  4917.8   584.2
    4924  584.61  4929.1  584.32  4958.4  581.67  4968.6  579.57  4977.3  579.52
  4982.4  580.34  4993.4  580.12  5019.4  579.89  5029.6  580.21  5035.7  580.96
  5040.7   579.6  5061.1  579.93  5066.8  579.31  5109.7  572.07  5109.9  571.57
  5113.4  571.57  5113.7  572.07  5117.2  573.19  5139.7  582.58  5150.3  582.95
    5179     585  5194.9  585.11  5204.4  585.75  5229.5  586.92  5277.4  588.34
#Mann= 5 ,-1 , 0
  4834.8     .05       0  4993.4     .12       0  5109.7     .07       0
  5113.7     .12       0  5204.4     .05       0
Bank Sta=5109.7,5113.7
XS Rating Curve= 0 ,0
Exp/Cntr=0.3,0.1

Type RM Length L Ch R = 1 ,1012    ,237,237,237
BEGIN DESCRIPTION:
LWE S 013 2.9
END DESCRIPTION:
XS GIS Cut Line= 3
      2393092.68      7031209.02      2393303.84       7031170.5
      2393508.35      7031069.58
#Sta/Elev= 30
  4797.8   587.8  4819.8   587.1  4824.9  587.42  4844.9  585.31    4855  584.76
  4885.5  584.74  4895.7  584.03  4905.9  582.34  4926.9  582.27  4966.9  581.86
    4977  581.05  4984.7  574.41  5012.4  574.03  5024.3  575.07  5052.3  575.71
  5062.8  575.33  5069.2  573.62  5074.8  573.76  5083.1  572.31  5083.4  571.81
  5086.9  571.81  5087.1  572.31  5091.7  577.12  5114.1  581.14  5136.6  582.73
  5142.1  584.19    5187  585.59  5203.9   585.6  5221.4  586.36  5240.5  587.35
#Mann= 5 ,-1 , 0
  4797.8     .05       0  4926.9     .12       0  5083.1     .07       0
  5087.1     .12       0  5221.4     .05       0
Bank Sta=5083.1,5087.1
XS Rating Curve= 0 ,0
Exp/Cntr=0.3,0.1

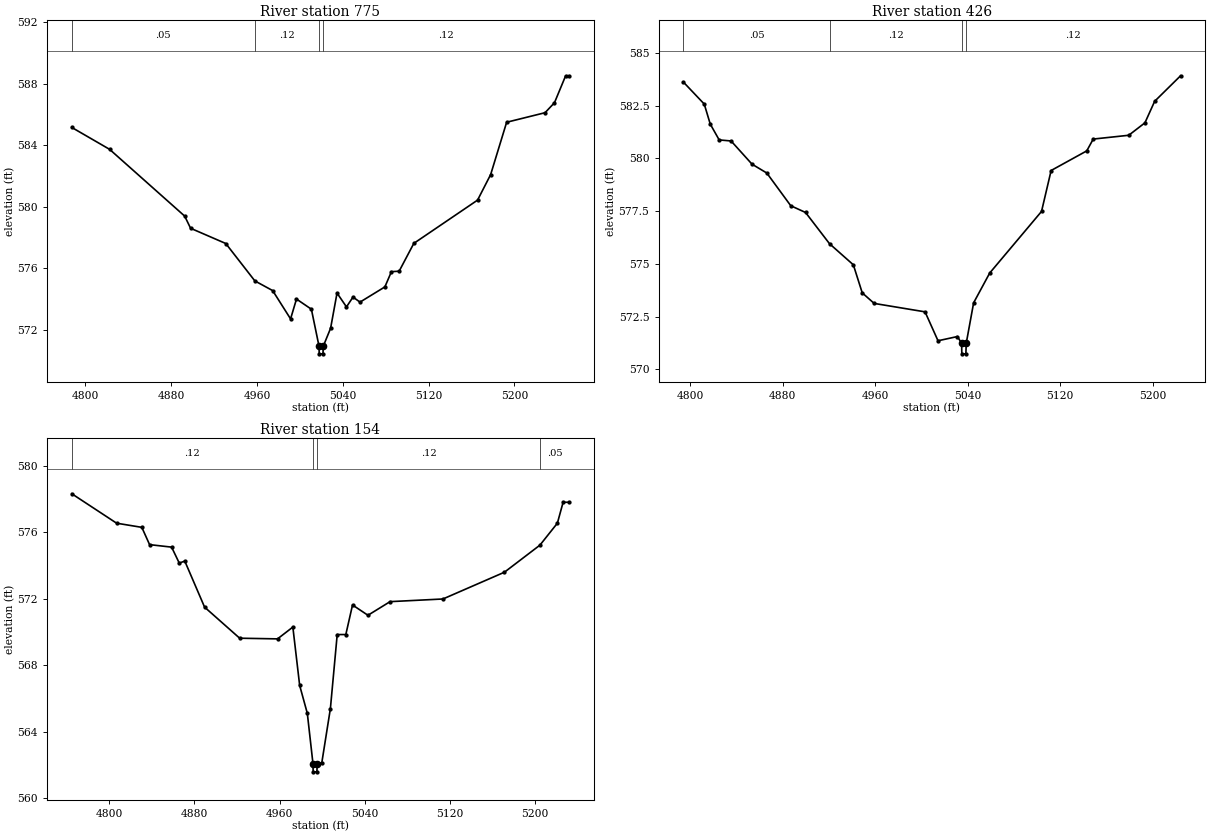
Type RM Length L Ch R = 1 ,775     ,349,349,349
BEGIN DESCRIPTION:
LWE S 013 2.0
END DESCRIPTION:
XS GIS Cut Line= 3
      2393177.68      7031437.38      2393379.52      7031348.42
      2393579.02      7031209.99
#Sta/Elev= 30
  4787.5  585.15  4822.7  583.73  4892.7  579.39  4898.2   578.6    4931  577.61
  4958.1  575.18  4974.7  574.55  4991.4  572.71  4996.9     574  5010.8  573.34
  5017.9  570.94  5018.1  570.44  5021.6  570.44  5021.9  570.94  5028.7   572.1
  5034.7  574.39  5043.5  573.49  5049.6  574.13  5056.1   573.8  5079.3  574.79
  5085.4  575.78  5092.6  575.81  5106.3  577.62  5165.7  580.43  5177.9  582.09
  5192.8  585.49  5228.6  586.11  5237.4  586.76  5247.8  588.51  5250.9  588.51
#Mann= 4 ,-1 , 0
  4787.5     .05       0  4958.1     .12       0  5017.9     .07       0
  5021.9     .12       0
Bank Sta=5017.9,5021.9
XS Rating Curve= 0 ,0
Exp/Cntr=0.3,0.1

Type RM Length L Ch R = 1 ,426     ,272,272,272
BEGIN DESCRIPTION:
LWE S 013 1.0
END DESCRIPTION:
XS GIS Cut Line= 3
      2393279.01        7031660.        2393479.        7031610.
      2393679.04      7031509.98
#Sta/Elev= 30
  4794.2  583.62  4812.2  582.58  4817.4  581.63  4825.1  580.88  4835.4  580.83
  4853.5  579.73  4866.3  579.31    4887  577.76  4899.8  577.44  4920.5  575.96
  4941.1  574.96  4948.8  573.63  4959.1  573.13  5003.1  572.73  5014.3  571.36
  5031.1  571.56  5034.7  571.24  5034.9  570.74  5038.4  570.74  5038.7  571.24
  5045.1  573.16    5059  574.57  5103.8  577.49  5112.1  579.43  5142.9  580.36
  5148.5  580.92  5179.2   581.1  5193.2  581.69  5201.6  582.71    5224  583.92
#Mann= 4 ,-1 , 0
  4794.2     .05       0  4920.5     .12       0  5034.7     .07       0
  5038.7     .12       0
Bank Sta=5034.7,5038.7
XS Rating Curve= 0 ,0
Exp/Cntr=0.3,0.1

Type RM Length L Ch R = 1 ,154     ,0,0,0
BEGIN DESCRIPTION:
LWE S 013 0.4
END DESCRIPTION:
XS GIS Cut Line= 3
      2393358.29      7031868.89      2393500.34      7031906.06
       2393752.6      7031708.24
#Sta/Elev= 30
  4764.7  578.31  4806.8  576.54  4830.5  576.29  4837.8  575.25  4858.5   575.1
  4865.7  574.14  4870.9  574.26  4889.5  571.49  4922.5  569.62  4958.1  569.58
  4972.5  570.29  4978.9  566.78  4986.1   565.1  4991.4  562.08  4991.6  561.58
  4995.1  561.58  4995.4  562.08  4999.7  562.12  5007.8  565.39  5014.2  569.84
  5022.3  569.84  5028.6  571.62  5043.1     571  5063.9  571.82  5113.6  571.98
  5171.4  573.59  5204.8  575.22  5221.2  576.54  5226.6   577.8  5232.1   577.8
#Mann= 4 ,-1 , 0
  4764.7     .12       0  4991.4     .07       0  4995.4     .12       0
  5204.8     .05       0
Bank Sta=4991.4,4995.4
XS Rating Curve= 0 ,0
Exp/Cntr=0.3,0.1

Chan Stop Cuts=-1
Use User Specified Reach Order=0
Composite Channel Slope=5