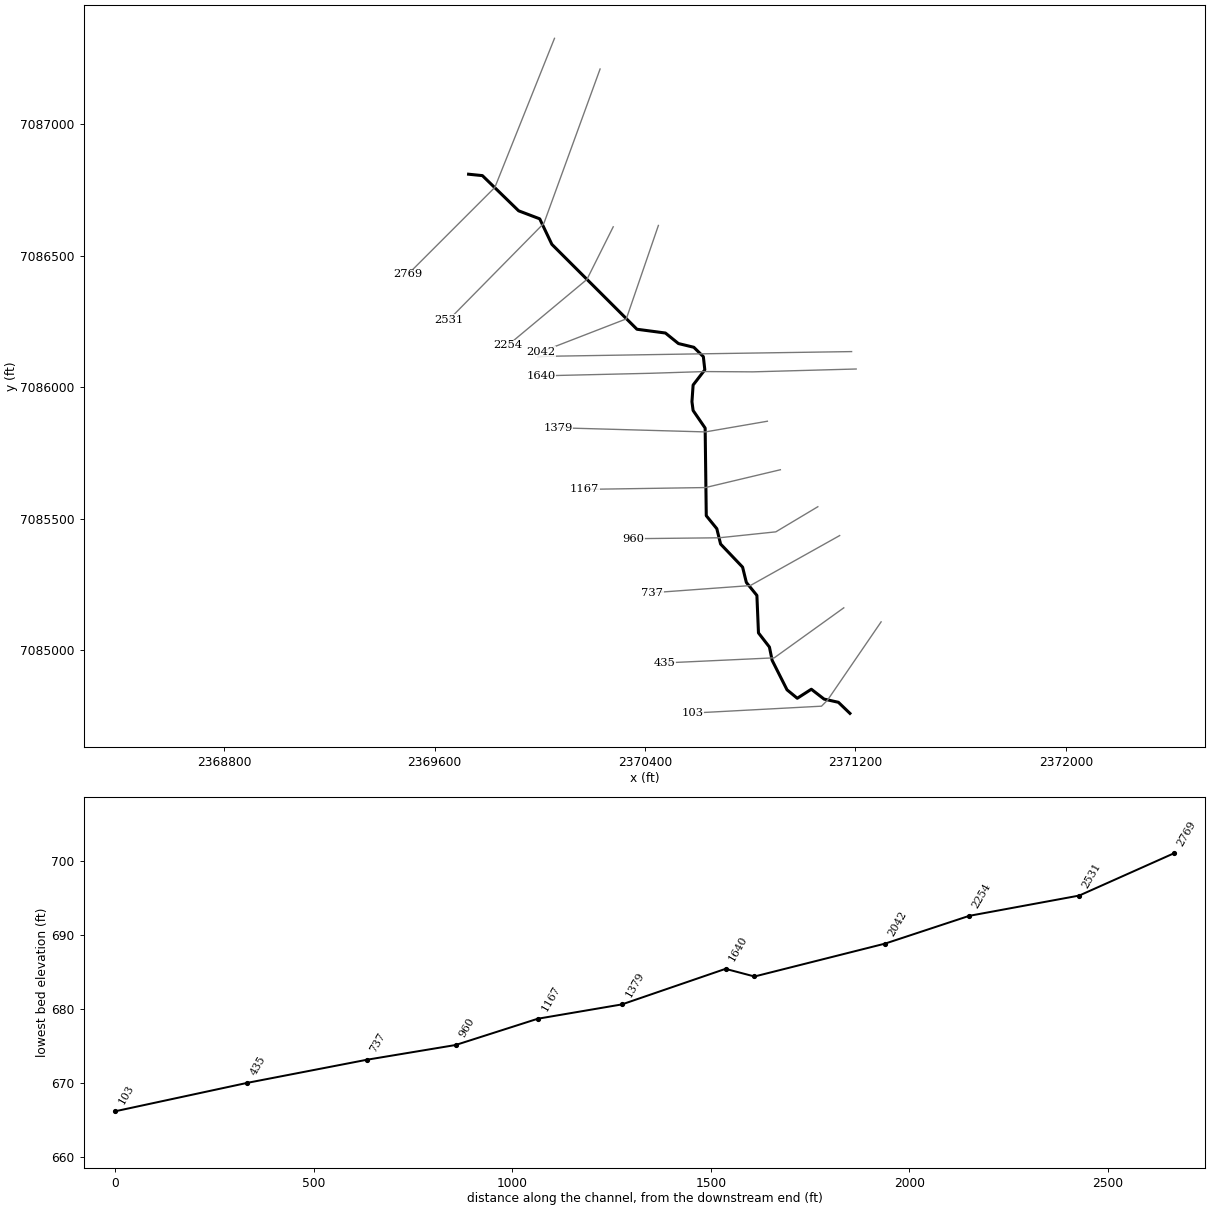
--- LWE S 024.prj (project) ---

Proj Title=LWE S 024 Base Level Engineering
Current Plan=p01
Default Exp/Contr=0.3,0.1
English Units
Geom File=g01
Flow File=f01
Plan File=p01
Y Axis Title=Elevation
X Axis Title(PF)=Main Channel Distance
X Axis Title(XS)=Station
BEGIN DESCRIPTION:
LWE S 024
END DESCRIPTION:
DSS Export Rating Curves= 0
DSS Export Rating Curve Sorted= 0
DSS Export Volume Flow Curves= 0
DXF OffsetX= 0
DXF OffsetY= 0
DXF ScaleX= 1
DXF ScaleY= 10

--- LWE S 024.p01 (plan) ---

Plan Title=Multiple Run
Short Identifier=Multiple
Geom File=g01
Flow File=f01
Subcritical Flow
K Sum by GR= 0
Std Step Tol= 0.01
Critical Tol= 0.01
Num of Std Step Trials= 20
Max Error Tol= 0.3
Flow Tol Ratio= 0.001
Split Flow NTrial= 30
Split Flow Tol= 0.02
Split Flow Ratio= 0.02
Log Output Level= 0
Friction Slope Method= 1
Unsteady Friction Slope Method= 2
Unsteady Bridges Friction Slope Method= 1
Parabolic Critical Depth
Global Vel Dist=  1 , 1 , 1
Global Log Level= 0
CheckData=True
Encroach Param= -1, 0, 0, 0
BEGIN DESCRIPTION:
Multiple Run
END DESCRIPTION:

--- LWE S 024.f01 (steady flow) ---

Flow Title=Multiple
Program Version=4.10
Number of Profiles= 7
Profile Names=10-year,25-year,50-year,1pct_min,100-year,1pct_plu,500-year
River Rch & RM=LWE S 024,Reach-1         ,2769
     186     236     274     159     317     632     423
Boundary for River Rch & Prof#=LWE S 024,Reach-1         , 1
Up Type= 0
Dn Type= 3
Dn Slope=0.011
Boundary for River Rch & Prof#=LWE S 024,Reach-1         , 2
Up Type= 0
Dn Type= 3
Dn Slope=0.011
Boundary for River Rch & Prof#=LWE S 024,Reach-1         , 3
Up Type= 0
Dn Type= 3
Dn Slope=0.011
Boundary for River Rch & Prof#=LWE S 024,Reach-1         , 4
Up Type= 0
Dn Type= 3
Dn Slope=0.011
Boundary for River Rch & Prof#=LWE S 024,Reach-1         , 5
Up Type= 0
Dn Type= 3
Dn Slope=0.011
Boundary for River Rch & Prof#=LWE S 024,Reach-1         , 6
Up Type= 0
Dn Type= 3
Dn Slope=0.011
Boundary for River Rch & Prof#=LWE S 024,Reach-1         , 7
Up Type= 0
Dn Type= 3
Dn Slope=0.011
DSS Import GetInterval= 0
DSS Import GetPeak= 0
DSS Import FillOption= 0

--- LWE S 024.g01 (geometry) ---

Geom Title=Existing Conditions
Program Version=4.10

River Reach=LWE S 024       ,Reach-1
Reach XY= 30
        2369729.        7086810.      2369781.52      7086804.69
      2369919.34      7086670.79      2369999.47      7086640.37
      2370045.66      7086543.34      2370369.21      7086220.52
      2370477.42      7086206.17      2370526.86      7086166.15
      2370585.43      7086151.98      2370621.64      7086116.34
      2370627.23      7086066.17      2370582.74      7086008.42
      2370578.29      7085944.94      2370582.71       7085911.6
      2370628.48      7085844.78      2370632.75      7085511.55
      2370672.86      7085462.17      2370687.16      7085403.95
      2370770.84      7085316.05      2370785.14      7085257.83
      2370825.24      7085208.44      2370831.25      7085065.93
      2370872.88      7085012.18      2370883.16      7084961.72
      2370939.76      7084849.61      2370978.78      7084817.46
      2371032.22      7084851.77      2371080.58      7084814.32
      2371135.14      7084802.12        2371179.        7084760.

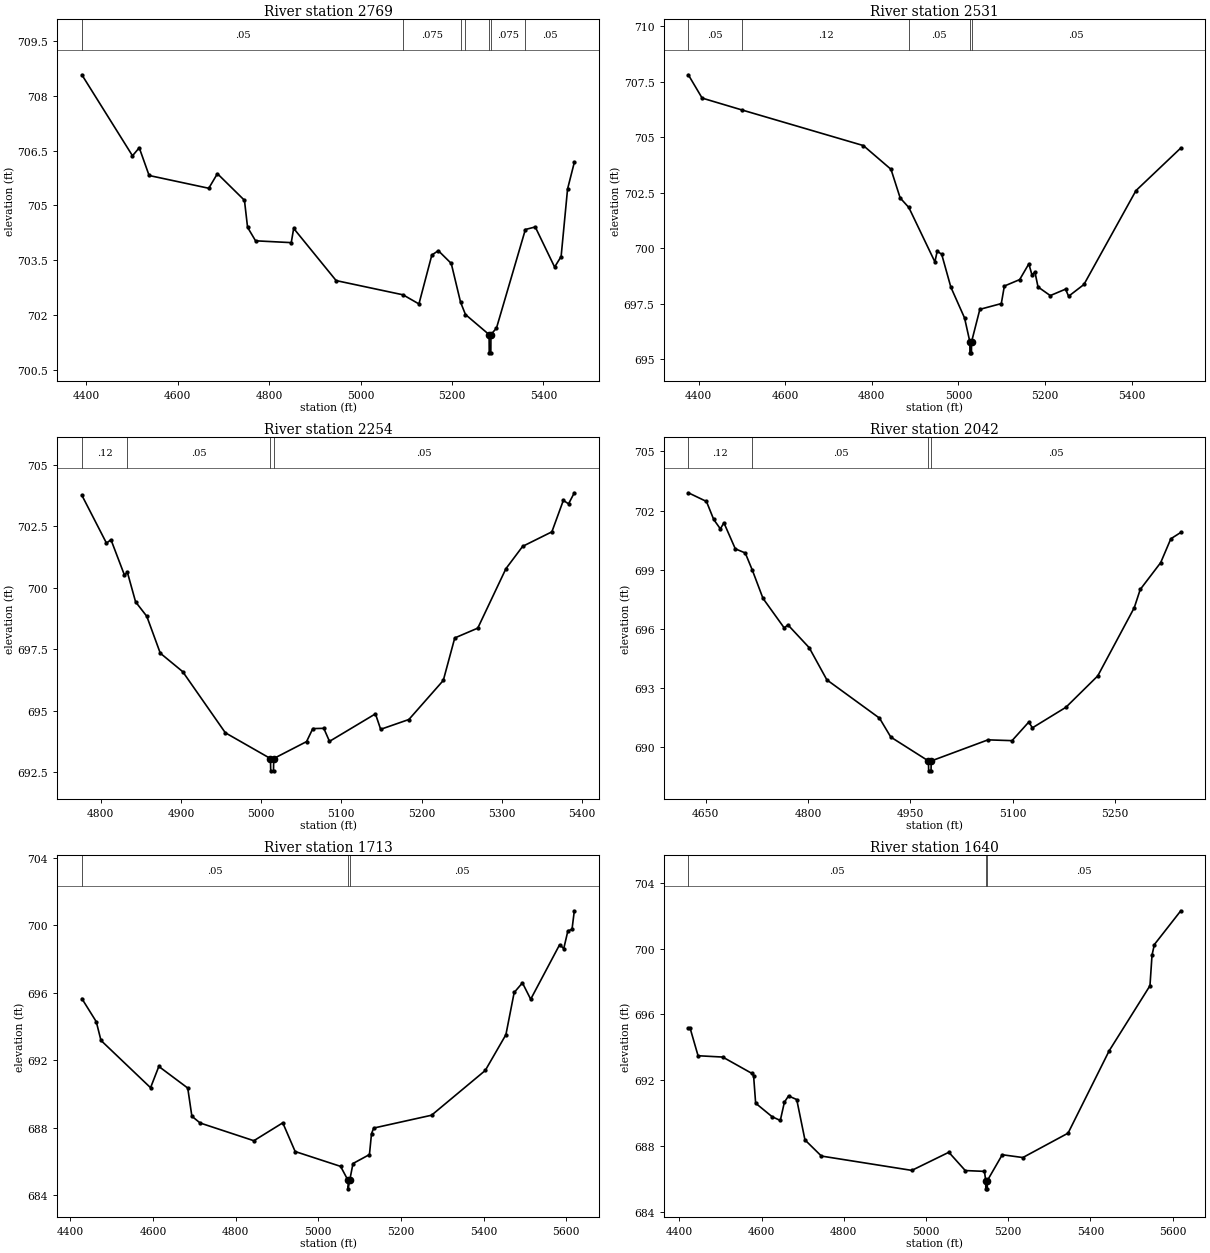
Type RM Length L Ch R = 1 ,2769    ,238,238,238
BEGIN DESCRIPTION:
LWE S 024 8.0
END DESCRIPTION:
XS GIS Cut Line= 3
      2370055.65      7087326.63        2369829.        7086760.
      2369498.56      7086429.56
#Sta/Elev= 30
  4389.9  708.58  4500.7  706.36  4515.5  706.58  4537.1  705.82  4667.6  705.47
  4686.5  705.87  4745.7  705.14  4752.5   704.4    4770  704.03  4848.1  703.98
  4853.4  704.37  4946.3  702.94  5092.7  702.55  5127.5   702.3  5155.7  703.64
  5169.9  703.76  5198.2  703.41  5218.5  702.35  5229.3  702.01    5281  701.46
  5281.3  700.96  5284.8  700.96    5285  701.46  5297.2  701.64  5360.4  704.34
    5382  704.41  5424.4  703.31  5438.6   703.6  5452.7  705.45  5467.5  706.18
#Mann= 7 ,-1 , 0
  4389.9     .05       0  5092.7    .075       0  5218.5     .05       0
  5229.3    .075       0    5281     .05       0    5285    .075       0
  5360.4     .05       0
Bank Sta=5281,5285
XS Rating Curve= 0 ,0
Exp/Cntr=0.3,0.1

Type RM Length L Ch R = 1 ,2531    ,277,277,277
BEGIN DESCRIPTION:
LWE S 024 7.0
END DESCRIPTION:
XS GIS Cut Line= 3
        2370229.      7087210.01      2370015.51      7086623.56
      2369654.93      7086257.55
#Sta/Elev= 30
  4375.9  707.81  4407.8  706.76  4500.6  706.22  4780.3  704.62  4844.2  703.55
  4865.4  702.26  4885.4  701.83  4945.6  699.38  4950.9  699.85  4961.2  699.73
  4982.5  698.24  5014.2  696.85  5026.4  695.78  5026.6  695.28  5030.1  695.28
  5030.4  695.78  5049.5  697.24  5099.1   697.5  5106.1  698.29  5141.5  698.58
  5162.7  699.29  5169.8   698.8  5176.8  698.92  5183.9  698.25  5212.2  697.86
  5247.5  698.15  5254.6  697.83    5290  698.36  5410.2  702.59  5513.8  704.51
#Mann= 5 ,-1 , 0
  4375.9     .05       0  4500.6     .12       0  4885.4     .05       0
  5026.4    .033       0  5030.4     .05       0
Bank Sta=5026.4,5030.4
XS Rating Curve= 0 ,0
Exp/Cntr=0.3,0.1

Type RM Length L Ch R = 1 ,2254    ,212,212,212
BEGIN DESCRIPTION:
LWE S 024 6.0
END DESCRIPTION:
XS GIS Cut Line= 3
      2370278.99      7086609.97        2370179.        7086410.
      2369878.99      7086159.99
#Sta/Elev= 30
  4776.4  703.77  4807.1  701.82  4812.7  701.96  4829.5  700.52  4833.2  700.63
  4843.4  699.43  4857.4  698.84  4874.2  697.34  4902.1  696.59  4955.3   694.1
  5011.6  693.05  5011.9  692.55  5015.4  692.55  5015.6  693.05  5056.6  693.74
  5064.4  694.27  5078.1  694.28  5085.2  693.75  5142.5  694.87    5149  694.24
  5184.2  694.64  5227.1  696.23  5241.4  697.96  5270.1  698.36  5305.2  700.78
  5326.1  701.69  5362.5  702.28  5376.8  703.56  5383.3  703.42  5390.5  703.87
#Mann= 4 ,-1 , 0
  4776.4     .12       0  4833.2     .05       0  5011.6    .033       0
  5015.6     .05       0
Bank Sta=5011.6,5015.6
XS Rating Curve= 0 ,0
Exp/Cntr=0.3,0.1

Type RM Length L Ch R = 1 ,2042    ,329,329,329
BEGIN DESCRIPTION:
LWE S 024 5.0
END DESCRIPTION:
XS GIS Cut Line= 3
      2370450.71      7086615.17      2370328.71      7086259.94
       2370005.4      7086134.74
#Sta/Elev= 30
  4624.4   702.9    4651  702.46  4661.6  701.55  4671.4  701.07  4676.6  701.38
  4693.3  700.06  4707.9  699.85  4718.4  698.97  4733.9  697.55  4765.1  696.05
  4770.4  696.21  4801.7  695.05  4827.6  693.42  4904.8  691.48  4921.4  690.52
  4976.6  689.31  4976.9  688.81  4980.4  688.81  4980.6  689.31  5063.9  690.38
  5099.2  690.34  5123.7  691.28  5129.1  690.99  5178.2  692.03  5224.9  693.62
  5278.5  697.08  5287.2     698  5317.2  699.36  5332.1  700.57  5346.7  700.89
#Mann= 4 ,-1 , 0
  4624.4     .12       0  4718.4     .05       0  4976.6     .04       0
  4980.6     .05       0
Bank Sta=4976.6,4980.6
XS Rating Curve= 0 ,0
Exp/Cntr=0.3,0.1

Type RM Length L Ch R = 1 ,1713    ,73,73,73
BEGIN DESCRIPTION:
LWE S 024 4.0
END DESCRIPTION:
XS GIS Cut Line= 3
      2371185.28      7086135.57      2370612.94      7086127.06
      2369993.42      7086117.14
#Sta/Elev= 30
  4427.6  695.65  4462.5  694.28  4473.9  693.17  4593.9  690.37  4613.9  691.63
  4683.9  690.35  4693.9  688.68  4713.9  688.28  4843.9  687.23  4913.9  688.29
  4943.9  686.59  5053.9  685.71  5071.9  684.88  5072.2  684.38  5075.9  684.88
  5083.9  685.88  5123.7  686.41  5128.7  687.65    5134  687.98    5274  688.74
    5404  691.39    5454  693.51    5474  696.01    5494  696.58    5514  695.61
    5584  698.84    5594  698.61    5604  699.66    5614  699.75  5619.6  700.85
#Mann= 3 ,-1 , 0
  4427.6     .05       0  5071.9    .033       0  5075.9     .05       0
Bank Sta=5071.9,5075.9
XS Rating Curve= 0 ,0
Exp/Cntr=0.3,0.1

Type RM Length L Ch R = 1 ,1640    ,261,261,261
BEGIN DESCRIPTION:
Mapping XS 681675ce
END DESCRIPTION:
XS GIS Cut Line= 5
       2371202.7      7086069.39      2370809.87      7086058.54
       2370625.4      7086059.62      2370421.41      7086053.11
      2370004.77      7086043.34
#Sta/Elev= 30
  4421.7  695.16  4426.1  695.16  4445.4  693.49  4505.4  693.41  4575.5  692.43
  4580.5  692.29  4585.5  690.61  4625.5  689.79  4645.5  689.56  4655.5  690.67
  4665.5  691.05  4685.5  690.83  4705.5  688.38  4745.5   687.4  4965.5  686.53
  5055.6  687.63  5095.6  686.52  5142.3  686.47  5145.3  685.91  5145.6  685.41
  5149.1  685.41  5149.3  685.91  5185.6  687.48  5235.7  687.31  5345.7  688.79
  5445.7  693.79    5545  697.74    5550   699.6  5555.7  700.24    5620  702.29
#Mann= 3 ,-1 , 0
  4421.7     .05       0  5145.3    .033       0  5149.3     .05       0
Bank Sta=5145.3,5149.3
XS Rating Curve= 0 ,0
Exp/Cntr=0.3,0.1

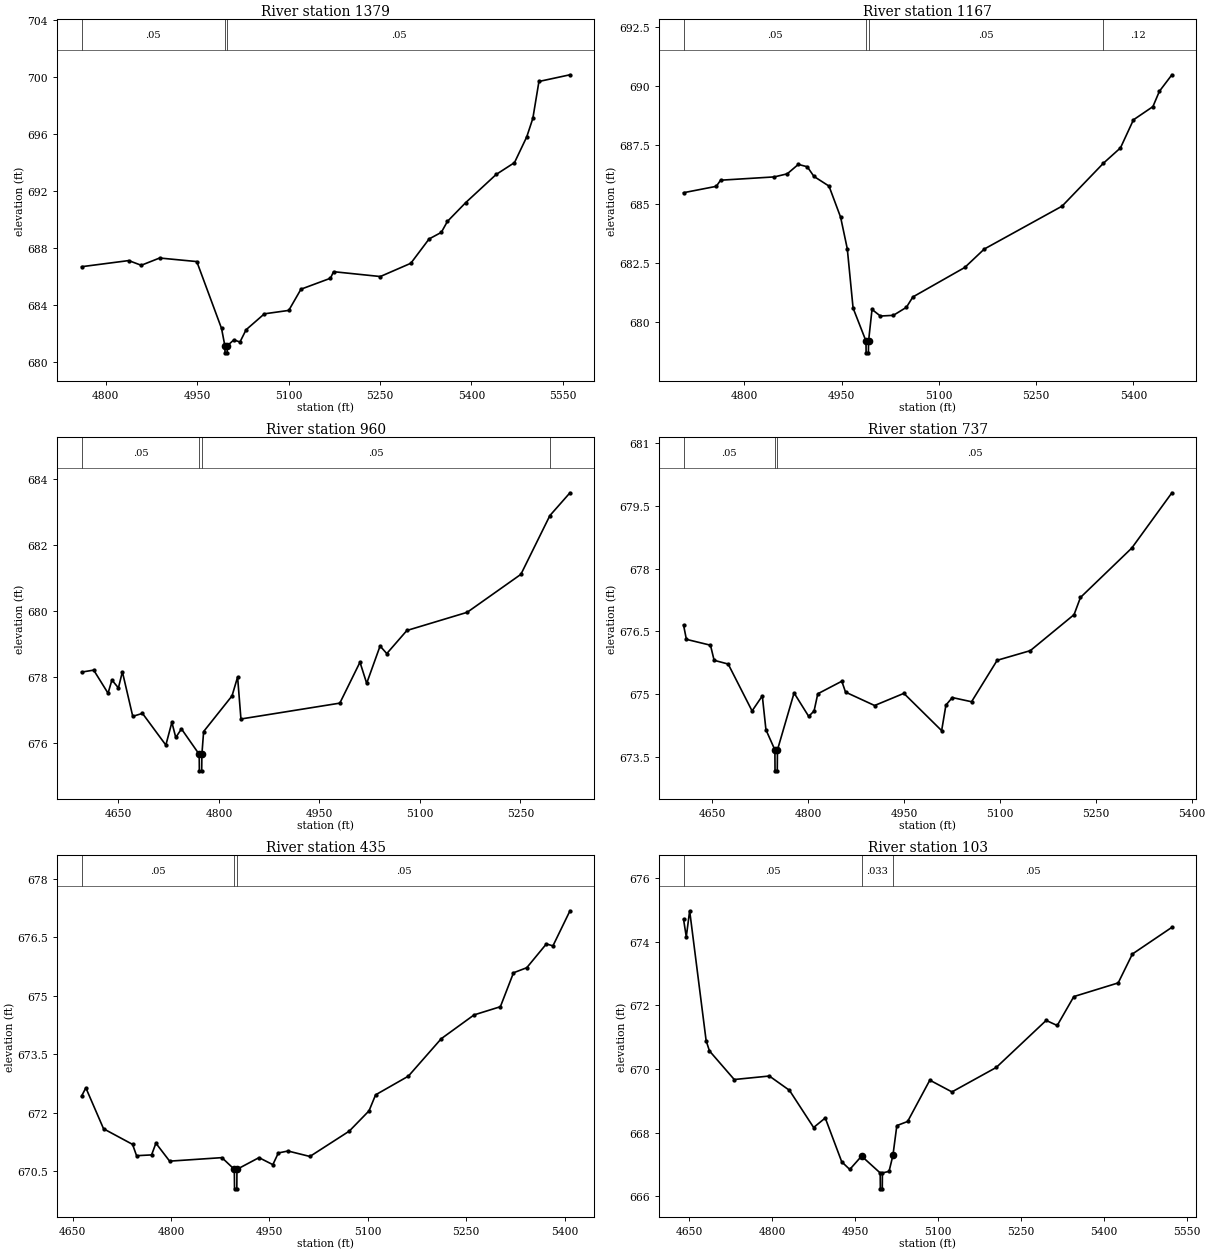
Type RM Length L Ch R = 1 ,1379    ,212,212,212
BEGIN DESCRIPTION:
LWE S 024 3.0
END DESCRIPTION:
XS GIS Cut Line= 3
      2370865.08      7085870.79      2370629.36      7085830.15
      2370068.08      7085845.97
#Sta/Elev= 30
  4760.8  686.67    4838   687.1  4858.5  686.77  4888.7  687.28  4949.6  687.03
  4990.2  682.33  4995.6  681.12  4995.9  680.62  4999.4  680.62  4999.6  681.12
  5010.4  681.53  5020.4  681.38  5030.4  682.24  5060.4  683.36  5100.4   683.6
  5120.4  685.09  5168.8  685.86  5173.8  686.32  5250.5  685.98  5300.5  686.91
  5330.5  688.62  5350.5  689.08  5360.5  689.85  5390.5  691.17  5440.5  693.15
  5470.5  693.98  5490.6  695.79  5500.6  697.09  5510.6  699.68  5561.5  700.15
#Mann= 3 ,-1 , 0
  4760.8     .05       0  4995.6    .033       0  4999.6     .05       0
Bank Sta=4995.6,4999.6
XS Rating Curve= 0 ,0
Exp/Cntr=0.3,0.1

Type RM Length L Ch R = 1 ,1167    ,207,207,207
BEGIN DESCRIPTION:
Mapping XS 5fff195e
END DESCRIPTION:
XS GIS Cut Line= 3
      2370914.51      7085686.32      2370629.81      7085618.61
       2370169.7      7085611.67
#Sta/Elev= 30
  4706.5  685.48  4756.9  685.75  4763.6  686.01  4846.4  686.15  4866.3  686.28
  4883.4  686.68  4897.2  686.58  4907.5  686.17  4930.7  685.76  4948.6  684.44
  4958.9   683.1  4967.8  680.59  4987.7  679.19  4987.9  678.69  4991.4  678.69
  4991.7  679.19    4997  680.53  5009.9  680.25  5029.9  680.28    5050  680.62
    5060  681.06    5140  682.31    5170  683.09    5290  684.91  5353.7  686.73
    5380  687.38    5400  688.57    5430  689.13    5440  689.78  5459.3  690.48
#Mann= 4 ,-1 , 0
  4706.5     .05       0  4987.7    .033       0  4991.7     .05       0
  5353.7     .12       0
Bank Sta=4987.7,4991.7
XS Rating Curve= 0 ,0
Exp/Cntr=0.3,0.1

Type RM Length L Ch R = 1 ,960     ,223,223,223
BEGIN DESCRIPTION:
Mapping XS 4c3611d2
END DESCRIPTION:
XS GIS Cut Line= 4
      2371056.93      7085545.72      2370897.17      7085450.21
      2370681.89      7085427.64       2370355.5      7085424.17
#Sta/Elev= 30
  4595.1  678.14  4613.1   678.2  4634.5   677.5  4640.3   677.9    4650  677.66
  4655.9  678.15  4671.4   676.8  4685.9  676.89  4720.8  675.93  4729.8  676.62
  4735.6  676.16  4744.1  676.42  4770.6  675.65  4770.8  675.15  4774.3  675.15
  4774.6  675.65  4777.2  676.34  4819.6  677.42  4827.9  677.99  4832.9  676.72
  4980.5   677.2  5010.6  678.44  5020.6   677.8  5040.6  678.93  5050.6   678.7
  5080.6   679.4  5170.6  679.95  5250.8   681.1  5294.1  682.88  5324.1  683.57
#Mann= 4 ,-1 , 0
  4595.1     .05       0  4770.6    .033       0  4774.6     .05       0
  5294.1     .12       0
Bank Sta=4770.6,4774.6
XS Rating Curve= 0 ,0
Exp/Cntr=0.3,0.1

Type RM Length L Ch R = 1 ,737     ,302,302,302
BEGIN DESCRIPTION:
Mapping XS 07ac2773
END DESCRIPTION:
XS GIS Cut Line= 3
      2371139.88      7085436.02      2370800.06      7085245.93
      2370426.33      7085218.58
#Sta/Elev= 30
  4604.9  676.65  4609.3  676.31    4647  676.17  4652.7  675.81  4674.7  675.72
  4712.1   674.6  4728.1  674.96  4733.8  674.15  4747.8  673.67    4748  673.17
  4751.5  673.17  4751.8  673.67  4777.8  675.03  4800.7  674.47  4809.1   674.6
  4814.9  675.01  4852.5  675.31  4858.3  675.05  4903.8  674.73  4949.6  675.02
  5008.7  674.13  5015.4  674.74  5025.4  674.92  5055.5  674.82  5095.6  675.81
  5147.4  676.04  5215.9   676.9  5225.9  677.31  5306.2  678.49    5369  679.81
#Mann= 3 ,-1 , 0
  4604.9     .05       0  4747.8    .033       0  4751.8     .05       0
Bank Sta=4747.8,4751.8
XS Rating Curve= 0 ,0
Exp/Cntr=0.3,0.1

Type RM Length L Ch R = 1 ,435     ,332,332,332
BEGIN DESCRIPTION:
Mapping XS f9d45553
END DESCRIPTION:
XS GIS Cut Line= 3
      2371155.56      7085161.32       2370891.2      7084971.19
      2370472.99      7084951.71
#Sta/Elev= 30
  4663.8  672.43  4670.2  672.64  4697.2  671.59  4741.4  671.19  4747.5   670.9
  4770.4  670.92    4777  671.22  4797.9  670.76  4877.6  670.85  4896.5  670.55
  4896.8  670.05  4900.3  670.05  4900.5  670.55  4934.1  670.85  4955.2  670.67
  4963.6  670.97  4978.3  671.02  5011.7  670.88  5071.7  671.53  5101.8  672.05
  5111.8  672.46  5161.8  672.94  5211.9   673.9  5261.9  674.51    5302  674.72
    5322  675.59  5342.2  675.72  5372.1  676.33  5382.1  676.28  5408.1  677.18
#Mann= 3 ,-1 , 0
  4663.8     .05       0  4896.5    .033       0  4900.5     .05       0
Bank Sta=4896.5,4900.5
XS Rating Curve= 0 ,0
Exp/Cntr=0.3,0.1

Type RM Length L Ch R = 1 ,103     ,0,0,0
BEGIN DESCRIPTION:
LWE S 024 1.0
END DESCRIPTION:
XS GIS Cut Line= 4
      2371297.53      7085107.94      2371094.26      7084810.94
      2371070.95      7084787.38      2370581.99      7084761.22
#Sta/Elev= 30
  4640.1  674.71    4645  674.16  4651.1  674.98  4680.9  670.89  4686.9  670.57
  4731.7  669.67  4795.1  669.78  4831.5  669.33  4875.2  668.16  4896.2  668.46
    4926  667.08  4940.5  666.84  4961.9  667.26  4995.5  666.73  4995.8  666.23
  4999.3  666.23  4999.5  666.73  5011.5  666.78  5018.5  667.28  5025.6  668.22
  5045.1  668.35  5085.2  669.65  5125.2  669.28  5205.3  670.05  5295.5  671.53
  5315.5  671.37  5345.5  672.28  5425.7  672.71  5451.4  673.62  5522.8  674.46
#Mann= 3 ,-1 , 0
  4640.1     .05       0  4961.9    .033       0  5018.5     .05       0
Bank Sta=4961.9,5018.5
XS Rating Curve= 0 ,0
Exp/Cntr=0.3,0.1

Chan Stop Cuts=-1
Use User Specified Reach Order=0
Composite Channel Slope=5