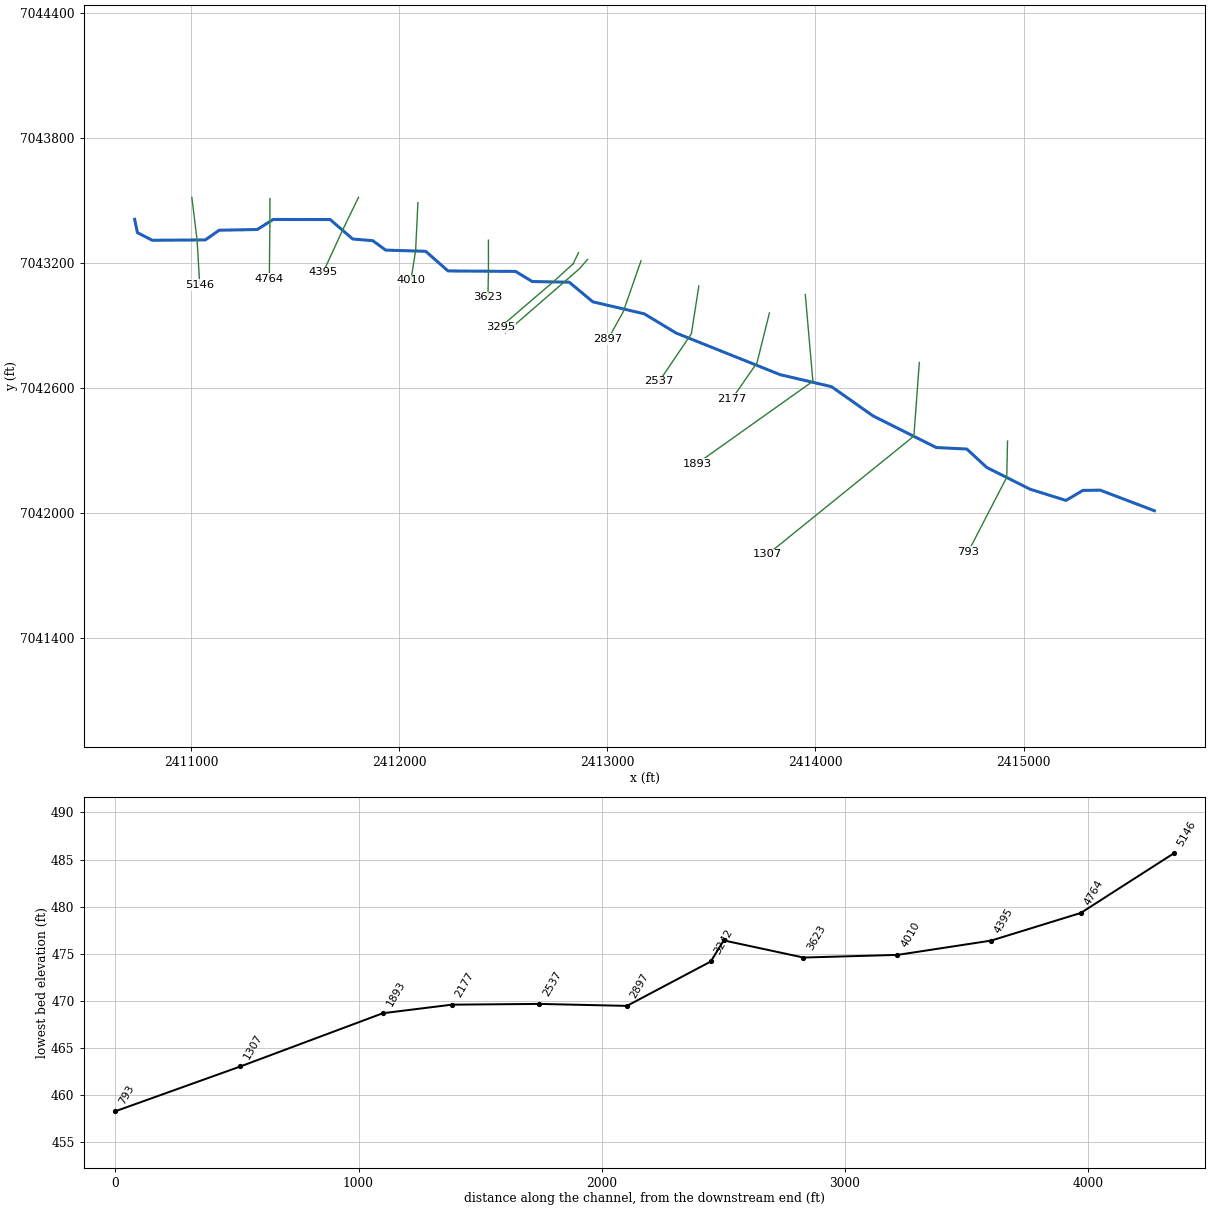
--- LWE S 027.prj (project) ---

Proj Title=LWE S 027 Base Level Engineering
Current Plan=p01
Default Exp/Contr=0.3,0.1
English Units
Geom File=g01
Flow File=f01
Plan File=p01
Y Axis Title=Elevation
X Axis Title(PF)=Main Channel Distance
X Axis Title(XS)=Station
BEGIN DESCRIPTION:
LWE S 027
END DESCRIPTION:
DSS Export Rating Curves= 0
DSS Export Rating Curve Sorted= 0
DSS Export Volume Flow Curves= 0
DXF OffsetX= 0
DXF OffsetY= 0
DXF ScaleX= 1
DXF ScaleY= 10

--- LWE S 027.p01 (plan) ---

Plan Title=Multiple Run
Short Identifier=Multiple
Geom File=g01
Flow File=f01
Subcritical Flow
K Sum by GR= 0
Std Step Tol= 0.01
Critical Tol= 0.01
Num of Std Step Trials= 20
Max Error Tol= 0.3
Flow Tol Ratio= 0.001
Split Flow NTrial= 30
Split Flow Tol= 0.02
Split Flow Ratio= 0.02
Log Output Level= 0
Friction Slope Method= 1
Unsteady Friction Slope Method= 2
Unsteady Bridges Friction Slope Method= 1
Parabolic Critical Depth
Global Vel Dist=  1 , 1 , 1
Global Log Level= 0
CheckData=True
Encroach Param= -1, 0, 0, 0
BEGIN DESCRIPTION:
Multiple Run
END DESCRIPTION:

--- LWE S 027.f01 (steady flow) ---

Flow Title=Multiple
Number of Profiles=7
Profile Names=10-year,25-year,50-year,1pct_min,100-year,1pct_plu,500-year
River Rch & RM= LWE S 027,Reach-1,5146
     713     983    1207     735    1467    2928    2165
Boundary for River Rch & Prof#=LWE S 027,Reach-1,1
Up Type=0
Dn Type=3
Dn Slope=0.005
Boundary for River Rch & Prof#=LWE S 027,Reach-1,2
Up Type=0
Dn Type=3
Dn Slope=0.005
Boundary for River Rch & Prof#=LWE S 027,Reach-1,3
Up Type=0
Dn Type=3
Dn Slope=0.005
Boundary for River Rch & Prof#=LWE S 027,Reach-1,4
Up Type=0
Dn Type=3
Dn Slope=0.005
Boundary for River Rch & Prof#=LWE S 027,Reach-1,5
Up Type=0
Dn Type=3
Dn Slope=0.005
Boundary for River Rch & Prof#=LWE S 027,Reach-1,6
Up Type=0
Dn Type=3
Dn Slope=0.005
Boundary for River Rch & Prof#=LWE S 027,Reach-1,7
Up Type=0
Dn Type=3
Dn Slope=0.005

--- LWE S 027.g01 (geometry) ---

Geom Title=Existing Conditions
Program Version=4.10

River Reach=LWE S 027       ,Reach-1
Reach XY= 30
        2410729.        7043410.      2410742.23      7043346.12
      2410813.76       7043309.5       2411068.5      7043311.22
      2411134.94      7043357.74      2411318.49      7043361.22
      2411394.22      7043409.48      2411668.56      7043408.94
      2411776.58      7043315.54      2411873.02      7043307.64
      2411934.94      7043262.26      2412127.53      7043256.45
      2412234.86      7043162.07      2412558.97      7043159.93
      2412639.51      7043111.22      2412817.05      7043108.08
      2412930.56      7043013.82      2413177.42      7042956.17
      2413330.58      7042863.83      2413830.58      7042663.83
      2414077.42      7042606.17      2414276.71      7042465.85
      2414580.56      7042313.76      2414727.53      7042306.45
      2414822.95      7042218.16      2415030.58      7042113.83
        2415204.       7042059.6      2415284.97      7042107.81
      2415368.45       7042108.9        2415629.        7042010.

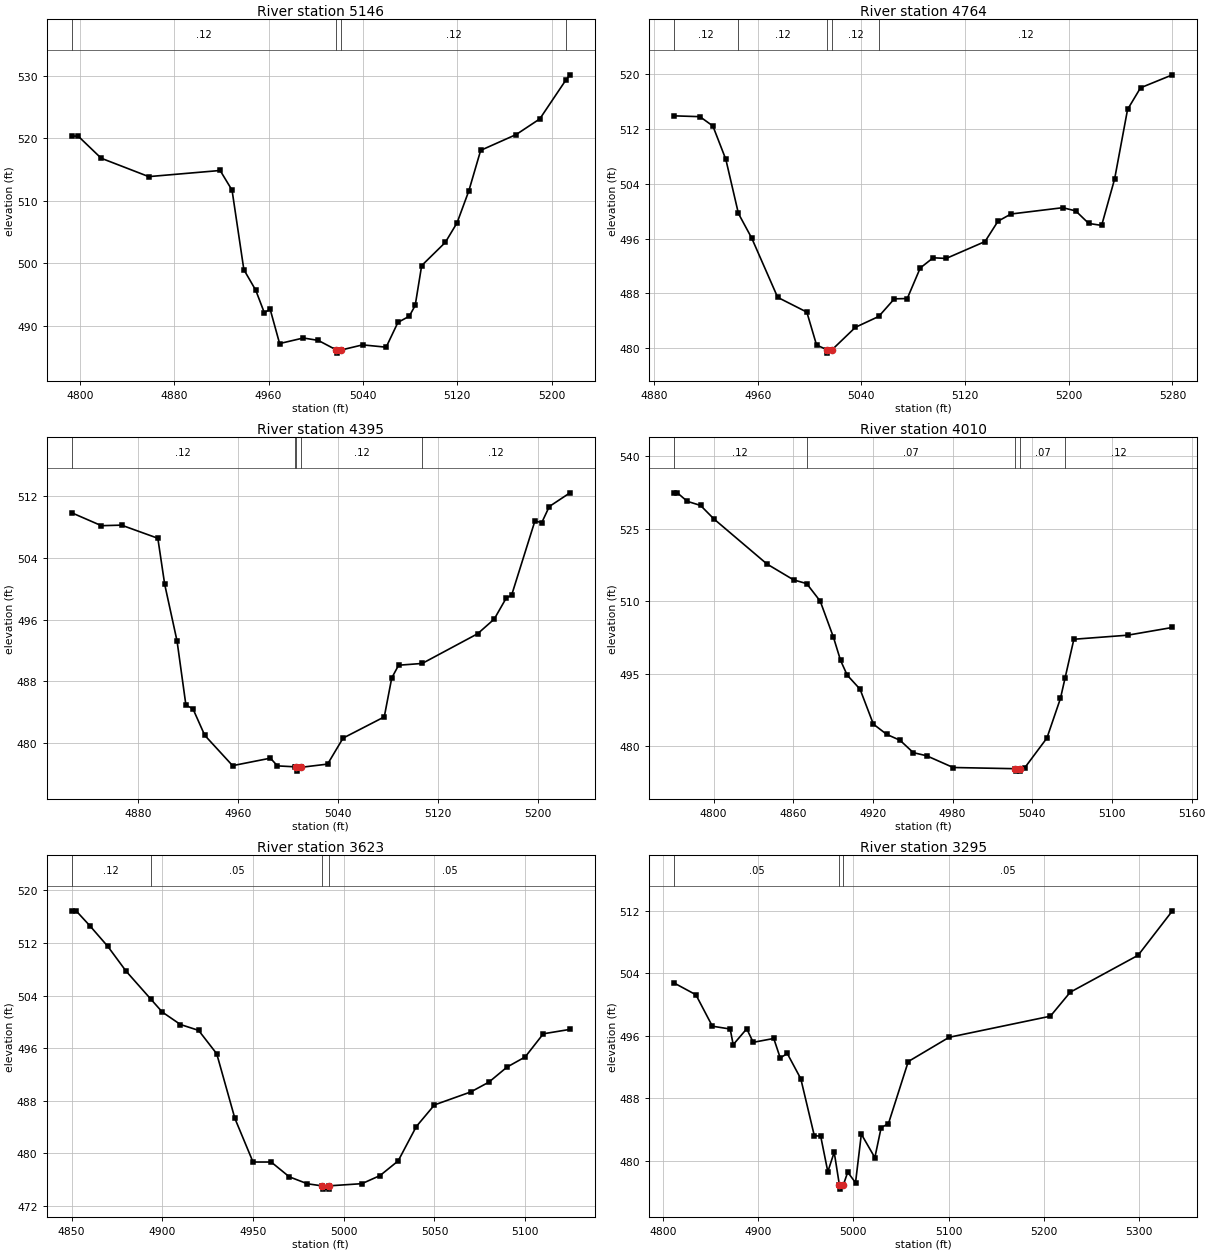
Type RM Length L Ch R = 1 ,5146    ,382,382,382
BEGIN DESCRIPTION:
LWE S 027 13.0
END DESCRIPTION:
XS GIS Cut Line= 3
      2411003.86      7043514.96        2411029.        7043310.
      2411041.81      7043094.47
#Sta/Elev= 30
  4793.1  520.37  4798.7  520.35  4818.2  516.82  4858.5  513.88    4919  514.86
  4929.1  511.71  4939.1     499  4949.2   495.7  4956.4  492.13  4961.4  492.66
  4969.4  487.18  4989.5  488.07  5002.1  487.69  5017.6  486.15  5017.9  485.65
  5021.6  486.15  5039.7  486.97  5059.7   486.6  5069.7  490.57  5079.3  491.55
  5084.3  493.27  5089.8  499.65  5109.8  503.35  5119.8  506.49  5129.8  511.62
  5139.8  518.08  5169.9  520.61  5189.9  523.11  5212.1  529.35  5215.5  530.16
#Mann= 4 ,-1 , 0
  4793.1     .12       0  5017.6     .07       0  5021.6     .12       0
  5212.1     .05       0
Bank Sta=5017.6,5021.6
XS Rating Curve= 0 ,0
Exp/Cntr=0.3,0.1

Type RM Length L Ch R = 1 ,4764    ,369,369,369
BEGIN DESCRIPTION:
LWE S 027 12.0
END DESCRIPTION:
XS GIS Cut Line= 3
        2411379.      7043510.01        2411379.        7043410.
      2411376.04      7043125.42
#Sta/Elev= 30
  4895.4  513.86  4915.4  513.74  4925.4  512.38  4935.4  507.52  4945.1  499.65
  4955.4  496.05  4975.4  487.44  4997.9  485.29  5005.4   480.5  5013.4  479.82
  5013.7  479.32  5017.4  479.82  5035.4  483.08  5053.4  484.66  5065.4  487.22
  5075.4  487.27  5085.4  491.71  5095.4   493.2  5105.4   493.1  5135.4  495.56
  5145.4  498.52  5155.4  499.57  5195.4  500.49  5205.4  500.02  5215.4   498.2
  5225.4  497.91  5235.4  504.66  5245.4  514.79  5255.4  517.94    5280  519.83
#Mann= 5 ,-1 , 0
  4895.4     .12       0  4945.1     .12       0  5013.4     .07       0
  5017.4     .12       0  5053.4     .12       0
Bank Sta=5013.4,5017.4
XS Rating Curve= 0 ,0
Exp/Cntr=0.3,0.1

Type RM Length L Ch R = 1 ,4395    ,385,385,385
BEGIN DESCRIPTION:
LWE S 027 11.0
END DESCRIPTION:
XS GIS Cut Line= 3
      2411804.66      7043516.04        2411729.        7043360.
      2411634.38      7043154.88
#Sta/Elev= 30
  4826.6  509.88  4850.5   508.2  4866.6  508.27  4895.7  506.57  4901.2  500.59
  4911.1  493.24  4918.2  484.93  4923.8  484.47  4933.3  481.02  4955.6  477.09
  4985.9  478.06  4991.5  477.06  5005.4  476.94  5006.7  476.88    5007  476.38
  5010.7  476.88  5031.7  477.29  5044.1  480.66  5077.1  483.41  5083.1  488.46
  5088.6  490.11  5107.5  490.34  5151.9  494.19  5165.2  496.09  5174.9  498.84
  5179.1  499.17  5197.8  508.81  5203.3   508.6  5209.3  510.68  5225.9  512.46
#Mann= 5 ,-1 , 0
  4826.6     .12       0  5005.4     .12       0  5006.7     .07       0
  5010.7     .12       0  5107.5     .12       0
Bank Sta=5006.7,5010.7
XS Rating Curve= 0 ,0
Exp/Cntr=0.3,0.1

Type RM Length L Ch R = 1 ,4010    ,387,387,387
BEGIN DESCRIPTION:
LWE S 027 10.0
END DESCRIPTION:
XS GIS Cut Line= 3
      2412090.02      7043489.97        2412079.        7043260.
      2412056.38       7043116.7
#Sta/Elev= 30
  4770.2  532.41  4772.7  532.41  4780.2  530.65  4790.2   529.8  4800.2  527.02
  4840.2  517.69  4860.3   514.4  4870.1  513.64  4880.3  510.01  4890.3  502.51
  4895.6  497.77  4900.6  494.72  4910.3   491.8  4920.3  484.59  4930.3  482.47
  4940.4  481.24  4950.4  478.68  4960.4  478.04  4980.4  475.61  5027.1  475.36
  5027.4  474.86  5030.9  474.86  5031.1  475.36  5034.2  475.51    5051   481.7
  5061.2   489.9  5064.6  494.02  5071.3  502.13  5111.8  502.97  5145.5  504.57
#Mann= 5 ,-1 , 0
  4770.2     .12       0  4870.1     .07       0  5027.1     .05       0
  5031.1     .07       0  5064.6     .12       0
Bank Sta=5027.1,5031.1
XS Rating Curve= 0 ,0
Exp/Cntr=0.3,0.1

Type RM Length L Ch R = 1 ,3623    ,328,328,328
BEGIN DESCRIPTION:
LWE S 027 9.0
END DESCRIPTION:
XS GIS Cut Line= 3
        2412429.      7043310.02        2412429.        7043160.
      2412426.39      7043035.35
#Sta/Elev= 30
    4850  516.88  4852.5  516.88    4860  514.63    4870  511.46    4880  507.72
  4893.6  503.48    4900  501.49    4910   499.6    4920  498.71    4930  495.15
    4940  485.33    4950   478.7    4960   478.7    4970  476.45    4980  475.39
    4988  475.08  4988.3  474.58  4991.8  474.58    4992  475.08    5010  475.41
    5020  476.64    5030  478.87    5040  484.09    5050  487.38    5070  489.35
    5080  490.84    5090  493.13    5100  494.67    5110  498.19  5124.7  498.86
#Mann= 4 ,-1 , 0
    4850     .12       0  4893.6     .05       0    4988    .033       0
    4992     .05       0
Bank Sta=4988,4992
XS Rating Curve= 0 ,0
Exp/Cntr=0.3,0.1

Type RM Length L Ch R = 1 ,3295    ,53,53,53
BEGIN DESCRIPTION:
Mapping XS 1c4e35cf
END DESCRIPTION:
XS GIS Cut Line= 4
      2412861.65      7043250.43      2412836.54      7043196.99
      2412743.23      7043112.36      2412486.08       7042892.1
#Sta/Elev= 30
  4811.6  502.76  4834.6  501.25  4851.9  497.23  4870.6  496.87  4873.8  494.87
    4888   496.9  4894.8  495.17  4916.4  495.66  4923.2  493.17  4930.6  493.74
  4944.8  490.51    4959  483.23  4965.7  483.17  4973.2  478.62  4979.9  481.12
  4985.4   476.9  4985.6   476.4  4989.4   476.9  4994.1  478.57  5002.3  477.22
  5008.4  483.43  5022.6  480.43  5029.2  484.25  5036.9  484.78  5057.7  492.71
  5100.6  495.81    5207  498.51  5227.9  501.58  5299.2   506.3  5335.2  511.98
#Mann= 3 ,-1 , 0
  4811.6     .05       0  4985.4    .033       0  4989.4     .05       0
Bank Sta=4985.4,4989.4
XS Rating Curve= 0 ,0
Exp/Cntr=0.3,0.1

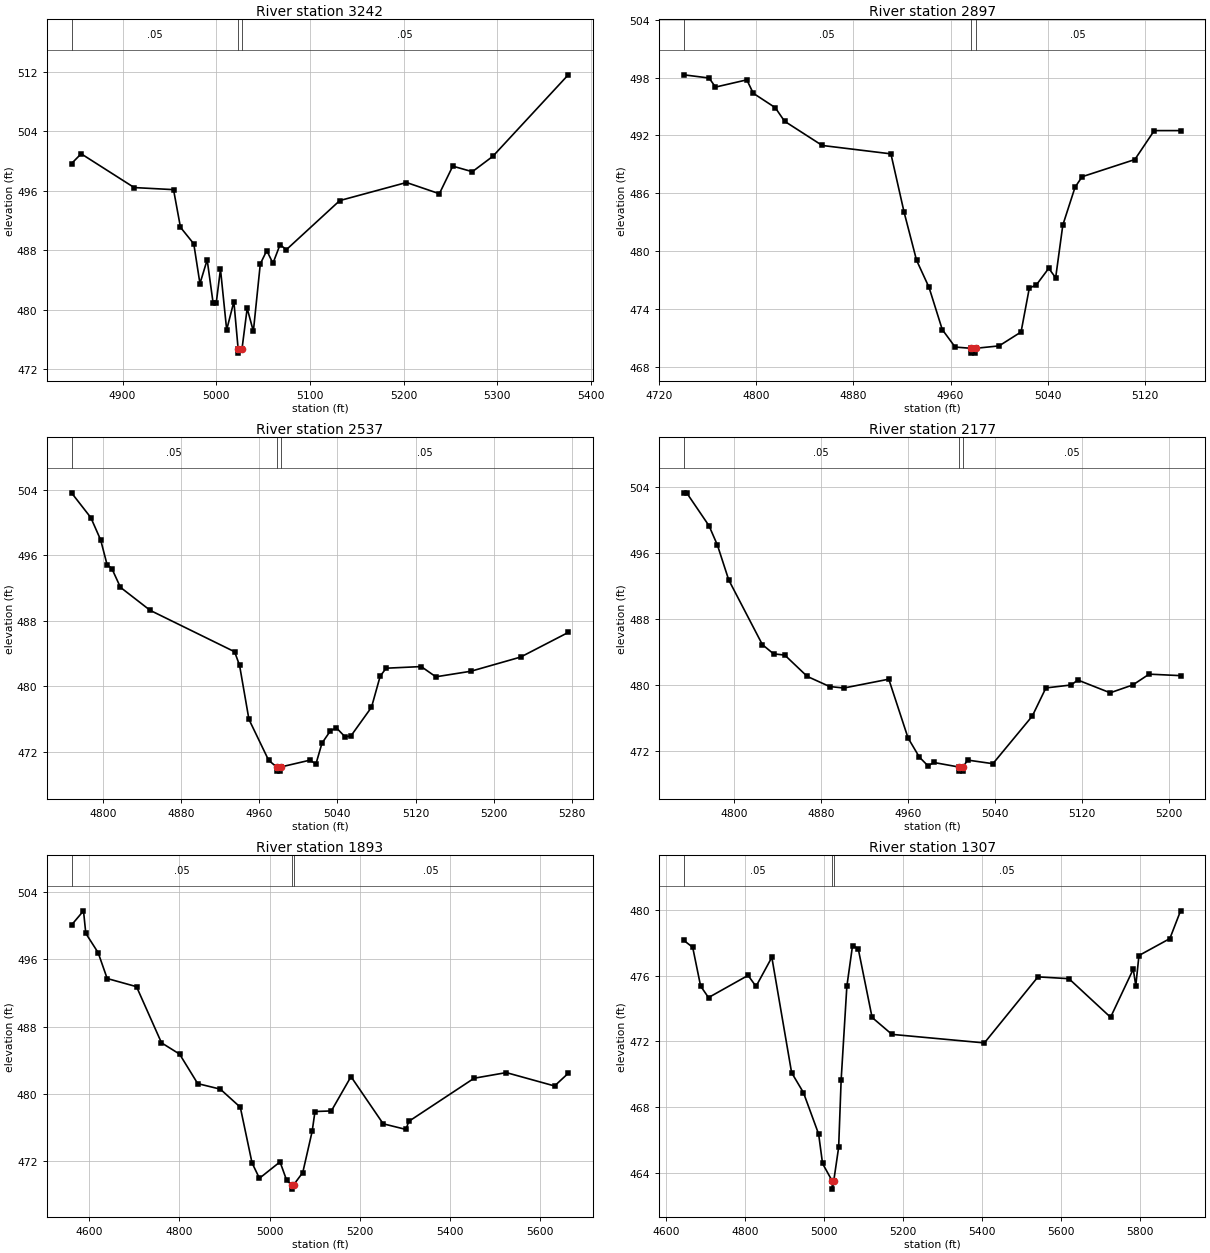
Type RM Length L Ch R = 1 ,3242    ,345,345,345
BEGIN DESCRIPTION:
LWE S 027 8.0
END DESCRIPTION:
XS GIS Cut Line= 4
      2412905.04      7043217.84      2412866.93      7043173.12
      2412794.49       7043110.5      2412510.59      7042864.44
#Sta/Elev= 30
  4845.5  499.63  4855.8  500.95  4912.4  496.41  4954.4  496.13  4961.8  491.07
    4976  488.85  4982.6   483.5  4990.3   486.7  4996.6  480.93    5000  480.93
  5004.5  485.44  5011.1  477.29  5018.8  481.08  5023.4  474.66  5023.6  474.16
  5027.4  474.66    5033  480.18  5039.6  477.09    5047  486.15  5053.9  487.94
  5060.5  486.23  5068.1  488.74  5074.8  488.06  5131.8  494.66    5203  497.09
  5238.1  495.58  5252.4  499.29  5273.3  498.54  5295.1   500.6  5375.7  511.56
#Mann= 3 ,-1 , 0
  4845.5     .05       0  5023.4    .033       0  5027.4     .05       0
Bank Sta=5023.4,5027.4
XS Rating Curve= 0 ,0
Exp/Cntr=0.3,0.1

Type RM Length L Ch R = 1 ,2897    ,360,360,360
BEGIN DESCRIPTION:
LWE S 027 7.0
END DESCRIPTION:
XS GIS Cut Line= 3
      2413162.06      7043211.07      2413076.69      7042965.81
      2413003.82      7042835.27
#Sta/Elev= 30
  4740.3  498.28  4761.1  497.95  4766.4  497.01  4792.2  497.76  4797.5  496.37
  4815.6  494.88  4823.3  493.47  4854.3  490.96  4910.9  490.09  4921.8  484.02
    4932  479.07  4942.3  476.25  4953.2  471.88  4963.8  470.07  4976.7  469.94
    4977  469.44  4980.5  469.44  4980.7  469.94    5000  470.19  5018.1  471.63
  5024.9  476.18  5030.7  476.51  5040.9  478.23  5046.6  477.25  5052.5  482.71
  5062.6  486.64  5068.4  487.72  5111.8   489.5  5127.8   492.5  5149.5   492.5
#Mann= 3 ,-1 , 0
  4740.3     .05       0  4976.7    .033       0  4980.7     .05       0
Bank Sta=4976.7,4980.7
XS Rating Curve= 0 ,0
Exp/Cntr=0.3,0.1

Type RM Length L Ch R = 1 ,2537    ,360,360,360
BEGIN DESCRIPTION:
LWE S 027 6.0
END DESCRIPTION:
XS GIS Cut Line= 3
      2413439.84      7043089.53        2413404.      7042860.01
      2413248.88      7042631.25
#Sta/Elev= 30
  4767.7  503.64  4787.5  500.61  4797.6  497.87  4804.1  494.88  4809.1  494.37
  4817.8   492.1  4848.2  489.29  4934.7  484.23  4939.8  482.57  4949.4  475.97
  4969.6  470.97  4977.8  470.15    4978  469.65  4981.5  469.65  4981.8  470.15
  5011.9  470.99    5018  470.52  5024.2  473.07  5032.9  474.58    5039  474.93
  5047.9  473.83  5053.9  473.96  5074.9  477.45  5083.8  481.25  5089.9  482.22
  5125.8  482.42  5140.8  481.17  5176.7  481.85  5227.6  483.58  5276.4  486.59
#Mann= 3 ,-1 , 0
  4767.7     .05       0  4977.8    .033       0  4981.8     .05       0
Bank Sta=4977.8,4981.8
XS Rating Curve= 0 ,0
Exp/Cntr=0.3,0.1

Type RM Length L Ch R = 1 ,2177    ,284,284,284
BEGIN DESCRIPTION:
LWE S 027 5.0
END DESCRIPTION:
XS GIS Cut Line= 3
      2413779.01      7042960.03      2413719.47      7042721.14
      2413599.56      7042548.25
#Sta/Elev= 30
  4753.8  503.29  4756.4  503.29    4777  499.29  4784.7  496.95  4795.1  492.73
    4826   484.9  4836.3  483.78  4846.6  483.63  4867.2  481.05  4887.8  479.82
  4900.9  479.64  4942.2  480.71  4959.9  473.59  4970.3  471.27  4978.3   470.2
  4983.5  470.62  5006.5  470.07  5006.8  469.57  5010.3  469.57  5010.5  470.07
  5014.6  470.91  5037.9  470.47  5074.1  476.24  5086.6  479.65  5109.9  480.01
  5115.9  480.61  5145.7  479.06  5166.6  480.02  5181.5  481.32  5210.4  481.14
#Mann= 3 ,-1 , 0
  4753.8     .05       0  5006.5    .033       0  5010.5     .05       0
Bank Sta=5006.5,5010.5
XS Rating Curve= 0 ,0
Exp/Cntr=0.3,0.1

Type RM Length L Ch R = 1 ,1893    ,586,586,586
BEGIN DESCRIPTION:
Mapping XS bf8be746
END DESCRIPTION:
XS GIS Cut Line= 3
      2413951.44      7043048.83       2413987.9      7042632.18
      2413430.61      7042236.35
#Sta/Elev= 30
  4560.6  500.07  4587.2  501.76  4592.3  499.08  4619.7  496.78  4639.7  493.71
  4704.8  492.74  4760.2  486.06  4800.3  484.72  4840.5  481.21  4890.7  480.55
    4935   478.4    4961  471.78  4977.4  469.95  5023.1   471.9  5037.9  469.69
  5049.1  469.16  5049.3  468.66  5053.1  469.16  5073.5  470.63  5094.4  475.54
  5100.6  477.89  5136.9  477.96  5180.5  482.04  5251.9  476.43  5302.3  475.76
  5308.7  476.72  5453.6  481.85  5524.9  482.52    5632  480.93  5662.4  482.44
#Mann= 3 ,-1 , 0
  4560.6     .05       0  5049.1    .033       0  5053.1     .05       0
Bank Sta=5049.1,5053.1
XS Rating Curve= 0 ,0
Exp/Cntr=0.3,0.1

Type RM Length L Ch R = 1 ,1307    ,514,514,514
BEGIN DESCRIPTION:
Mapping XS c0382251
END DESCRIPTION:
XS GIS Cut Line= 3
      2414499.33      7042722.48      2414473.29      7042368.73
      2413770.13      7041800.12
#Sta/Elev= 30
  4644.9  478.14  4667.4  477.72  4687.5  475.36  4707.5  474.66  4807.8  476.01
  4827.9  475.34    4868  477.11  4918.1  470.09  4948.2  468.87  4986.6  466.35
  4996.5  464.56  5020.9   463.5  5021.2     463  5024.9   463.5  5037.3  465.54
  5043.7  469.67  5058.1  475.34  5072.5  477.82  5086.9  477.64  5122.1  473.45
  5172.3  472.42  5406.7   471.9  5542.5  475.92  5620.9  475.81  5726.5  473.46
    5784  476.39  5790.4  475.38  5798.4  477.22  5876.7  478.25  5903.9  479.94
#Mann= 3 ,-1 , 0
  4644.9     .05       0  5020.9    .033       0  5024.9     .05       0
Bank Sta=5020.9,5024.9
XS Rating Curve= 0 ,0
Exp/Cntr=0.3,0.1

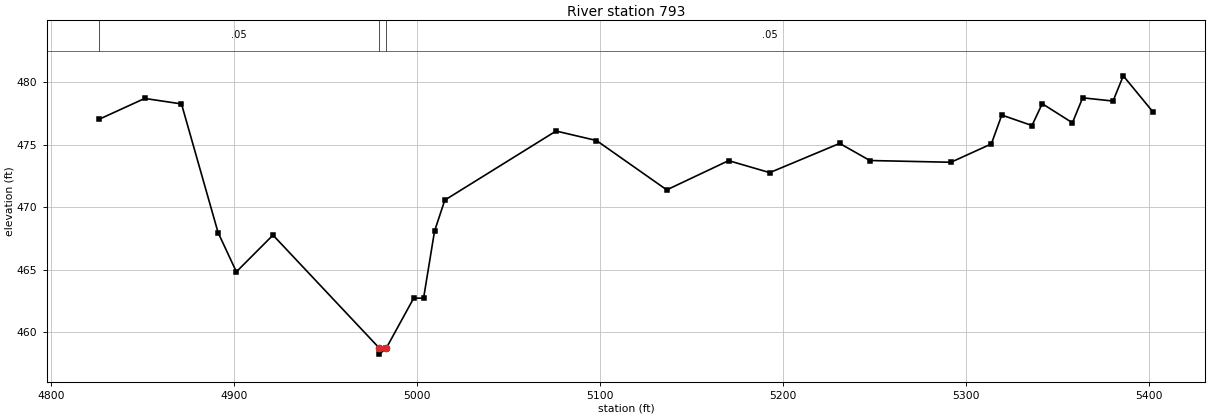
Type RM Length L Ch R = 1 ,793     ,0,0,0
BEGIN DESCRIPTION:
LWE S 027 4.0
END DESCRIPTION:
XS GIS Cut Line= 3
      2414923.16      7042344.84      2414919.45      7042171.08
      2414734.83      7041814.09
#Sta/Elev= 30
  4826.2  477.05    4851  478.71  4871.1  478.27  4891.1  467.97  4901.1  464.83
  4921.1  467.77  4979.1  458.74  4979.3  458.24  4983.1  458.74    4998  462.72
  5003.4  462.72  5009.4  468.09    5015  470.57  5075.8   476.1  5097.9  475.34
  5136.3  471.39  5170.1  473.73  5192.6  472.77  5230.8  475.11  5247.3  473.74
  5291.6   473.6  5313.7  475.07  5319.4  477.38  5335.9  476.54  5341.5  478.29
    5358  476.76  5363.6  478.76  5380.2   478.5  5385.8  480.52  5401.9  477.65
#Mann= 3 ,-1 , 0
  4826.2     .05       0  4979.1    .033       0  4983.1     .05       0
Bank Sta=4979.1,4983.1
XS Rating Curve= 0 ,0
Exp/Cntr=0.3,0.1

Chan Stop Cuts=-1
Use User Specified Reach Order=0
Composite Channel Slope=5