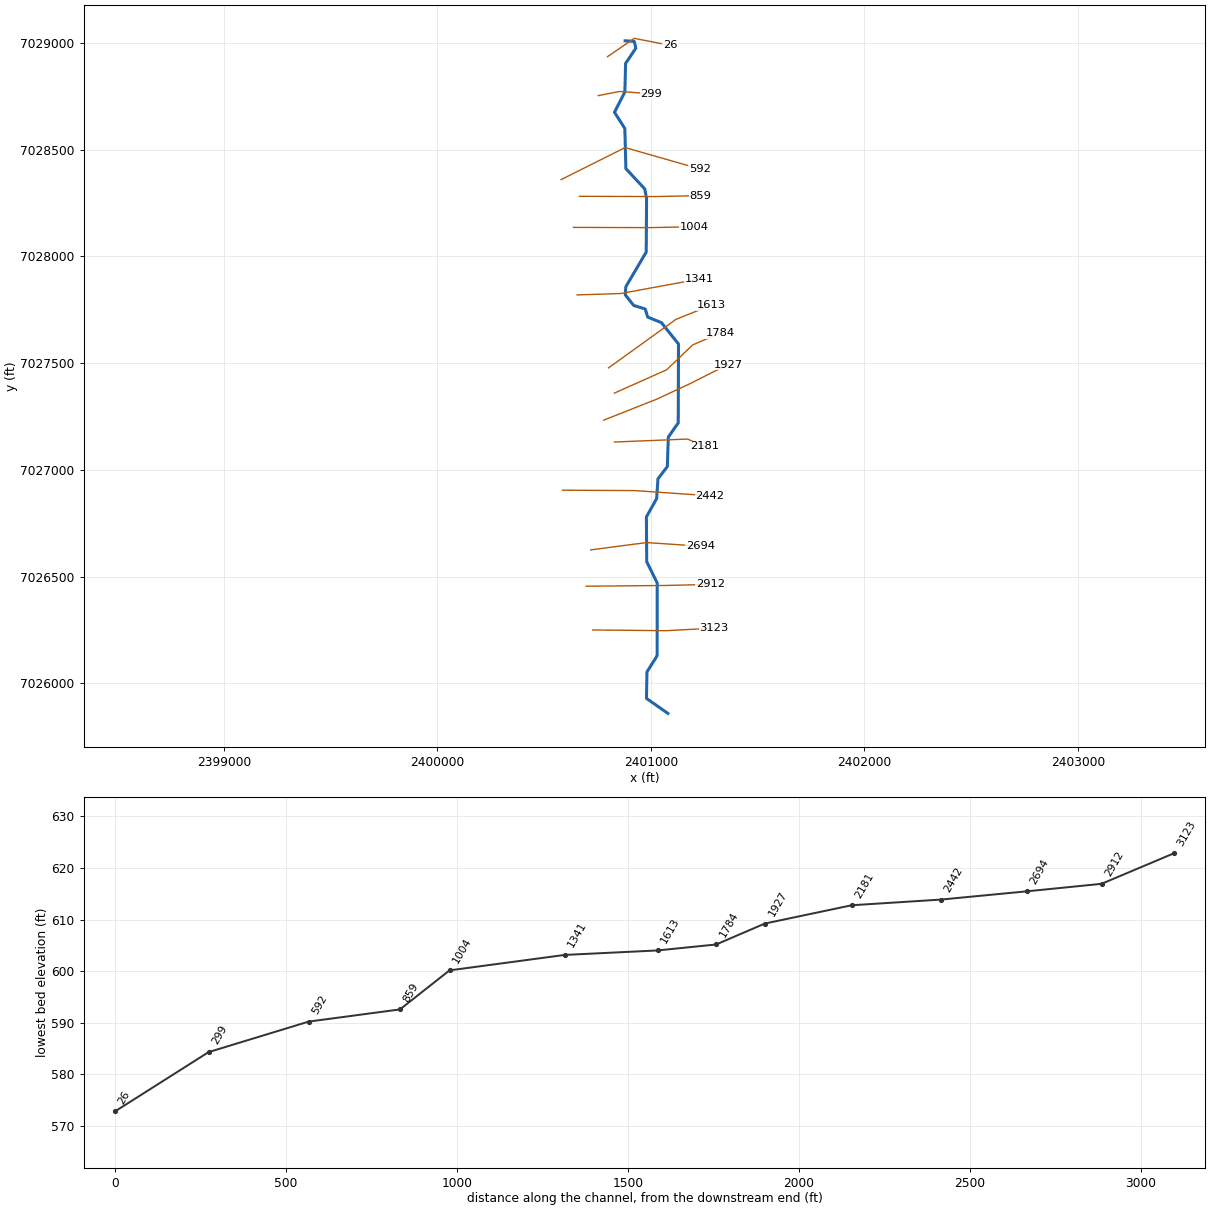
--- LWE S 028.prj (project) ---

Proj Title=LWE S 028 Base Level Engineering
Current Plan=p01
Default Exp/Contr=0.3,0.1
English Units
Geom File=g01
Flow File=f01
Plan File=p01
Y Axis Title=Elevation
X Axis Title(PF)=Main Channel Distance
X Axis Title(XS)=Station
BEGIN DESCRIPTION:
LWE S 028
END DESCRIPTION:
DSS Export Rating Curves= 0
DSS Export Rating Curve Sorted= 0
DSS Export Volume Flow Curves= 0
DXF OffsetX= 0
DXF OffsetY= 0
DXF ScaleX= 1
DXF ScaleY= 10

--- LWE S 028.p01 (plan) ---

Plan Title=Multiple Run
Program Version=4.10
Short Identifier=Multiple
Geom File=g01
Flow File=f01
Subcritical Flow
K Sum by GR= 0
Std Step Tol= 0.01
Critical Tol= 0.01
Num of Std Step Trials= 20
Max Error Tol= 0.3
Flow Tol Ratio= 0.001
Split Flow NTrial= 30
Split Flow Tol= 0.02
Split Flow Ratio= 0.02
Log Output Level= 0
Friction Slope Method= 1
Unsteady Friction Slope Method= 2
Unsteady Bridges Friction Slope Method= 1
Parabolic Critical Depth
Global Vel Dist= 1 , 1 , 1
Global Log Level= 0
CheckData=True
Encroach Param=-1 ,0,0, 0
BEGIN DESCRIPTION:
Multiple Run
END DESCRIPTION:
Computation Interval=1HOUR
Output Interval=1HOUR
Run HTab= 0
Run UNet= 0
Run PostProcess= 0
Run WQNet= 0
UNET Theta= 1
UNET Theta Warmup= 1
UNET ZTol= 0.02
UNET ZSATol= 0.05
UNET MxIter= 20
UNET MaxInSteps= 0
UNET DtIC= 0
UNET DtMin= 0
UNET MaxCRTS= 20
UNET WFStab= 2
UNET SFStab= 1
UNET WFX= 1
UNET SFX= 1
UNET DSS MLevel= 4
UNET DZMax Abort= 100
UNET Convert EG Bridges= 0
UNET Use Existing IB Tables=-1
UNET Froude Reduction=False
UNET Froude Limit= 1
UNET Froude Power= 10
UNET Time Slicing=0,0, 5
UNET Junction Losses=0
Instantaneous Interval=1HOUR
Write IC File= 0
Write IC File at Sim End=0
Echo Input=False
Echo Parameters=False
Echo Output=False
Write Detailed= 0
WQ AD Non Conservative
WQ ULTIMATE=-1
WQ Max Comp Step=1HOUR
WQ Output Interval=15MIN
WQ Output Selected Increments= 0
WQ Output face flow=0
WQ Output face velocity=0
WQ Output face area=0
WQ Output face dispersion=0
WQ Output cell volume=0
WQ Output cell surface area=0
WQ Output cell continuity=0
WQ Output cumulative cell continuity=0
WQ Output face conc=0
WQ Output face dconc_dx=0
WQ Output face courant=0
WQ Output face peclet=0
WQ Output face adv mass=0
WQ Output face disp mass=0
WQ Output cell mass=0
WQ Output cell source sink temp=0
WQ Output cell source sink nsm=0
WQ Output MaxMinRange=-1
WQ Daily Max Min Mean=-1
WQ Daily Range=0
WQ Daily Time=0
WQ Create Restart=0
WQ Fixed Restart=0
WQ System Summary=0
WQ Use Fixed Temperature=0
Sorting and Armoring Iterations= 10
XS Update Threshold= 0.02
Hydraulics Update Threshold= 0.02
Energy Slope Method= 1
Volume Change Method= 0
XS Weighting Method= 0
Number of US Weighted Cross Sections= 1
Number of DS Weighted Cross Sections= 1
Upstream XS Weight=0.25
Main XS Weight=0.5
Downstream XS Weight=0.25
Number of DS XS's Weighted with US Boundary= 1
Upstream Boundary Weight= 1
Weight of XSs Associated with US Boundary= 0
Number of US XS's Weighted with DS Boundary= 1
Downstream Boundary Weight= 0.5
Weight of XSs Associated with DS Boundary= 0.5
Sediment Output Level= 4
Mass or Volume Output= 0
Output Increment Type= 1
Profile and TS Output Increment= 10
XS Output Flag= 0
XS Output Increment= 10
Disregard all LS=0
Disregard all Conn=0
Disregard all Breaches=0
Disregard all Pumps=0

--- LWE S 028.f01 (steady flow) ---

Flow Title=Multiple
Number of Profiles=7
Profile Names=10-year,25-year,50-year,1pct_min,100-year,1pct_plu,500-year
River Rch & RM= LWE S 028,Reach-1,3123
     380     504     603     359     715    1427    1006
Boundary for River Rch & Prof#=LWE S 028,Reach-1,1
Up Type=0
Dn Type=3
Dn Slope=0.005
Boundary for River Rch & Prof#=LWE S 028,Reach-1,2
Up Type=0
Dn Type=3
Dn Slope=0.005
Boundary for River Rch & Prof#=LWE S 028,Reach-1,3
Up Type=0
Dn Type=3
Dn Slope=0.005
Boundary for River Rch & Prof#=LWE S 028,Reach-1,4
Up Type=0
Dn Type=3
Dn Slope=0.005
Boundary for River Rch & Prof#=LWE S 028,Reach-1,5
Up Type=0
Dn Type=3
Dn Slope=0.005
Boundary for River Rch & Prof#=LWE S 028,Reach-1,6
Up Type=0
Dn Type=3
Dn Slope=0.005
Boundary for River Rch & Prof#=LWE S 028,Reach-1,7
Up Type=0
Dn Type=3
Dn Slope=0.005

--- LWE S 028.g01 (geometry) ---

Geom Title=Existing Conditions
Program Version=4.10

River Reach=LWE S 028       ,Reach-1
Reach XY= 30
        2401079.        7025860.      2400978.99      7025930.14
      2400981.25      7026054.05      2401028.93      7026130.03
      2401029.45      7026470.19      2400980.22       7026570.5
      2400978.64      7026780.15      2401026.64      7026865.98
      2401032.86       7026958.4      2401076.73      7027015.94
      2401081.27      7027154.06      2401127.78       7027220.5
      2401129.04      7027590.02      2401048.97      7027690.18
      2400984.77      7027715.98      2400973.19        7027754.
      2400919.13      7027770.72      2400879.55      7027820.48
       2400882.3      7027858.24       2400977.8       7028020.5
       2400979.5      7028270.21      2400971.17      7028316.19
      2400882.55      7028411.47      2400877.76       7028599.5
      2400829.09      7028675.39      2400877.75       7028770.5
      2400881.27      7028904.09      2400929.14      7028975.55
      2400921.76      7029007.39        2400879.        7029010.

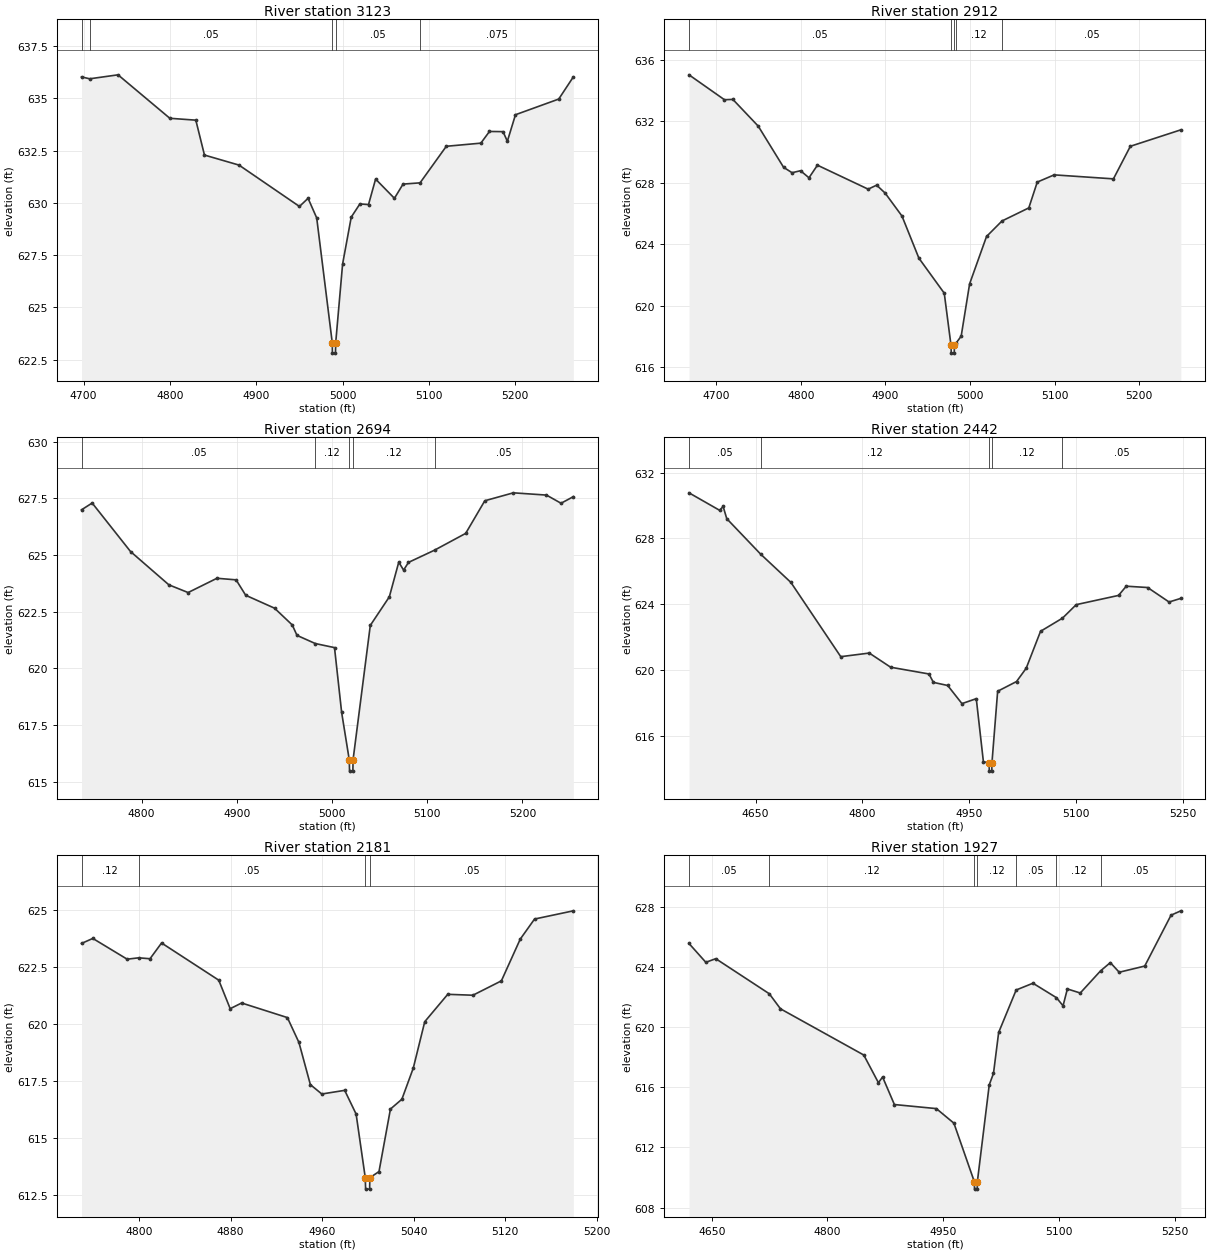
Type RM Length L Ch R = 1 ,3123    ,211,211,211
BEGIN DESCRIPTION:
LWE S 028 11.0
END DESCRIPTION:
XS GIS Cut Line= 3
      2400726.66      7026250.73      2401070.38      7026247.26
      2401295.92      7026259.31
#Sta/Elev= 30
  4697.6  636.03  4707.1  635.94  4739.9  636.13  4799.9  634.05    4830  633.96
    4840  632.29    4880  631.81    4950  629.83    4960  630.22    4970  629.28
    4988  623.31  4988.2  622.81  4991.7  622.81    4992  623.31    5000  627.08
    5010  629.32    5020  629.95    5030  629.92  5038.2  631.14    5060  630.22
    5070   630.9  5089.7  630.96  5120.1  632.71  5160.1  632.86  5170.1  633.42
  5185.8  633.41  5190.8  632.95  5200.2  634.22  5250.3  634.97  5267.2  636.03
#Mann= 5 ,-1 , 0
  4697.6    .075       0  4707.1     .05       0    4988     .05       0
    4992     .05       0  5089.7    .075       0
Bank Sta=4988,4992
XS Rating Curve= 0 ,0
Exp/Cntr=0.3,0.1

Type RM Length L Ch R = 1 ,2912    ,218,218,218
BEGIN DESCRIPTION:
LWE S 028 10.0
END DESCRIPTION:
XS GIS Cut Line= 3
       2400697.1      7026455.59      2401070.38      7026459.07
      2401278.72      7026464.27
#Sta/Elev= 30
  4667.7  635.03  4709.6  633.41  4719.6  633.43  4749.6  631.69  4779.6  629.01
  4789.6  628.66  4799.6  628.79  4809.6  628.33  4819.6  629.15  4879.6  627.59
  4889.6  627.85  4899.6  627.34  4919.6  625.84  4939.6   623.1  4969.6  620.82
  4977.6  617.42  4977.9  616.92  4981.4  616.92  4981.6  617.42  4983.4  617.56
  4989.6  618.02  4999.6  621.43  5019.6  624.51  5037.9  625.52  5069.6  626.37
  5079.6  628.05  5099.6  628.52  5169.7  628.26  5189.7  630.38  5249.4  631.45
#Mann= 5 ,-1 , 0
  4667.7     .05       0  4977.6     .07       0  4981.6     .05       0
  4983.4     .12       0  5037.9     .05       0
Bank Sta=4977.6,4981.6
XS Rating Curve= 0 ,0
Exp/Cntr=0.3,0.1

Type RM Length L Ch R = 1 ,2694    ,252,252,252
BEGIN DESCRIPTION:
LWE S 028 9.0
END DESCRIPTION:
XS GIS Cut Line= 3
      2400717.94      7026625.73        2400979.        7026660.
      2401231.84      7026643.09
#Sta/Elev= 30
  4736.8     627    4748   627.3  4788.3  625.16  4828.6  623.69  4848.8  623.35
  4879.1  623.98  4899.2  623.91  4909.3  623.23  4939.6  622.66  4958.2  621.92
  4963.2  621.46  4982.4   621.1  5002.6  620.92  5010.1  618.06  5018.1  615.97
  5018.4  615.47  5021.9  615.47  5022.1  615.97  5040.2   621.9  5060.2  623.16
  5070.1  624.69  5075.2  624.34  5080.3  624.68  5107.7  625.22  5140.4  625.96
  5160.5   627.4  5190.5  627.75  5225.3  627.65  5240.6  627.29  5253.5  627.58
#Mann= 5 ,-1 , 0
  4736.8     .05       0  4982.4     .12       0  5018.1     .07       0
  5022.1     .12       0  5107.7     .05       0
Bank Sta=5018.1,5022.1
XS Rating Curve= 0 ,0
Exp/Cntr=0.3,0.1

Type RM Length L Ch R = 1 ,2442    ,261,261,261
BEGIN DESCRIPTION:
LWE S 028 8.0
END DESCRIPTION:
XS GIS Cut Line= 3
      2400585.99      7026905.25      2400922.81      7026903.51
      2401275.46      7026879.31
#Sta/Elev= 30
  4556.6  630.77  4599.5  629.71  4604.5  629.94  4609.6   629.2  4657.3  627.04
  4699.6  625.33  4769.6  620.82  4809.6  621.04  4839.6  620.18  4893.4  619.77
  4899.6  619.26  4919.7  619.07  4939.7  617.97  4959.8  618.27  4969.8  614.44
  4977.8  614.37  4978.1  613.87  4981.6  613.87  4981.8  614.37  4989.8  618.72
  5016.3  619.31  5029.9  620.12    5050  622.36  5080.8  623.16  5100.1  623.98
  5159.5  624.54  5170.3   625.1  5200.3  625.02  5230.4  624.14  5246.9  624.36
#Mann= 5 ,-1 , 0
  4556.6     .05       0  4657.3     .12       0  4977.8     .07       0
  4981.8     .12       0  5080.8     .05       0
Bank Sta=4977.8,4981.8
XS Rating Curve= 0 ,0
Exp/Cntr=0.3,0.1

Type RM Length L Ch R = 1 ,2181    ,254,254,254
BEGIN DESCRIPTION:
LWE S 028 7.0
END DESCRIPTION:
XS GIS Cut Line= 3
       2400829.1      7027130.94      2401171.07      7027144.83
      2401251.61      7027109.98
#Sta/Elev= 30
  4749.7  623.54  4759.6  623.76  4789.6  622.85  4799.7  622.91  4809.6  622.87
  4819.7  623.56  4869.7  621.93  4879.7  620.68  4889.7  620.93  4929.7  620.29
  4939.8   619.2  4949.8  617.35  4959.8  616.94  4979.8   617.1  4989.8  616.06
  4997.8  613.27  4998.1  612.77  5001.6  612.77  5001.8  613.27  5009.8  613.54
  5019.8  616.28  5029.8  616.71  5039.8  618.08  5049.8  620.11  5069.9  621.31
  5091.9  621.27  5116.8   621.9  5133.3  623.73  5145.8  624.61  5179.7  624.97
#Mann= 4 ,-1 , 0
  4749.7     .12       0  4799.7     .05       0  4997.8     .05       0
  5001.8     .05       0
Bank Sta=4997.8,5001.8
XS Rating Curve= 0 ,0
Exp/Cntr=0.3,0.1

Type RM Length L Ch R = 1 ,1927    ,143,143,143
BEGIN DESCRIPTION:
LWE S 028 6.2
END DESCRIPTION:
XS GIS Cut Line= 4
      2400778.75      7027233.39      2401028.71      7027332.33
      2401181.49      7027403.51      2401360.31      7027493.79
#Sta/Elev= 30
  4620.5  625.55  4642.3   624.3  4655.2  624.54  4724.6  622.21  4739.1  621.21
  4847.1  618.14  4866.1   616.3  4871.5  616.68  4886.8  614.85  4941.2  614.58
    4964  613.61  4990.4  609.73  4990.7  609.23  4994.2  609.23  4994.4  609.73
  5009.8  616.16  5015.3  616.92    5022  619.64  5044.7  622.46  5066.5  622.91
  5096.9  621.95  5105.5  621.41  5111.1  622.53  5127.8  622.26  5154.1  623.73
  5166.8  624.28  5178.3  623.64  5211.4  624.05  5245.5  627.43  5258.2  627.72
#Mann= 7 ,-1 , 0
  4620.5     .05       0  4724.6     .12       0  4990.4     .07       0
  4994.4     .12       0  5044.7     .05       0  5096.9     .12       0
  5154.1     .05       0
Bank Sta=4990.4,4994.4
XS Rating Curve= 0 ,0
Exp/Cntr=0.3,0.1

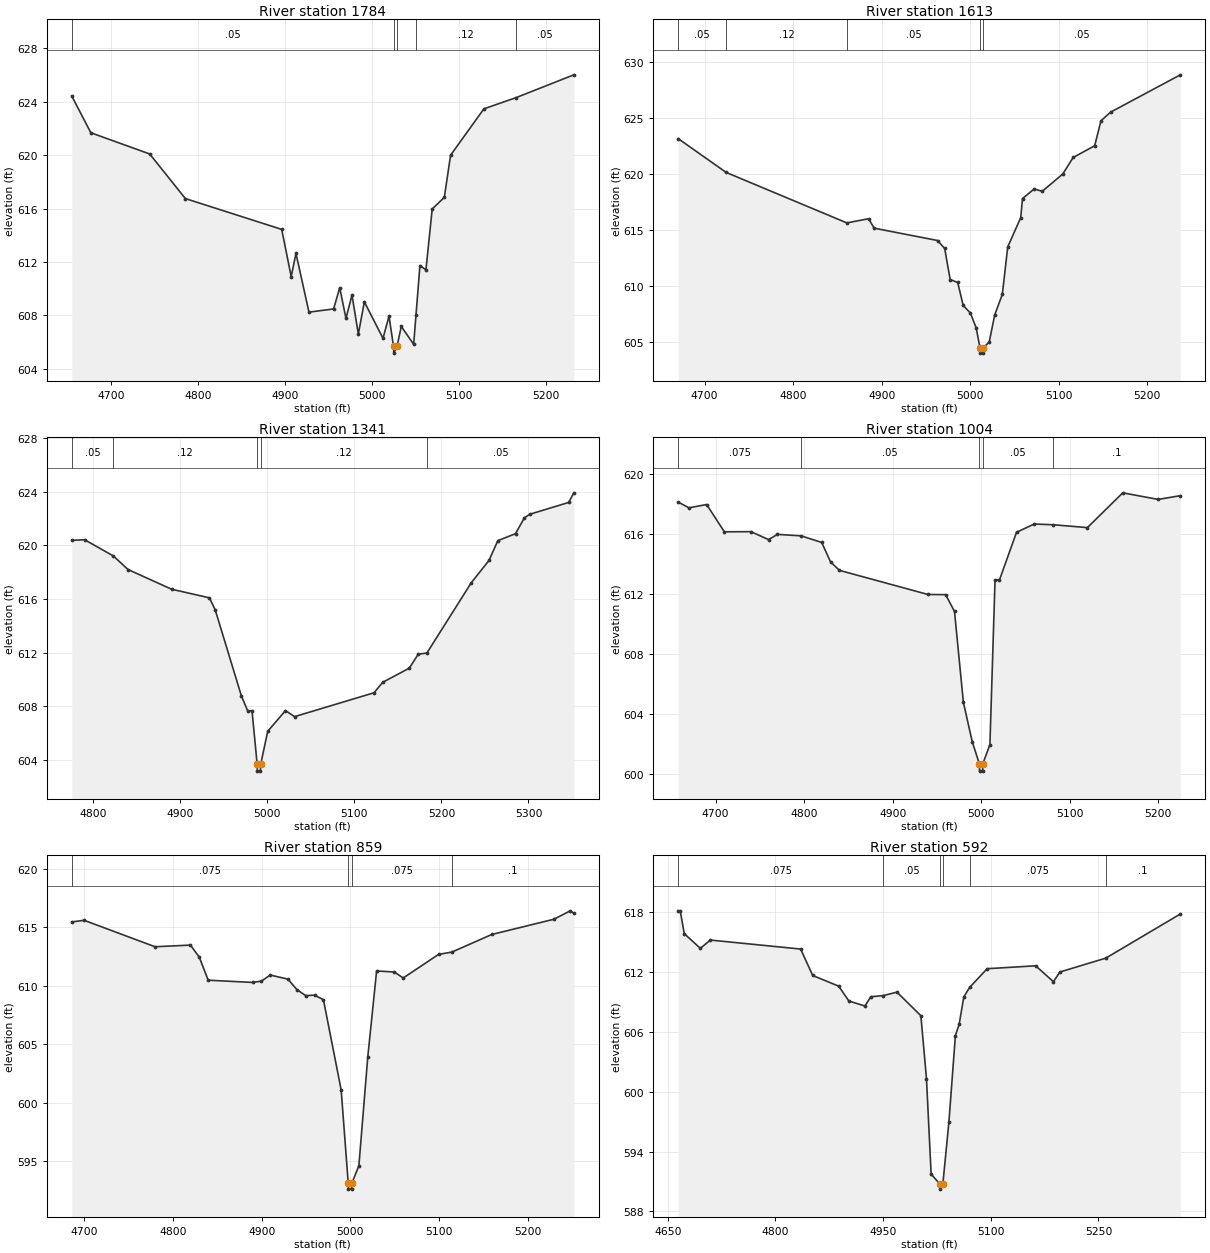
Type RM Length L Ch R = 1 ,1784    ,171,171,171
BEGIN DESCRIPTION:
LWE S 028 6.0
END DESCRIPTION:
XS GIS Cut Line= 4
      2400828.97      7027359.98      2401073.85      7027469.48
      2401195.38       7027585.8      2401323.81      7027641.34
#Sta/Elev= 30
  4655.2  624.43  4677.1  621.68  4744.7  620.09  4785.6  616.75  4896.2  614.44
  4907.1  610.91  4912.6  612.64  4927.5  608.24  4955.8  608.48  4962.8  610.07
    4970  607.77  4976.9  609.52  4984.2   606.6  4991.1  609.01  5012.5  606.28
  5019.4  607.94  5024.6  605.67  5024.9  605.17  5028.6  605.67  5033.5  607.17
  5047.7  605.83  5050.4  608.04  5054.9  611.73  5061.8  611.41    5069  615.97
  5082.9  616.84  5090.1     620  5128.3  623.47  5165.6  624.32  5231.6  626.02
#Mann= 5 ,-1 , 0
  4655.2     .05       0  5024.6    .033       0  5028.6     .05       0
  5050.4     .12       0  5165.6     .05       0
Bank Sta=5024.6,5028.6
XS Rating Curve= 0 ,0
Exp/Cntr=0.3,0.1

Type RM Length L Ch R = 1 ,1613    ,272,272,272
BEGIN DESCRIPTION:
LWE S 028 5.0
END DESCRIPTION:
XS GIS Cut Line= 3
      2400801.25      7027478.14      2401117.25      7027705.59
       2401282.2      7027771.57
#Sta/Elev= 30
  4670.3  623.14  4724.4  620.13  4860.7  615.63  4885.3     616  4891.5  615.16
  4963.2  614.06  4971.2  613.35  4977.4  610.58  4985.9  610.32  4992.1  608.27
  5000.2   607.6  5006.8  606.27    5011  604.52  5011.2  604.02  5014.7  604.02
    5015  604.52  5021.5  605.01  5027.7  607.42  5036.3  609.26  5042.4  613.49
  5057.1   616.1  5059.1   617.8  5072.3  618.66  5081.3  618.44  5104.6  619.99
  5116.3  621.46  5140.6  622.51  5147.7  624.73  5158.5   625.5  5237.3  628.83
#Mann= 5 ,-1 , 0
  4670.3     .05       0  4724.4     .12       0  4860.7     .05       0
    5011    .033       0    5015     .05       0
Bank Sta=5011,5015
XS Rating Curve= 0 ,0
Exp/Cntr=0.3,0.1

Type RM Length L Ch R = 1 ,1341    ,337,337,337
BEGIN DESCRIPTION:
LWE S 028 4.0
END DESCRIPTION:
XS GIS Cut Line= 3
       2400654.3      7027820.01      2400858.55      7027826.53
      2401224.88      7027893.73
#Sta/Elev= 30
  4775.3  620.38    4790  620.43    4823  619.22    4840   618.2  4890.1  616.73
  4933.4  616.09  4940.1  615.19  4970.1  608.78  4977.4  607.65  4982.4  607.65
  4988.3  603.65  4988.5  603.15    4992  603.15  4992.3  603.65  5000.4  606.12
  5020.8  607.67  5031.3  607.22  5122.5     609  5132.5  609.78  5163.1  610.84
  5173.3  611.88  5183.3  611.97  5234.3  617.22  5254.6  618.88  5264.8  620.36
  5285.1  620.88  5295.3  622.07    5302  622.34  5346.1  623.21  5352.1  623.93
#Mann= 5 ,-1 , 0
  4775.3     .05       0    4823     .12       0  4988.3     .07       0
  4992.3     .12       0  5183.3     .05       0
Bank Sta=4988.3,4992.3
XS Rating Curve= 0 ,0
Exp/Cntr=0.3,0.1

Type RM Length L Ch R = 1 ,1004    ,145,145,145
BEGIN DESCRIPTION:
LWE S 028 3.3
END DESCRIPTION:
XS GIS Cut Line= 3
      2400636.86      7028136.18      2400995.45       7028135.1
      2401204.01      7028139.44
#Sta/Elev= 30
  4657.8   618.1  4669.9  617.72  4689.9  617.94  4709.9  616.12  4739.9  616.13
  4759.9   615.6  4769.9  615.95  4796.7  615.85  4819.9  615.41  4829.9  614.11
  4839.9  613.55  4939.9  611.94  4959.9  611.93  4969.9  610.81  4979.9  604.76
  4989.9  602.13  4997.9  600.66  4998.2  600.16  5001.7  600.16  5001.9  600.66
  5009.9  601.92  5015.7  612.91  5020.7  612.91    5040  616.09    5060  616.64
  5081.7  616.59    5120   616.4    5160  618.72    5200  618.28    5225  618.53
#Mann= 5 ,-1 , 0
  4657.8    .075       0  4796.7     .05       0  4997.9     .05       0
  5001.9     .05       0  5081.7      .1       0
Bank Sta=4997.9,5001.9
XS Rating Curve= 0 ,0
Exp/Cntr=0.3,0.1

Type RM Length L Ch R = 1 ,859     ,267,267,267
BEGIN DESCRIPTION:
LWE S 028 3.0
END DESCRIPTION:
XS GIS Cut Line= 3
      2400665.11      7028281.77       2401023.7      7028280.69
      2401231.47      7028285.02
#Sta/Elev= 30
  4685.7  615.44  4699.6  615.58  4779.6  613.32  4819.6  613.46  4829.6  612.42
  4839.6  610.46  4889.6  610.27  4899.6  610.38  4909.6   610.9  4929.6  610.55
  4939.6  609.66  4949.6  609.14  4959.6  609.18  4969.6  608.79  4989.6  601.09
  4997.6   593.1  4997.8   592.6  5001.3   592.6  5001.6   593.1  5009.6   594.6
  5019.6  603.87  5029.6  611.25  5049.6  611.16  5059.6  610.65  5099.6  612.67
  5114.4  612.86  5159.6  614.37  5229.6  615.67    5248  616.39  5252.1  616.18
#Mann= 4 ,-1 , 0
  4685.7    .075       0  4997.6     .07       0  5001.6    .075       0
  5114.4      .1       0
Bank Sta=4997.6,5001.6
XS Rating Curve= 0 ,0
Exp/Cntr=0.3,0.1

Type RM Length L Ch R = 1 ,592     ,293,293,293
BEGIN DESCRIPTION:
LWE S 028 2.0
END DESCRIPTION:
XS GIS Cut Line= 3
      2400578.99        7028360.        2400879.        7028510.
      2401228.98      7028410.01
#Sta/Elev= 30
  4664.6  618.13  4667.4  618.13    4673  615.84  4695.4  614.37  4709.3   615.2
  4835.1   614.3  4851.9  611.65  4888.2  610.58  4902.2   609.1  4924.6  608.59
  4932.9  609.52  4950.4  609.64  4969.3  609.98  5002.6  607.62  5010.4  601.32
  5016.9  591.74  5029.2  590.74  5029.5  590.24  5033.2  590.74  5041.6  596.92
  5050.7  605.63  5055.9  606.75  5062.4   609.5  5070.6  610.46  5094.9  612.33
  5162.5  612.62  5187.2  611.03  5196.3     612  5260.2  613.39    5364  617.81
#Mann= 6 ,-1 , 0
  4664.6    .075       0  4950.4     .05       0  5029.2    .033       0
  5033.2     .05       0  5070.6    .075       0  5260.2      .1       0
Bank Sta=5029.2,5033.2
XS Rating Curve= 0 ,0
Exp/Cntr=0.3,0.1

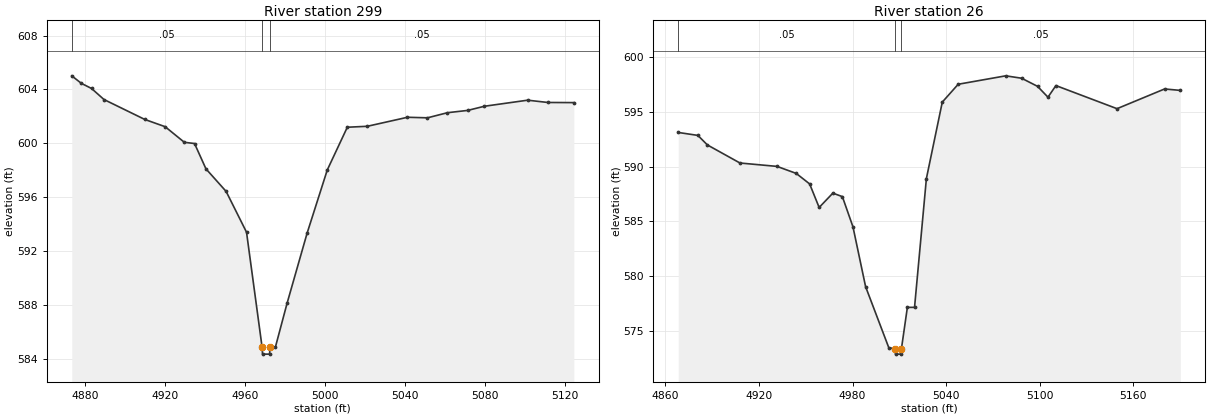
Type RM Length L Ch R = 1 ,299     ,273,273,273
BEGIN DESCRIPTION:
LWE S 028 1.0
END DESCRIPTION:
XS GIS Cut Line= 3
      2400753.19      7028753.32      2400853.12      7028772.87
        2401002.        7028762.
#Sta/Elev= 29
  4873.4  605.01  4878.2  604.45  4883.3  604.07  4889.5  603.25  4909.9  601.77
  4920.1  601.23  4929.7  600.07  4934.8  599.98  4940.5   598.1  4950.6  596.42
  4960.8  593.39  4968.6  584.83  4968.8  584.33  4972.3  584.33  4972.6  584.83
  4975.2  584.83  4981.1  588.12  4991.1  593.32  5001.2  598.02  5011.2  601.19
  5021.2  601.26  5041.3  601.93  5051.3  601.89  5061.3  602.27  5071.4  602.44
  5079.8  602.75  5101.4   603.2  5111.5  603.03  5124.5  603.02
#Mann= 3 ,-1 , 0
  4873.4     .05       0  4968.6    .033       0  4972.6     .05       0
Bank Sta=4968.6,4972.6
XS Rating Curve= 0 ,0
Exp/Cntr=0.3,0.1

Type RM Length L Ch R = 1 ,26      ,0,0,0
BEGIN DESCRIPTION:
LWE S 028 0.3
END DESCRIPTION:
XS GIS Cut Line= 3
      2400796.58      7028935.82      2400921.57      7029021.68
      2401088.88      7028989.08
#Sta/Elev= 30
  4868.2  593.12  4880.8  592.85  4886.9  591.98  4907.8  590.33  4931.6  590.02
  4943.9  589.38  4952.5  588.42  4958.6  586.27  4967.4  587.58  4973.5  587.26
  4980.3   584.5  4988.4  579.04  5003.3  573.46  5007.4  573.38  5007.6  572.88
  5011.1  572.88  5011.4  573.38  5015.2  577.15  5019.8  577.15  5027.4  588.91
  5037.6  595.89  5047.8  597.52  5078.3  598.29  5088.5  598.07  5098.7  597.33
  5105.4  596.34  5110.5   597.4  5149.7  595.29  5180.2  597.09  5190.3  596.96
#Mann= 3 ,-1 , 0
  4868.2     .05       0  5007.4    .033       0  5011.4     .05       0
Bank Sta=5007.4,5011.4
XS Rating Curve= 0 ,0
Exp/Cntr=0.3,0.1

Chan Stop Cuts=-1
Use User Specified Reach Order=0
Composite Channel Slope=5