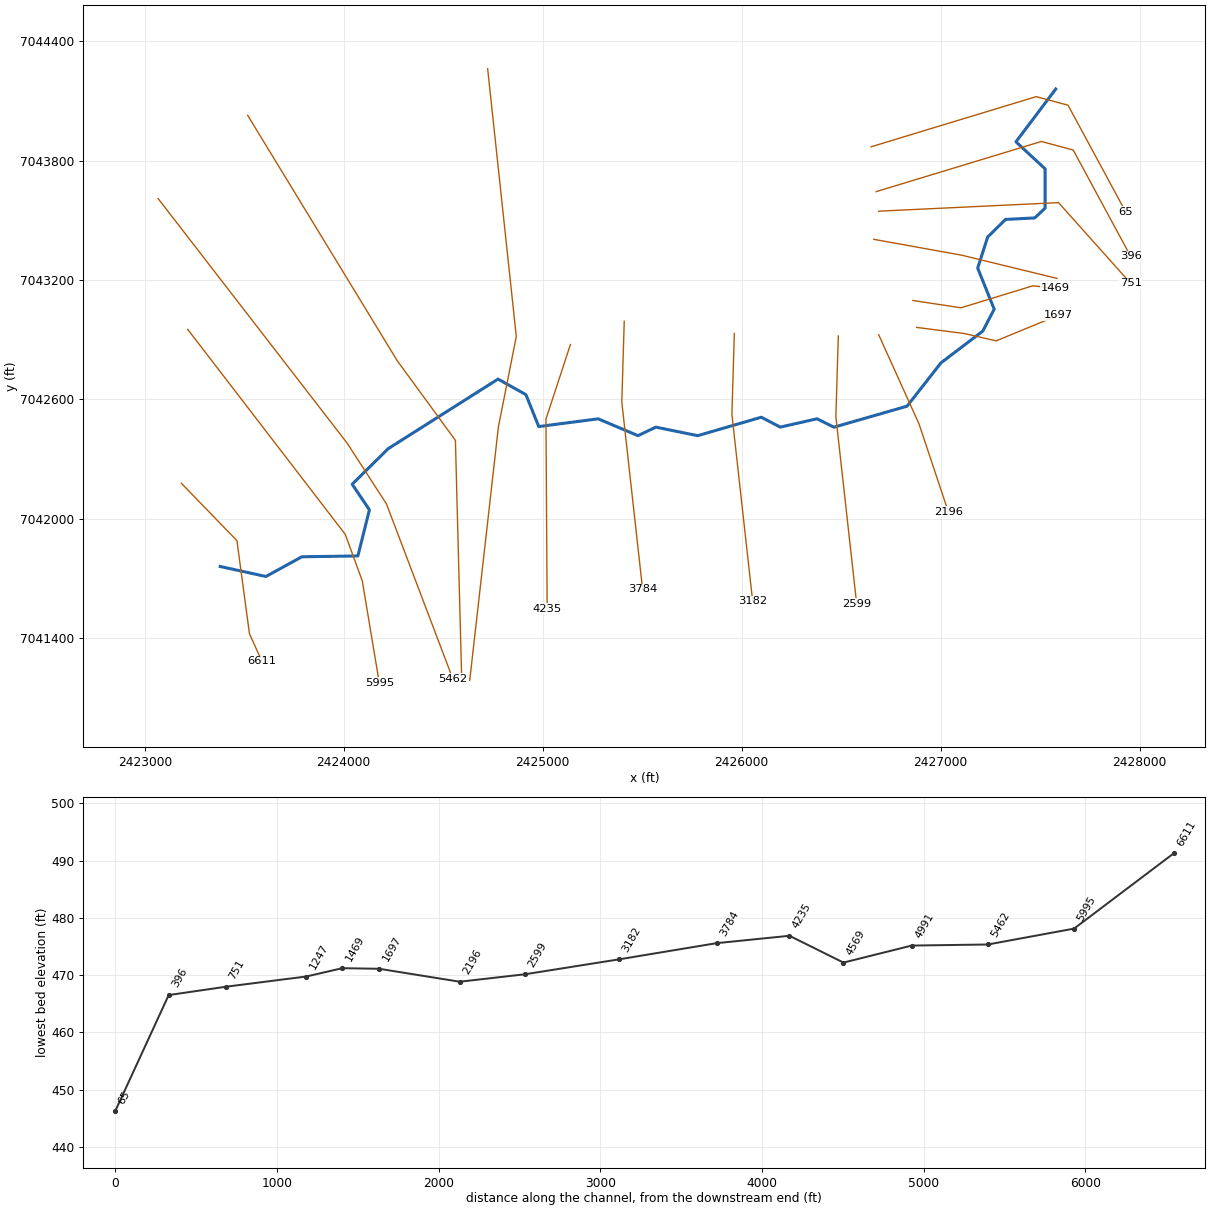
--- LWE S 034.prj (project) ---

Proj Title=LWE S 034 Base Level Engineering
Current Plan=p01
Default Exp/Contr=0.3,0.1
English Units
Geom File=g01
Flow File=f01
Flow File=f02
Flow File=f03
Plan File=p01
Plan File=p02
Plan File=p03
Y Axis Title=Elevation
X Axis Title(PF)=Main Channel Distance
X Axis Title(XS)=Station
BEGIN DESCRIPTION:
LWE S 034
END DESCRIPTION:
DSS Export Rating Curves= 0
DSS Export Rating Curve Sorted= 0
DSS Export Volume Flow Curves= 0
DXF OffsetX= 0
DXF OffsetY= 0
DXF ScaleX= 1
DXF ScaleY= 10

--- LWE S 034.p01 (plan) ---

Plan Title=Multiple Run
Program Version=4.10
Short Identifier=Multiple
Geom File=g01
Flow File=f01
Subcritical Flow
K Sum by GR= 0
Std Step Tol= 0.01
Critical Tol= 0.01
Num of Std Step Trials= 20
Max Error Tol= 0.3
Flow Tol Ratio= 0.001
Split Flow NTrial= 30
Split Flow Tol= 0.02
Split Flow Ratio= 0.02
Log Output Level= 0
Friction Slope Method= 1
Unsteady Friction Slope Method= 2
Unsteady Bridges Friction Slope Method= 1
Parabolic Critical Depth
Global Vel Dist= 1 , 1 , 1
Global Log Level= 0
CheckData=True
Encroach Param=-1 ,0,0, 0
BEGIN DESCRIPTION:
Multiple Run
END DESCRIPTION:
Computation Interval=1HOUR
Output Interval=1HOUR
Run HTab= 0
Run UNet= 0
Run PostProcess= 0
Run WQNet= 0
UNET Theta= 1
UNET Theta Warmup= 1
UNET ZTol= 0.02
UNET ZSATol= 0.05
UNET MxIter= 20
UNET MaxInSteps= 0
UNET DtIC= 0
UNET DtMin= 0
UNET MaxCRTS= 20
UNET WFStab= 2
UNET SFStab= 1
UNET WFX= 1
UNET SFX= 1
UNET DSS MLevel= 4
UNET DZMax Abort= 100
UNET Convert EG Bridges= 0
UNET Use Existing IB Tables=-1
UNET Froude Reduction=False
UNET Froude Limit= 1
UNET Froude Power= 10
UNET Time Slicing=0,0, 5
UNET Junction Losses=0
Instantaneous Interval=1HOUR
Write IC File= 0
Write IC File at Sim End=0
Echo Input=False
Echo Parameters=False
Echo Output=False
Write Detailed= 0
WQ AD Non Conservative
WQ ULTIMATE=-1
WQ Max Comp Step=1HOUR
WQ Output Interval=15MIN
WQ Output Selected Increments= 0
WQ Output face flow=0
WQ Output face velocity=0
WQ Output face area=0
WQ Output face dispersion=0
WQ Output cell volume=0
WQ Output cell surface area=0
WQ Output cell continuity=0
WQ Output cumulative cell continuity=0
WQ Output face conc=0
WQ Output face dconc_dx=0
WQ Output face courant=0
WQ Output face peclet=0
WQ Output face adv mass=0
WQ Output face disp mass=0
WQ Output cell mass=0
WQ Output cell source sink temp=0
WQ Output cell source sink nsm=0
WQ Output MaxMinRange=-1
WQ Daily Max Min Mean=-1
WQ Daily Range=0
WQ Daily Time=0
WQ Create Restart=0
WQ Fixed Restart=0
WQ System Summary=0
WQ Use Fixed Temperature=0
Sorting and Armoring Iterations= 10
XS Update Threshold= 0.02
Hydraulics Update Threshold= 0.02
Energy Slope Method= 1
Volume Change Method= 0
XS Weighting Method= 0
Number of US Weighted Cross Sections= 1
Number of DS Weighted Cross Sections= 1
Upstream XS Weight=0.25
Main XS Weight=0.5
Downstream XS Weight=0.25
Number of DS XS's Weighted with US Boundary= 1
Upstream Boundary Weight= 1
Weight of XSs Associated with US Boundary= 0
Number of US XS's Weighted with DS Boundary= 1
Downstream Boundary Weight= 0.5
Weight of XSs Associated with DS Boundary= 0.5
Sediment Output Level= 4
Mass or Volume Output= 0
Output Increment Type= 1
Profile and TS Output Increment= 10
XS Output Flag= 0
XS Output Increment= 10
Disregard all LS=0
Disregard all Conn=0
Disregard all Breaches=0
Disregard all Pumps=0

--- LWE S 034.p02 (plan) ---

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Plan Title=Floodway Run
Short Identifier=Floodway
Geom File=g01
Flow File=f02
Global Vel Dist=  1 , 1 , 1
Encroach Param= -1, 0, 0, 0
Floodway Run

--- LWE S 034.p03 (plan) ---

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Plan Title=100-Year Single
Short Identifier=100Year
Geom File=g01
Flow File=f03
Global Vel Dist=  1 , 1 , 1
Encroach Param= -1, 0, 0, 0
100Year Run

--- LWE S 034.f01 (steady flow) ---

Flow Title=Multiple
Program Version=4.10
Number of Profiles= 7
Profile Names=10-year,25-year,50-year,1pct_minus,100-year,1pct_plus,500-year
River Rch & RM=LWE S 034,Reach-1         ,6611
     498     665     798     475     947    1890    1334
River Rch & RM=LWE S 034,Reach-1         ,4235
     602     811     980     586    1170    2334    1666
Boundary for River Rch & Prof#=LWE S 034,Reach-1         , 1
Up Type= 0
Dn Type= 3
Dn Slope=0.06
Boundary for River Rch & Prof#=LWE S 034,Reach-1         , 2
Up Type= 0
Dn Type= 3
Dn Slope=0.06
Boundary for River Rch & Prof#=LWE S 034,Reach-1         , 3
Up Type= 0
Dn Type= 3
Dn Slope=0.06
Boundary for River Rch & Prof#=LWE S 034,Reach-1         , 4
Up Type= 0
Dn Type= 3
Dn Slope=0.06
Boundary for River Rch & Prof#=LWE S 034,Reach-1         , 5
Up Type= 0
Dn Type= 3
Dn Slope=0.06
Boundary for River Rch & Prof#=LWE S 034,Reach-1         , 6
Up Type= 0
Dn Type= 3
Dn Slope=0.06
Boundary for River Rch & Prof#=LWE S 034,Reach-1         , 7
Up Type= 0
Dn Type= 3
Dn Slope=0.06
DSS Import GetInterval= 0
DSS Import GetPeak= 0
DSS Import FillOption= 0

--- LWE S 034.f02 (steady flow) ---

Flow Title=Floodway
Number of Profiles=2
Profile Names=1pct_minus,100-year
River Rch & RM= LWE S 034,Reach-1,6611
     475     947
River Rch & RM= LWE S 034,Reach-1,4235
     586    1170
Boundary for River Rch & Prof#=LWE S 034,Reach-1,1
Up Type=0
Dn Type=3
Dn Slope=0.005
Boundary for River Rch & Prof#=LWE S 034,Reach-1,2
Up Type=0
Dn Type=3
Dn Slope=0.005

--- LWE S 034.f03 (steady flow) ---

Flow Title=100-year Single
Number of Profiles=1
Profile Names=1pct_minus
River Rch & RM= LWE S 034,Reach-1,6611
     475
River Rch & RM= LWE S 034,Reach-1,4235
     586
Boundary for River Rch & Prof#=LWE S 034,Reach-1,1
Up Type=0
Dn Type=3
Dn Slope=0.005

--- LWE S 034.g01 (geometry) ---

Geom Title=Existing Conditions
Program Version=4.10

River Reach=LWE S 034       ,Reach-1
Reach XY= 30
        2423379.        7041760.      2423608.83       7041709.7
       2423789.5       7041808.8      2424071.09      7041812.91
      2424129.04      7042044.66      2424042.41      7042173.34
      2424222.95      7042351.84      2424775.69      7042701.98
      2424915.74      7042623.66      2424980.25      7042463.36
       2425278.9      7042502.21        2425479.      7042417.56
       2425568.8      7042460.41        2425779.      7042417.56
      2426099.18      7042510.28      2426194.22      7042460.52
      2426379.01      7042502.41      2426463.58      7042460.15
      2426831.55      7042565.73      2427002.18       7042783.7
      2427212.37      7042943.33      2427269.59      7043053.38
      2427186.56        7043260.      2427236.85      7043416.19
      2427326.54      7043504.54      2427473.35      7043511.98
      2427525.57      7043561.22      2427525.55      7043758.75
      2427378.99      7043894.55        2427579.        7044160.

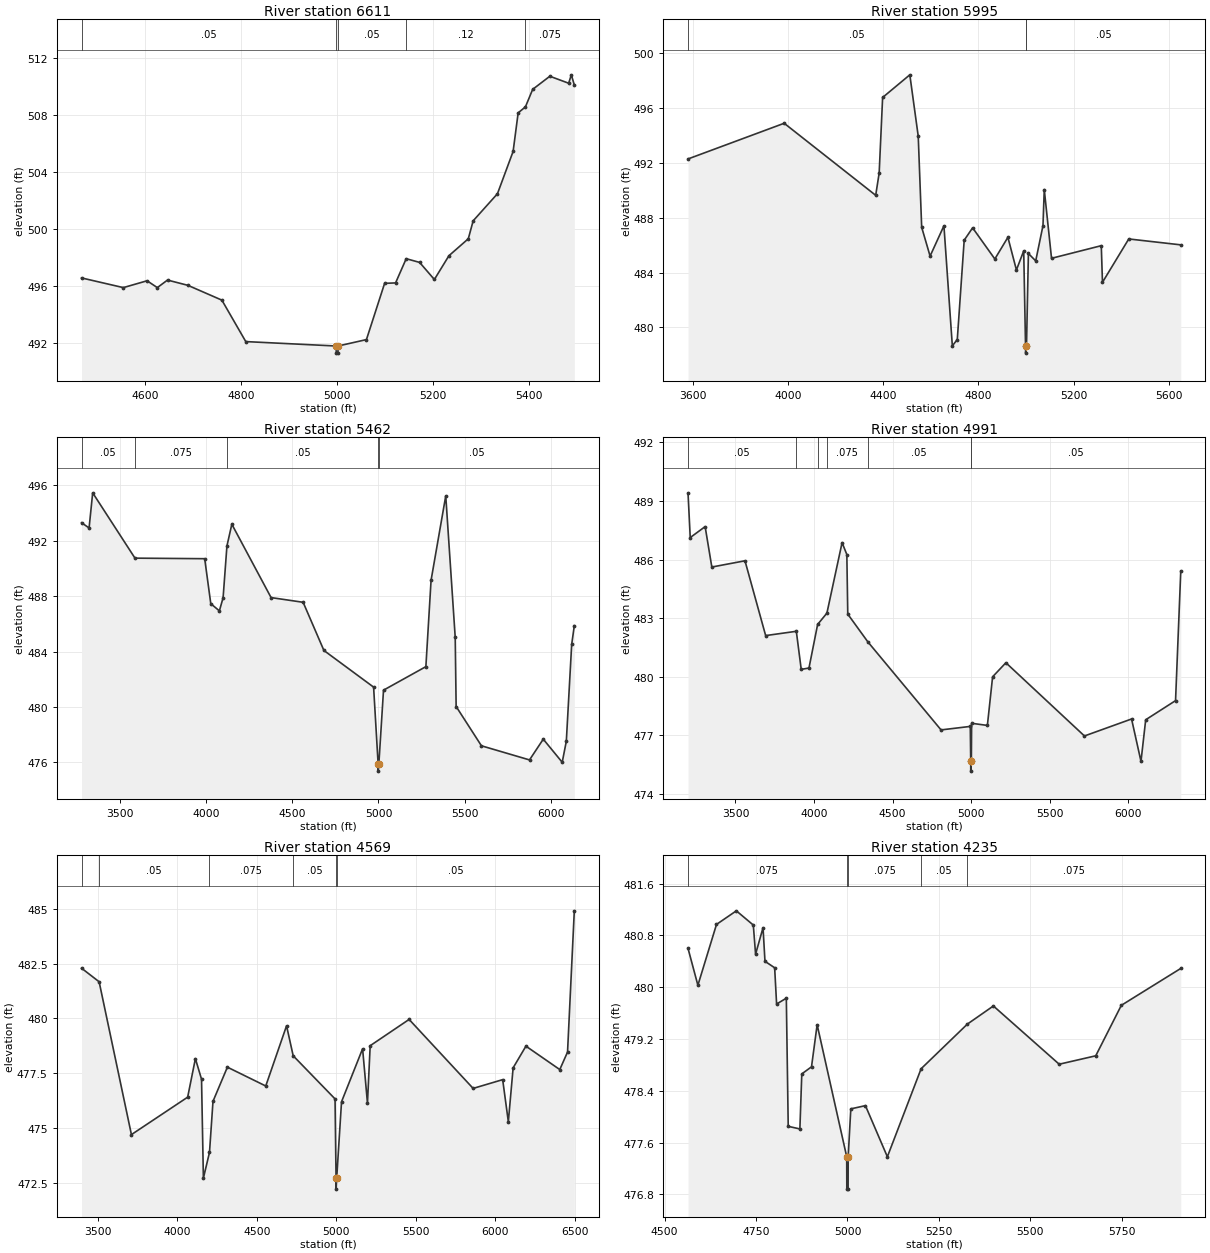
Type RM Length L Ch R = 1 ,6611    ,616,616,616
BEGIN DESCRIPTION:
LWE S 034 14.0
END DESCRIPTION:
XS GIS Cut Line= 4
      2423184.01      7042177.91      2423463.09      7041889.83
       2423526.1      7041421.73      2423588.49      7041283.58
#Sta/Elev= 30
  4468.4  496.54  4555.3  495.86  4604.7  496.34    4626  495.86  4647.2  496.39
  4689.6  496.02  4760.3  494.98    4810  492.07    4998  491.76  4998.3  491.26
  5001.8  491.26    5002  491.76    5061  492.21  5098.8  496.16  5121.6  496.19
  5143.7  497.89  5171.6  497.63  5202.3  496.43  5232.6   498.1  5272.9  499.29
    5283  500.55  5333.5  502.45  5366.1  505.42  5376.6  508.13  5391.7  508.55
  5406.8  509.78  5442.5   510.7  5481.7  510.21  5487.2   510.8  5493.4  510.09
#Mann= 5 ,-1 , 0
  4468.4     .05       0    4998     .04       0    5002     .05       0
  5143.7     .12       0  5391.7    .075       0
Bank Sta=4998,5002
XS Rating Curve= 0 ,0
Exp/Cntr=0.3,0.1

Type RM Length L Ch R = 1 ,5995    ,533,533,533
BEGIN DESCRIPTION:
LWE S 034 13.0
END DESCRIPTION:
XS GIS Cut Line= 4
      2423215.52      7042952.08      2424007.71      7041921.34
      2424093.23      7041687.29      2424178.68      7041174.54
#Sta/Elev= 30
  3580.8  492.28  3984.6  494.88  4368.8  489.63  4383.4  491.25  4397.9  496.76
  4512.1  498.41  4547.4  493.94  4561.9   487.3  4597.2   485.2  4655.3  487.41
  4690.6  478.66  4711.4  479.12  4740.4  486.36  4775.8  487.26  4869.1  484.99
  4923.9  486.57  4959.7  484.19  4990.3  485.58    4998  478.63  4998.3  478.13
    5002  478.63    5010  485.39  5040.7  484.85  5071.2  487.42  5076.6  490.05
  5107.1  485.04    5316  485.96    5321  483.29  5431.4  486.45  5649.8  486.02
#Mann= 3 ,-1 , 0
  3580.8     .05       0    4998     .04       0    5002     .05       0
Bank Sta=4998,5002
XS Rating Curve= 0 ,0
Exp/Cntr=0.3,0.1

Type RM Length L Ch R = 1 ,5462    ,471,471,471
BEGIN DESCRIPTION:
LWE S 034 12.0
END DESCRIPTION:
XS GIS Cut Line= 4
      2423067.01       7043609.2      2424016.71      7042380.44
      2424214.75      7042074.37      2424547.82      7041196.69
#Sta/Elev= 30
  3278.8  493.31  3322.5  492.93  3343.3  495.47  3588.5  490.75  3992.6  490.71
  4027.9  487.46  4077.7  486.94  4099.3  487.89  4121.5  491.63  4149.9   493.2
  4377.4   487.9  4563.2  487.56  4683.6  484.08  4971.7  481.43    4998  475.86
  4998.3  475.36    5002  475.86  5029.1  481.21  5274.7  482.91  5304.8  489.15
  5389.9  495.25  5444.8  485.02  5450.1  480.03  5596.8  477.19  5875.4  476.17
  5955.1  477.67    6065     476  6088.8  477.52  6119.9  484.52  6135.1  485.87
#Mann= 5 ,-1 , 0
  3278.8     .05       0  3588.5    .075       0  4121.5     .05       0
    4998     .04       0    5002     .05       0
Bank Sta=4998,5002
XS Rating Curve= 0 ,0
Exp/Cntr=0.3,0.1

Type RM Length L Ch R = 1 ,4991    ,422,422,422
BEGIN DESCRIPTION:
LWE S 034 11.0
END DESCRIPTION:
XS GIS Cut Line= 4
       2423517.1       7044027.8      2424268.76      7042794.52
      2424561.33      7042393.94      2424592.83      7041196.69
#Sta/Elev= 30
  3197.7  489.42  3211.8  487.13  3306.7  487.69  3349.3  485.62  3560.4  485.94
  3692.1  482.11  3887.4  482.33  3918.6  480.38    3968  480.45    4023  482.68
  4082.2  483.26  4178.8  486.87  4209.1  486.26    4215  483.21  4342.8  481.79
  4809.1  477.28  4995.2  477.46    4998  475.67  4998.3  475.17    5002  475.67
  5003.7  477.62  5104.1  477.51  5137.4     480    5222  480.72  5722.2  476.97
  6022.3  477.84  6082.3  475.67  6112.3   477.8  6302.4  478.78  6335.7  485.42
#Mann= 7 ,-1 , 0
  3197.7     .05       0  3887.4    .075       0    4023      .1       0
  4082.2    .075       0  4342.8     .05       0    4998     .04       0
    5002     .05       0
Bank Sta=4998,5002
XS Rating Curve= 0 ,0
Exp/Cntr=0.3,0.1

Type RM Length L Ch R = 1 ,4569    ,334,334,334
BEGIN DESCRIPTION:
LWE S 034 10.0
END DESCRIPTION:
XS GIS Cut Line= 4
      2424723.36      7044261.86      2424867.39      7042916.05
      2424777.37      7042461.45      2424633.34      7041187.69
#Sta/Elev= 30
  3397.5  482.29    3508  481.67  3711.1  474.69  4064.8   476.4  4113.4  478.16
    4152  477.22  4163.7   472.7  4202.1  473.88  4224.1  476.21  4314.6  477.77
  4555.9  476.91  4686.7  479.66  4728.4  478.29  4991.6  476.32    4998   472.7
  4998.3   472.2    5002   472.7  5032.4  476.19  5164.9  478.61  5195.5  476.13
  5212.6  478.75  5457.4  479.95    5860   476.8  6045.8   477.2  6081.4  475.28
  6111.6  477.74  6192.1  478.73  6404.9  477.66  6453.7  478.46  6496.3  484.91
#Mann= 6 ,-1 , 0
  3397.5    .075       0    3508     .05       0  4202.1    .075       0
  4728.4     .05       0    4998     .04       0    5002     .05       0
Bank Sta=4998,5002
XS Rating Curve= 0 ,0
Exp/Cntr=0.3,0.1

Type RM Length L Ch R = 1 ,4235    ,451,451,451
BEGIN DESCRIPTION:
LWE S 034 9.0
END DESCRIPTION:
XS GIS Cut Line= 3
      2425139.37      7042875.64      2425016.38      7042500.54
      2425022.53      7041547.41
#Sta/Elev= 30
  4563.9   480.6  4590.9  480.03  4641.8  480.97  4696.1  481.18  4742.5  480.96
  4748.7  480.51  4769.1  480.92  4774.4   480.4  4800.9   480.3  4806.2  479.74
  4832.8  479.83    4838  477.85  4869.9  477.81  4875.1  478.66  4901.7  478.77
  4917.1  479.42    4998  477.38  4998.3  476.88  5001.8  476.88    5002  477.38
  5009.2  478.12  5049.2  478.17  5109.2  477.38  5201.5  478.74  5328.1  479.43
  5399.2  479.71  5579.2  478.81  5679.2  478.94  5749.2  479.72  5911.8  480.29
#Mann= 5 ,-1 , 0
  4563.9    .075       0    4998     .07       0    5002    .075       0
  5201.5     .05       0  5328.1    .075       0
Bank Sta=4998,5002
XS Rating Curve= 0 ,0
Exp/Cntr=0.3,0.1

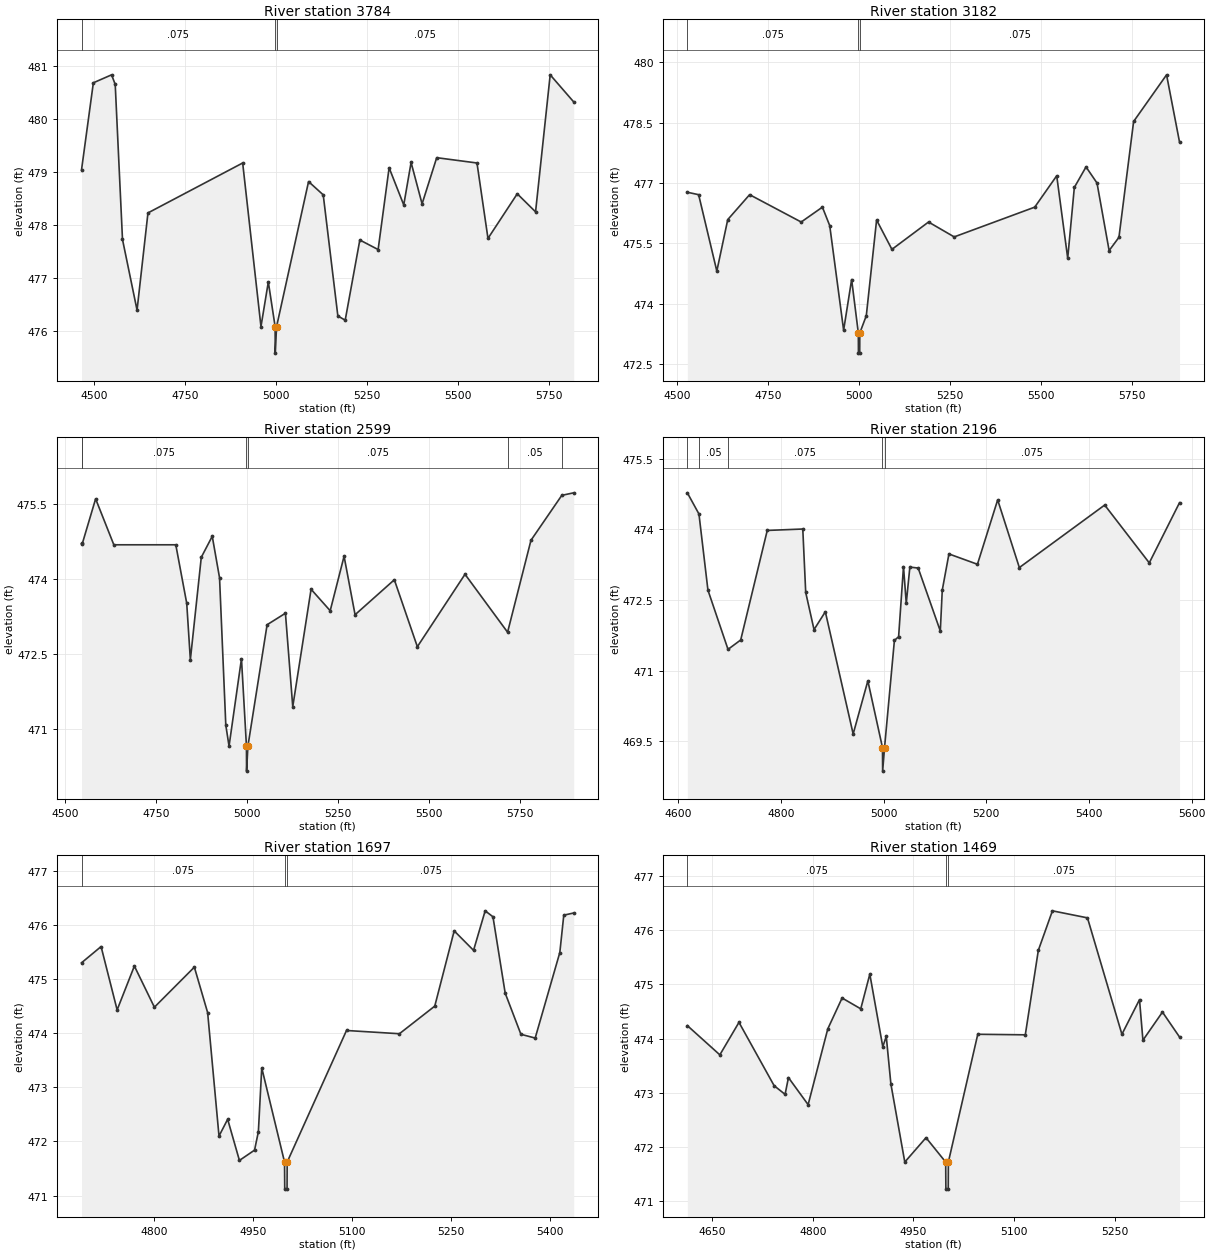
Type RM Length L Ch R = 1 ,3784    ,602,602,602
BEGIN DESCRIPTION:
LWE S 034 8.0
END DESCRIPTION:
XS GIS Cut Line= 3
      2425409.94      7042992.52      2425397.64      7042586.63
      2425502.17       7041645.8
#Sta/Elev= 30
  4465.9  479.04  4498.4  480.68  4548.5  480.83  4558.5  480.65  4578.5  477.73
  4618.5   476.4  4648.5  478.23  4908.8  479.17  4959.1  476.09  4979.3  476.93
    4998  476.09  4998.3  475.59    5002  476.09  5089.9  478.82  5130.2  478.57
  5170.4  476.29  5190.6  476.21  5230.8  477.72  5281.1  477.54  5311.3  479.08
  5351.5  478.38  5371.7  479.18  5401.9   478.4  5442.1  479.27  5552.8  479.17
    5583  477.75  5663.5  478.59  5713.8  478.25    5754  480.83  5818.6  480.32
#Mann= 3 ,-1 , 0
  4465.9    .075       0    4998     .07       0    5002    .075       0
Bank Sta=4998,5002
XS Rating Curve= 0 ,0
Exp/Cntr=0.3,0.1

Type RM Length L Ch R = 1 ,3182    ,583,583,583
BEGIN DESCRIPTION:
LWE S 034 7.0
END DESCRIPTION:
XS GIS Cut Line= 3
      2425963.37      7042930.98      2425951.07      7042525.13
      2426055.57      7041584.65
#Sta/Elev= 30
  4528.2  476.77  4559.2  476.71  4609.2  474.81  4639.2  476.09  4699.3  476.71
    4841  476.03  4899.3   476.4  4919.4  475.94  4957.6  473.34  4979.6   474.6
    4998  473.27  4998.3  472.77  5001.8  472.77    5002  473.27  5019.9   473.7
  5048.2  476.08  5090.3  475.35  5190.9  476.03  5261.4  475.66  5482.7   476.4
  5543.1  477.18  5573.3  475.13  5591.5  476.89  5623.6   477.4  5653.8     477
  5687.1  475.32  5714.1  475.65  5754.4  478.53  5844.9  479.69  5880.5  478.02
#Mann= 3 ,-1 , 0
  4528.2    .075       0    4998     .07       0    5002    .075       0
Bank Sta=4998,5002
XS Rating Curve= 0 ,0
Exp/Cntr=0.3,0.1

Type RM Length L Ch R = 1 ,2599    ,403,403,403
BEGIN DESCRIPTION:
LWE S 034 6.0
END DESCRIPTION:
XS GIS Cut Line= 3
      2426486.06      7042918.69      2426473.76      7042512.83
      2426578.14      7041573.45
#Sta/Elev= 30
  4545.2  474.71  4547.6  474.72  4583.9  475.61  4633.9  474.69    4804  474.69
    4834  473.52    4844  472.39    4874  474.44  4904.1  474.86  4924.1  474.03
  4941.3  471.08  4950.2  470.66  4984.3  472.41    4998  470.66  4998.3  470.16
    5002  470.66  5054.7  473.09    5105  473.32  5125.1  471.45  5175.4   473.8
  5227.9  473.37    5266  474.46  5296.2  473.29    5404  473.99  5467.2  472.65
    5598   474.1  5714.9  472.94  5779.1  474.78  5863.8  475.68  5896.4  475.73
#Mann= 6 ,-1 , 0
  4545.2     .05       0  4547.6    .075       0    4998     .07       0
    5002    .075       0  5714.9     .05       0  5863.8    .075       0
Bank Sta=4998,5002
XS Rating Curve= 0 ,0
Exp/Cntr=0.3,0.1

Type RM Length L Ch R = 1 ,2196    ,499,499,499
BEGIN DESCRIPTION:
LWE S 034 5.0
END DESCRIPTION:
XS GIS Cut Line= 3
      2426688.99      7042924.84      2426891.92      7042475.94
       2427039.2      7042034.08
#Sta/Elev= 30
    4618  474.78  4640.6  474.33  4658.1  472.71  4697.2  471.45  4721.9  471.65
  4773.6  473.98  4842.8  474.01  4848.5  472.66  4864.7  471.87  4886.7  472.25
  4940.9  469.65  4969.5  470.78    4998  469.36  4998.3  468.86    5002  469.36
  5021.2  471.64  5029.4  471.72  5038.9  473.21  5044.3  472.43  5051.3   473.2
  5067.5  473.18  5110.6  471.84  5114.4  472.71  5127.4  473.48  5182.9  473.26
  5222.3  474.63  5264.5  473.19  5430.7  474.52  5517.5  473.29  5576.4  474.57
#Mann= 5 ,-1 , 0
    4618    .075       0  4640.6     .05       0  4697.2    .075       0
    4998     .07       0    5002    .075       0
Bank Sta=4998,5002
XS Rating Curve= 0 ,0
Exp/Cntr=0.3,0.1

Type RM Length L Ch R = 1 ,1697    ,228,228,228
BEGIN DESCRIPTION:
LWE S 034 4.3
END DESCRIPTION:
XS GIS Cut Line= 4
      2426879.62      7042961.73      2427119.44      7042930.99
      2427279.32      7042894.09      2427592.91      7043023.22
#Sta/Elev= 30
  4690.7   475.3  4720.3   475.6  4744.6  474.43  4770.7  475.24    4801  474.48
  4861.5  475.22  4881.6  474.38  4898.8   472.1  4911.9  472.41  4929.7  471.65
  4952.6  471.84  4958.4  472.18  4963.5  473.36    4998  471.62  4998.3  471.12
  5001.8  471.12    5002  471.62  5091.8  474.05  5171.9  473.99  5225.4   474.5
  5254.8  475.89  5284.1  475.53  5301.7  476.26  5313.5  476.15    5332  474.74
  5355.8  473.98  5377.4  473.91  5414.7  475.49  5420.7  476.18  5435.7  476.22
#Mann= 3 ,-1 , 0
  4690.7    .075       0    4998     .07       0    5002    .075       0
Bank Sta=4998,5002
XS Rating Curve= 0 ,0
Exp/Cntr=0.3,0.1

Type RM Length L Ch R = 1 ,1469    ,222,222,222
BEGIN DESCRIPTION:
LWE S 034 4.0
END DESCRIPTION:
XS GIS Cut Line= 4
      2426861.13      7043097.02      2427102.82       7043060.3
       2427463.8      7043170.81      2427574.24      7043158.54
#Sta/Elev= 30
  4613.2  474.24  4661.6   473.7  4690.1   474.3  4742.5  473.13  4758.8  472.97
  4763.8  473.28  4793.1  472.78  4822.4  474.18  4843.7  474.75  4871.5  474.55
    4885  475.19  4904.3  473.85  4909.5  474.04  4916.4  473.16  4937.1  471.72
  4968.7  472.17    4998  471.72  4998.3  471.22  5001.8  471.22    5002  471.72
  5045.8  474.08  5116.6  474.07    5136  475.63    5157  476.36  5209.2  476.23
  5260.5  474.08  5286.7  474.72  5291.8  473.97  5320.9  474.49  5346.3  474.03
#Mann= 3 ,-1 , 0
  4613.2    .075       0    4998     .07       0    5002    .075       0
Bank Sta=4998,5002
XS Rating Curve= 0 ,0
Exp/Cntr=0.3,0.1

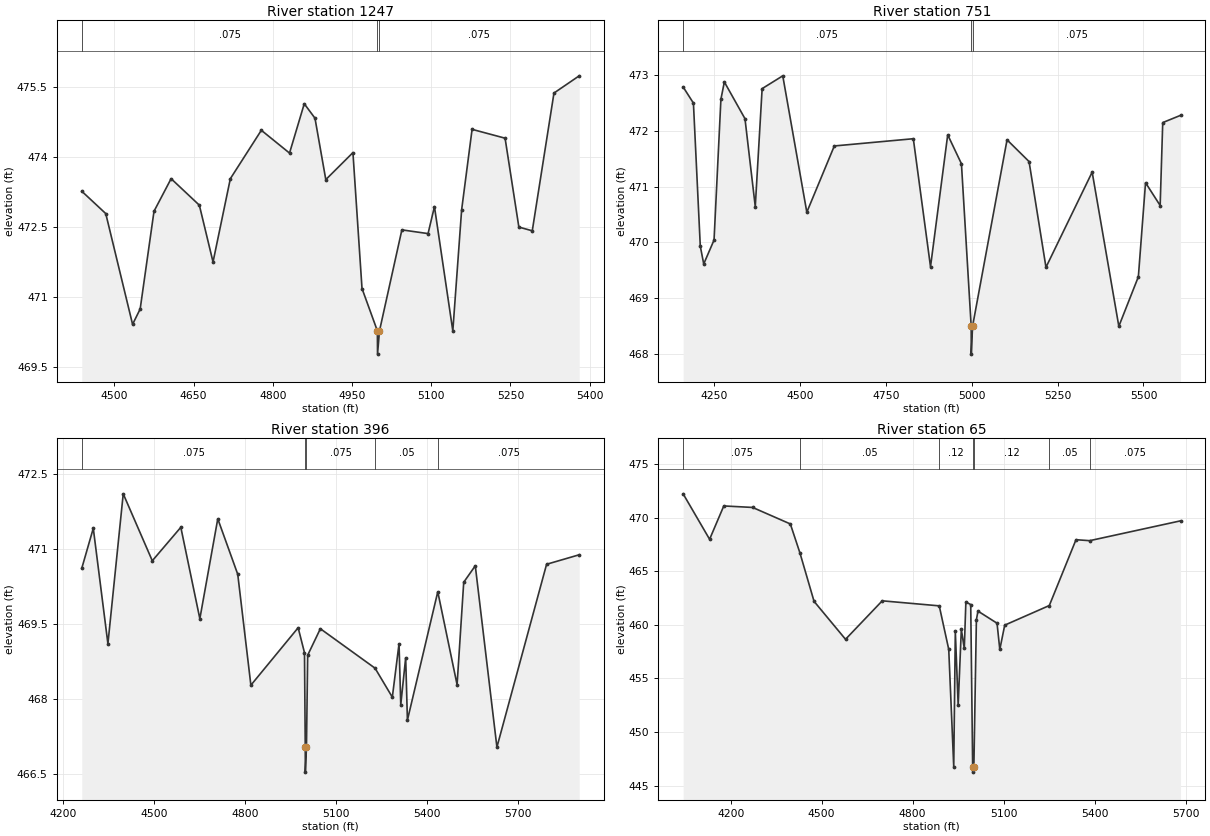
Type RM Length L Ch R = 1 ,1247    ,496,496,496
BEGIN DESCRIPTION:
LWE S 034 3.0
END DESCRIPTION:
XS GIS Cut Line= 3
      2426664.35      7043404.49      2427107.14      7043324.54
       2427585.4      7043208.04
#Sta/Elev= 30
  4438.1  473.27  4483.5  472.79  4534.3  470.41  4548.7  470.74  4574.9  472.84
  4607.3  473.54  4660.8  472.97  4686.7  471.75  4719.5  473.54  4778.2  474.58
  4831.6  474.09  4859.5  475.15  4879.8  474.84  4900.3  473.52  4951.7   474.1
  4968.9  471.18    4998  470.27  4998.3  469.77    5002  470.27  5044.4  472.44
    5094  472.36  5106.1  472.94  5140.9  470.27  5157.6  472.87  5177.4   474.6
  5239.9  474.41    5266   472.5  5291.4  472.42  5332.5  475.38  5380.3  475.75
#Mann= 3 ,-1 , 0
  4438.1    .075       0    4998     .07       0    5002    .075       0
Bank Sta=4998,5002
XS Rating Curve= 0 ,0
Exp/Cntr=0.3,0.1

Type RM Length L Ch R = 1 ,751     ,355,355,355
BEGIN DESCRIPTION:
LWE S 034 2.0
END DESCRIPTION:
XS GIS Cut Line= 3
      2426689.02      7043545.92      2427592.94      7043588.96
      2427955.73      7043183.12
#Sta/Elev= 30
  4158.7  472.79  4188.7   472.5  4208.7  469.93  4218.7  469.61  4248.8  470.04
  4268.8  472.57  4278.8  472.88  4338.9  472.22  4368.9  470.64  4388.9  472.76
    4449  472.99  4519.1  470.54  4599.2  471.73  4829.4  471.86  4879.5  469.56
  4929.6  471.93  4969.6  471.41    4998  468.49  4998.3  467.99    5002  468.49
  5102.5  471.84  5166.6  471.45  5215.9  469.55  5350.5  471.26  5428.2  468.49
  5485.1  469.38    5506  471.07  5548.6  470.66  5556.1  472.15    5608  472.28
#Mann= 3 ,-1 , 0
  4158.7    .075       0    4998     .07       0    5002    .075       0
Bank Sta=4998,5002
XS Rating Curve= 0 ,0
Exp/Cntr=0.3,0.1

Type RM Length L Ch R = 1 ,396     ,331,331,331
BEGIN DESCRIPTION:
LWE S 034 1.0
END DESCRIPTION:
XS GIS Cut Line= 4
      2426676.65      7043644.29      2427506.85      7043896.43
      2427666.73      7043853.38      2427954.85      7043320.05
#Sta/Elev= 30
  4261.5  470.61  4299.4  471.41  4347.6   469.1  4398.1   472.1  4493.9  470.76
  4587.9  471.43  4650.6   469.6  4709.7   471.6  4775.5  470.49  4818.8  468.27
  4974.6  469.42  4995.5  468.92    4998  467.03  4998.3  466.53    5002  467.03
    5006  468.87  5047.8   469.4  5228.1  468.61    5285  468.03  5307.1   469.1
  5312.8  467.88    5329  468.82  5334.7  467.57  5434.8  470.14  5498.4  468.28
  5520.3  470.33  5558.4  470.66  5629.7  467.03  5793.4  470.69  5900.9  470.88
#Mann= 5 ,-1 , 0
  4261.5    .075       0    4998     .07       0    5002    .075       0
  5228.1     .05       0  5434.8    .075       0
#XS Ineff= 2 , 0
       0                    5430       0     470
Permanent Ineff=
       F       F
Bank Sta=4998,5002
XS Rating Curve= 0 ,0
Exp/Cntr=0.3,0.1

Type RM Length L Ch R = 1 ,65      ,0,0,0
BEGIN DESCRIPTION:
LWE S 034 0.5
END DESCRIPTION:
XS GIS Cut Line= 4
      2426650.68      7043869.59      2427480.85      7044121.72
      2427640.73      7044078.67      2427929.39      7043544.34
#Sta/Elev= 30
  4043.1  472.21  4130.4  467.97  4177.2  471.08  4272.3  470.94  4396.7   469.4
  4428.3   466.7  4474.9  462.18  4578.7  458.64  4699.8  462.23  4887.8  461.76
  4919.1   457.7  4935.6  446.75  4940.8  459.38  4950.2  452.51  4960.6  459.56
  4970.4  457.79  4975.6  462.12  4991.6  461.88    4998  446.75  4998.3  446.25
    5002  446.75  5010.3  460.46  5015.5  461.27  5078.4  460.14  5087.5  457.69
  5103.7  459.96  5250.8  461.79  5338.8  467.93  5383.9  467.84  5683.6  469.69
#Mann= 7 ,-1 , 0
  4043.1    .075       0  4428.3     .05       0  4887.8     .12       0
    4998     .07       0    5002     .12       0  5250.8     .05       0
  5383.9    .075       0
Bank Sta=4998,5002
XS Rating Curve= 0 ,0
Exp/Cntr=0.3,0.1

Chan Stop Cuts=-1
Use User Specified Reach Order=0
Composite Channel Slope=5