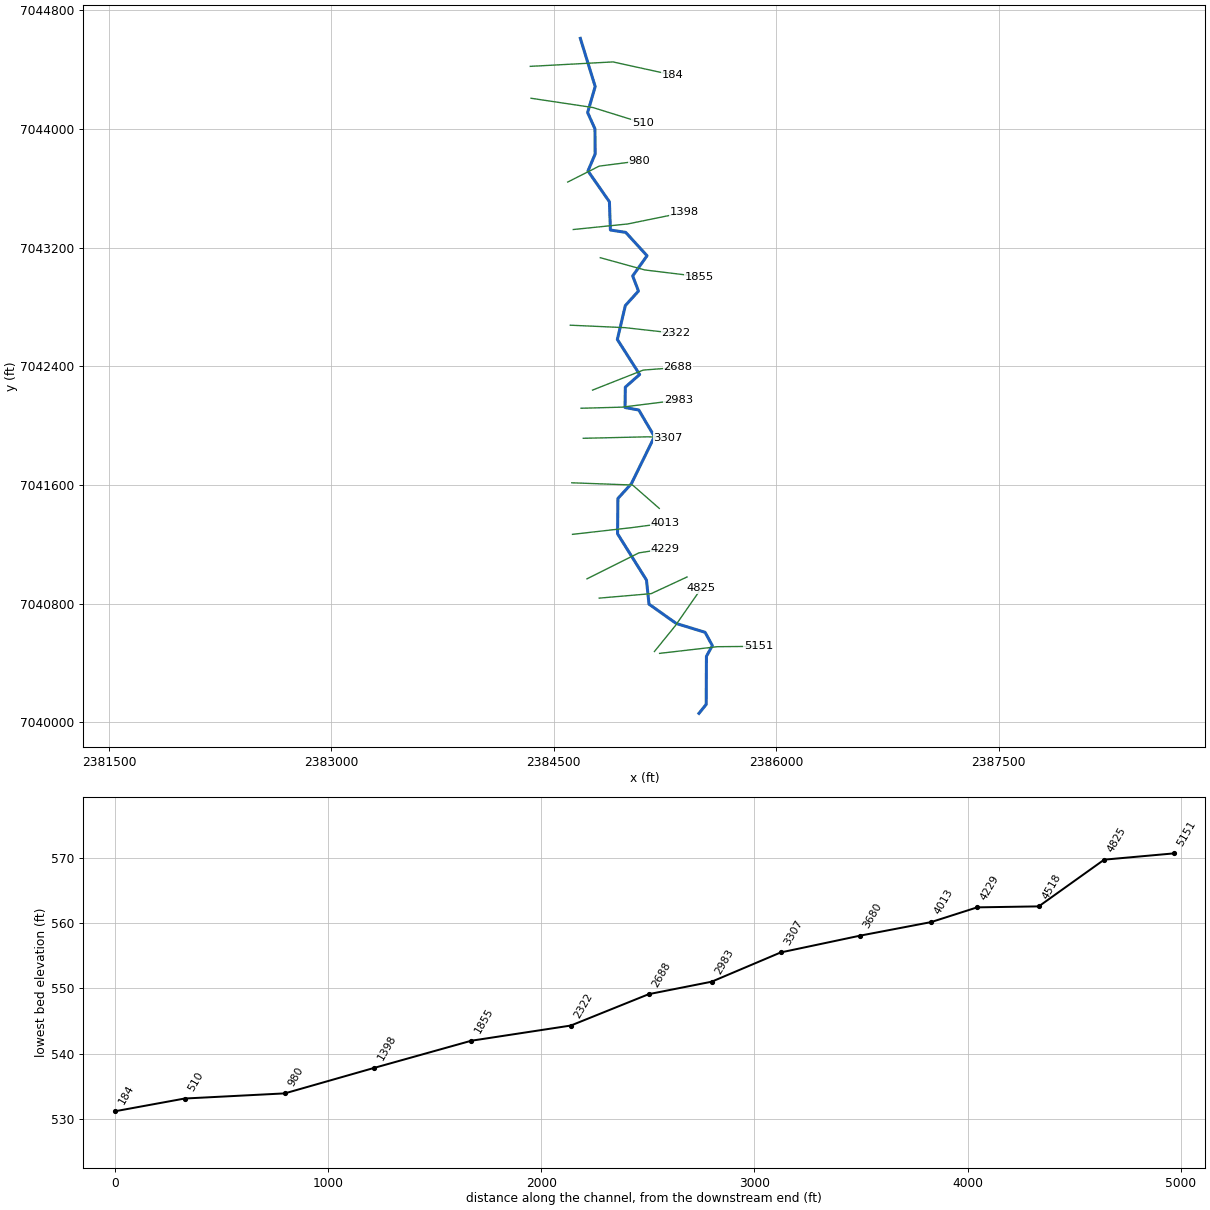
--- LWE S 039.prj (project) ---

Proj Title=LWE S 039 Base Level Engineering
Current Plan=p01
Default Exp/Contr=0.3,0.1
English Units
Geom File=g01
Flow File=f01
Plan File=p01
BEGIN DESCRIPTION:
LWE S 039
END DESCRIPTION:

--- LWE S 039.p01 (plan) ---

Plan Title=Multiple Run
Short Identifier=Multiple
Geom File=g01
Flow File=f01
Subcritical Flow
K Sum by GR= 0
Std Step Tol= 0.01
Critical Tol= 0.01
Num of Std Step Trials= 20
Max Error Tol= 0.3
Flow Tol Ratio= 0.001
Split Flow NTrial= 30
Split Flow Tol= 0.02
Split Flow Ratio= 0.02
Log Output Level= 0
Friction Slope Method= 1
Unsteady Friction Slope Method= 2
Unsteady Bridges Friction Slope Method= 1
Parabolic Critical Depth
Global Vel Dist=  1 , 1 , 1
Global Log Level= 0
CheckData=True
Encroach Param= -1, 0, 0, 0
BEGIN DESCRIPTION:
Multiple Run
END DESCRIPTION:

--- LWE S 039.f01 (steady flow) ---

Flow Title=Multiple
Number of Profiles=7
Profile Names=10-year,25-year,50-year,1pct_min,100-year,1pct_plu,500-year
River Rch & RM= LWE S 039,Reach-1,5151
     572     776     941     567    1131    2257    1632
River Rch & RM= LWE S 039,Reach-1,3680
     773    1068    1312     799    1595    3182    2355
River Rch & RM= LWE S 039,Reach-1,1398
     802    1109    1364     831    1659    3309    2452
Boundary for River Rch & Prof#=LWE S 039,Reach-1,1
Up Type=0
Dn Type=3
Dn Slope=0.005
Boundary for River Rch & Prof#=LWE S 039,Reach-1,2
Up Type=0
Dn Type=3
Dn Slope=0.005
Boundary for River Rch & Prof#=LWE S 039,Reach-1,3
Up Type=0
Dn Type=3
Dn Slope=0.005
Boundary for River Rch & Prof#=LWE S 039,Reach-1,4
Up Type=0
Dn Type=3
Dn Slope=0.005
Boundary for River Rch & Prof#=LWE S 039,Reach-1,5
Up Type=0
Dn Type=3
Dn Slope=0.005
Boundary for River Rch & Prof#=LWE S 039,Reach-1,6
Up Type=0
Dn Type=3
Dn Slope=0.005
Boundary for River Rch & Prof#=LWE S 039,Reach-1,7
Up Type=0
Dn Type=3
Dn Slope=0.005

--- LWE S 039.g01 (geometry) ---

Geom Title=Existing Conditions

River Reach=LWE S 039,Reach-1
Reach XY= 30
      2385479.00      7040060.00      2385528.04      7040120.40
      2385529.66      7040444.84      2385569.61      7040516.67
      2385520.57      7040606.49      2385326.58      7040665.54
      2385142.23      7040796.33      2385125.24      7040958.44
      2384930.20      7041270.50      2384932.55      7041508.53
      2385023.15      7041607.71      2385178.98      7041925.41
      2385073.45      7042104.71      2384980.54      7042121.56
      2384982.47      7042258.73      2385079.24      7042344.29
      2384928.70      7042580.17      2384982.57      7042808.53
      2385071.16      7042906.60      2385032.17      7043008.35
      2385129.11      7043144.64      2384985.12      7043302.12
      2384881.93      7043317.97      2384875.25      7043508.45
      2384730.63      7043716.04      2384778.92      7043830.03
      2384777.78      7043999.50      2384728.18      7044110.00
      2384779.40      7044285.00      2384679.00      7044610.00

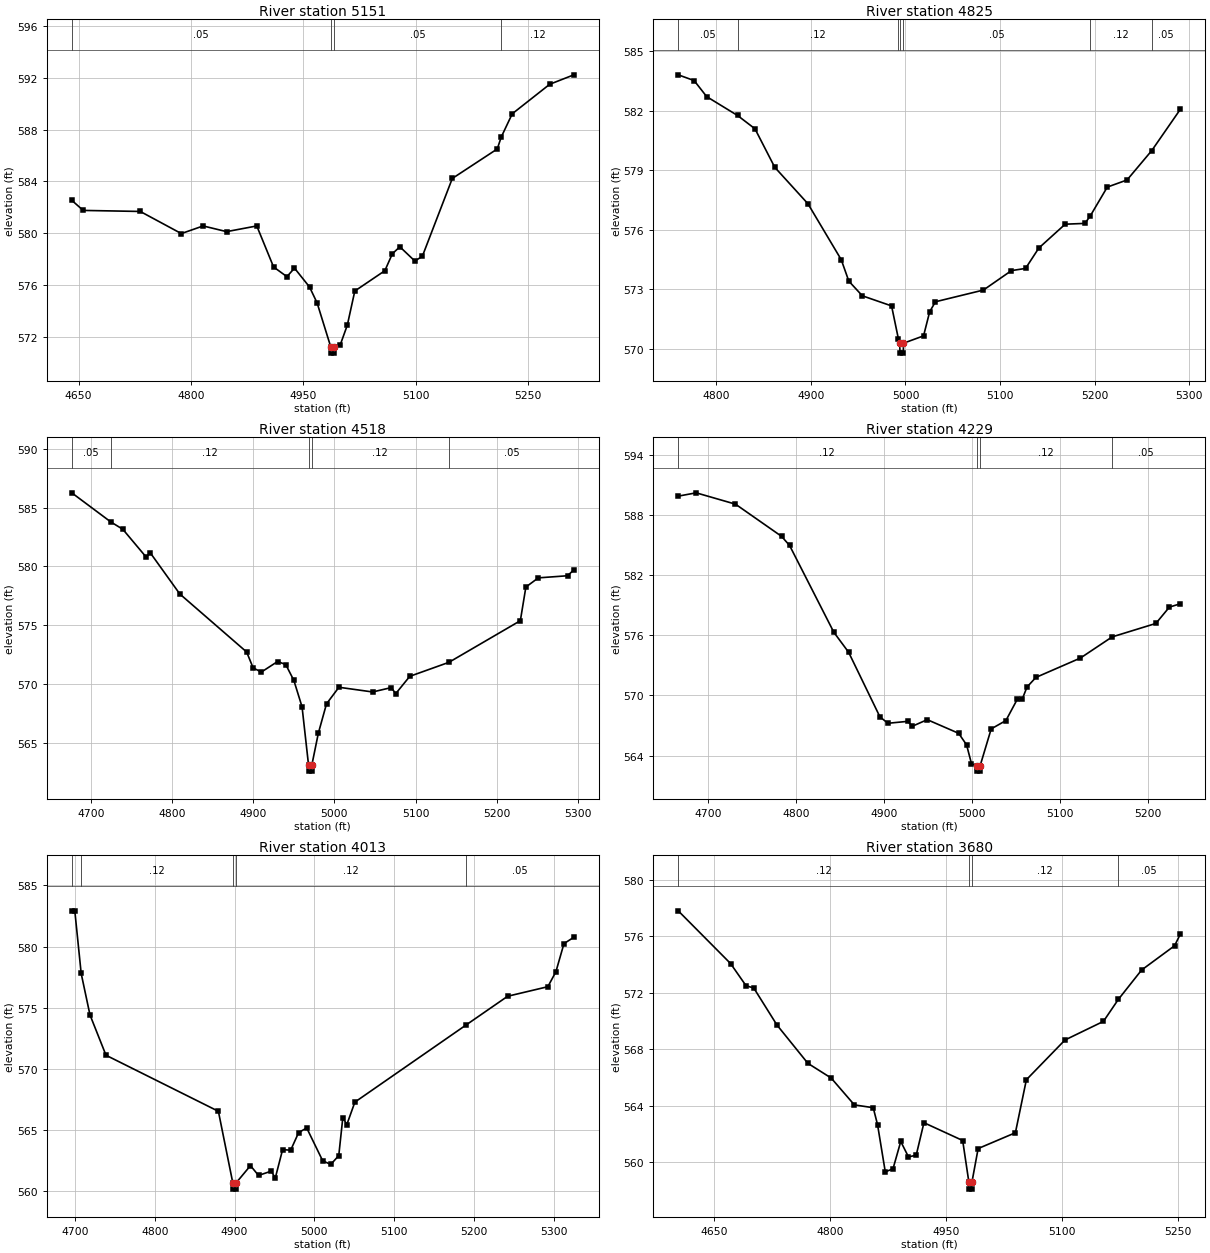
Type RM Length L Ch R = 1,5151,326,326,326
BEGIN DESCRIPTION:
LWE S 039 13.0
END DESCRIPTION:
XS GIS Cut Line= 3
      2385213.75      7040464.45      2385603.70      7040509.44
      2385881.15      7040511.94
#Sta/Elev= 30
  4640.9  582.54  4656.2  581.76  4732.3  581.68  4787.1  579.97  4816.2  580.56
  4847.5  580.12  4887.8  580.56  4910.2  577.39  4928.0  576.64  4938.1  577.30
  4958.2  575.84  4968.3  574.61  4986.4  571.23  4986.7  570.73  4990.2  570.73
  4990.4  571.23  4999.1  571.36  5008.6  572.89  5018.6  575.53  5058.7  577.10
  5068.7  578.41  5078.7  578.95  5098.7  577.85  5108.7  578.21  5148.7  584.23
  5208.7  586.51  5214.0  587.43  5228.7  589.23  5278.7  591.51  5310.9  592.24
#Mann=4,-1,0
  4640.9    0.05       0  4986.4   0.033       0  4990.4    0.05       0
  5214.0    0.12       0
Bank Sta=4986.4,4990.4
Exp/Cntr=0.3,0.1

Type RM Length L Ch R = 1,4825,307,307,307
BEGIN DESCRIPTION:
LWE S 039 12.0
END DESCRIPTION:
XS GIS Cut Line= 3
      2385178.82      7040476.99      2385318.76      7040649.41
      2385495.08      7040902.72
#Sta/Elev= 30
  4759.8  583.80  4776.6  583.51  4789.9  582.70  4822.5  581.75  4840.9  581.08
  4861.8  579.14  4896.9  577.30  4932.1  574.48  4940.1  573.40  4954.4  572.66
  4985.3  572.15  4992.6  570.47  4993.9  570.27  4994.2  569.77  4997.7  569.77
  4997.9  570.27  5019.1  570.64  5025.6  571.86  5031.7  572.36  5082.4  572.95
  5112.0  573.93  5126.9  574.04  5141.0  575.07  5168.8  576.27  5189.7  576.31
  5195.5  576.70  5213.3  578.14  5234.2  578.50  5260.3  579.98  5290.5  582.06
#Mann=7,-1,0
  4759.8    0.05       0  4822.5    0.12       0  4992.6    0.05       0
  4993.9   0.033       0  4997.9    0.05       0  5195.5    0.12       0
  5260.3    0.05       0
Bank Sta=4993.9,4997.9
Exp/Cntr=0.3,0.1

Type RM Length L Ch R = 1,4518,289,289,289
BEGIN DESCRIPTION:
LWE S 039 11.0
END DESCRIPTION:
XS GIS Cut Line= 3
      2384806.37      7040836.87      2385156.30      7040866.87
      2385398.77      7040979.35
#Sta/Elev= 30
  4676.5  586.26  4724.5  583.79  4739.4  583.16  4768.1  580.80  4773.1  581.17
  4809.6  577.66  4891.9  572.73  4899.9  571.38  4910.0  571.02  4930.1  571.92
  4940.1  571.66  4950.1  570.31  4960.2  568.06  4968.2  563.10  4968.5  562.60
  4972.0  562.60  4972.2  563.10  4980.2  565.81  4990.3  568.32  5005.6  569.73
  5047.1  569.33  5070.0  569.70  5075.6  569.19  5092.9  570.66  5141.1  571.85
  5229.1  575.39  5235.9  578.25  5251.2  579.03  5287.2  579.21  5295.0  579.71
#Mann=5,-1,0
  4676.5    0.05       0  4724.5    0.12       0  4968.2    0.07       0
  4972.2    0.12       0  5141.1    0.05       0
Bank Sta=4968.2,4972.2
Exp/Cntr=0.3,0.1

Type RM Length L Ch R = 1,4229,216,216,216
BEGIN DESCRIPTION:
LWE S 039 10.5
END DESCRIPTION:
XS GIS Cut Line= 3
      2384723.89      7040966.84      2385073.82      7041141.80
      2385251.27      7041169.30
#Sta/Elev= 30
  4666.0  589.86  4686.4  590.19  4731.1  589.06  4783.5  585.85  4792.6  584.94
  4842.9  576.29  4859.7  574.30  4895.3  567.86  4904.4  567.22  4926.7  567.41
  4932.3  566.93  4949.1  567.58  4984.8  566.22  4993.8  565.07  4999.4  563.19
  5005.1  562.95  5005.4  562.45  5008.9  562.45  5009.1  562.95  5021.8  566.66
  5038.5  567.49  5051.7  569.65  5057.2  569.65  5062.5  570.83  5072.6  571.79
  5123.2  573.72  5159.3  575.83  5209.0  577.17  5224.4  578.80  5236.8  579.13
#Mann=4,-1,0
  4666.0    0.12       0  5005.1    0.07       0  5009.1    0.12       0
  5159.3    0.05       0
Bank Sta=5005.1,5009.1
Exp/Cntr=0.3,0.1

Type RM Length L Ch R = 1,4013,333,333,333
BEGIN DESCRIPTION:
LWE S 039 10.0
END DESCRIPTION:
XS GIS Cut Line= 3
      2384626.39      7041266.77      2385023.83      7041311.77
      2385251.28      7041341.76
#Sta/Elev= 30
  4695.9  582.93  4699.7  582.93  4707.7  577.81  4718.7  574.43  4738.8  571.13
  4879.7  566.55  4897.8  560.69  4898.1  560.19  4901.6  560.19  4901.8  560.69
  4919.9  562.11  4930.0  561.31  4946.0  561.66  4951.0  561.09  4960.2  563.42
  4970.3  563.37  4980.3  564.81  4990.4  565.19  5010.5  562.50  5020.6  562.21
  5030.6  562.93  5035.7  566.04  5040.7  565.46  5050.8  567.30  5189.5  573.57
  5242.3  575.95  5292.7  576.73  5302.8  577.95  5312.9  580.25  5325.3  580.77
#Mann=5,-1,0
  4695.9    0.05       0  4707.7    0.12       0  4897.8    0.07       0
  4901.8    0.12       0  5189.5    0.05       0
Bank Sta=4897.8,4901.8
Exp/Cntr=0.3,0.1

Type RM Length L Ch R = 1,3680,373,373,373
BEGIN DESCRIPTION:
LWE S 039 9.0
END DESCRIPTION:
XS GIS Cut Line= 3
      2384621.37      7041614.20      2385031.33      7041599.20
      2385211.32      7041441.71
#Sta/Elev= 30
  4603.4  577.80  4671.1  574.07  4691.1  572.50  4701.1  572.34  4731.1  569.72
  4771.1  567.01  4801.2  565.97  4831.2  564.07  4855.6  563.87  4861.2  562.67
  4871.2  559.33  4881.2  559.55  4891.2  561.48  4901.2  560.39  4911.2  560.51
  4921.2  562.81  4971.3  561.55  4979.3  558.61  4979.5  558.11  4983.0  558.11
  4983.3  558.61  4991.3  560.98  5039.5  562.10  5053.7  565.85  5103.6  568.66
  5153.4  569.98  5172.6  571.53  5202.7  573.61  5245.4  575.33  5252.8  576.15
#Mann=4,-1,0
  4603.4    0.12       0  4979.3    0.07       0  4983.3    0.12       0
  5172.6    0.05       0
Bank Sta=4979.3,4983.3
Exp/Cntr=0.3,0.1

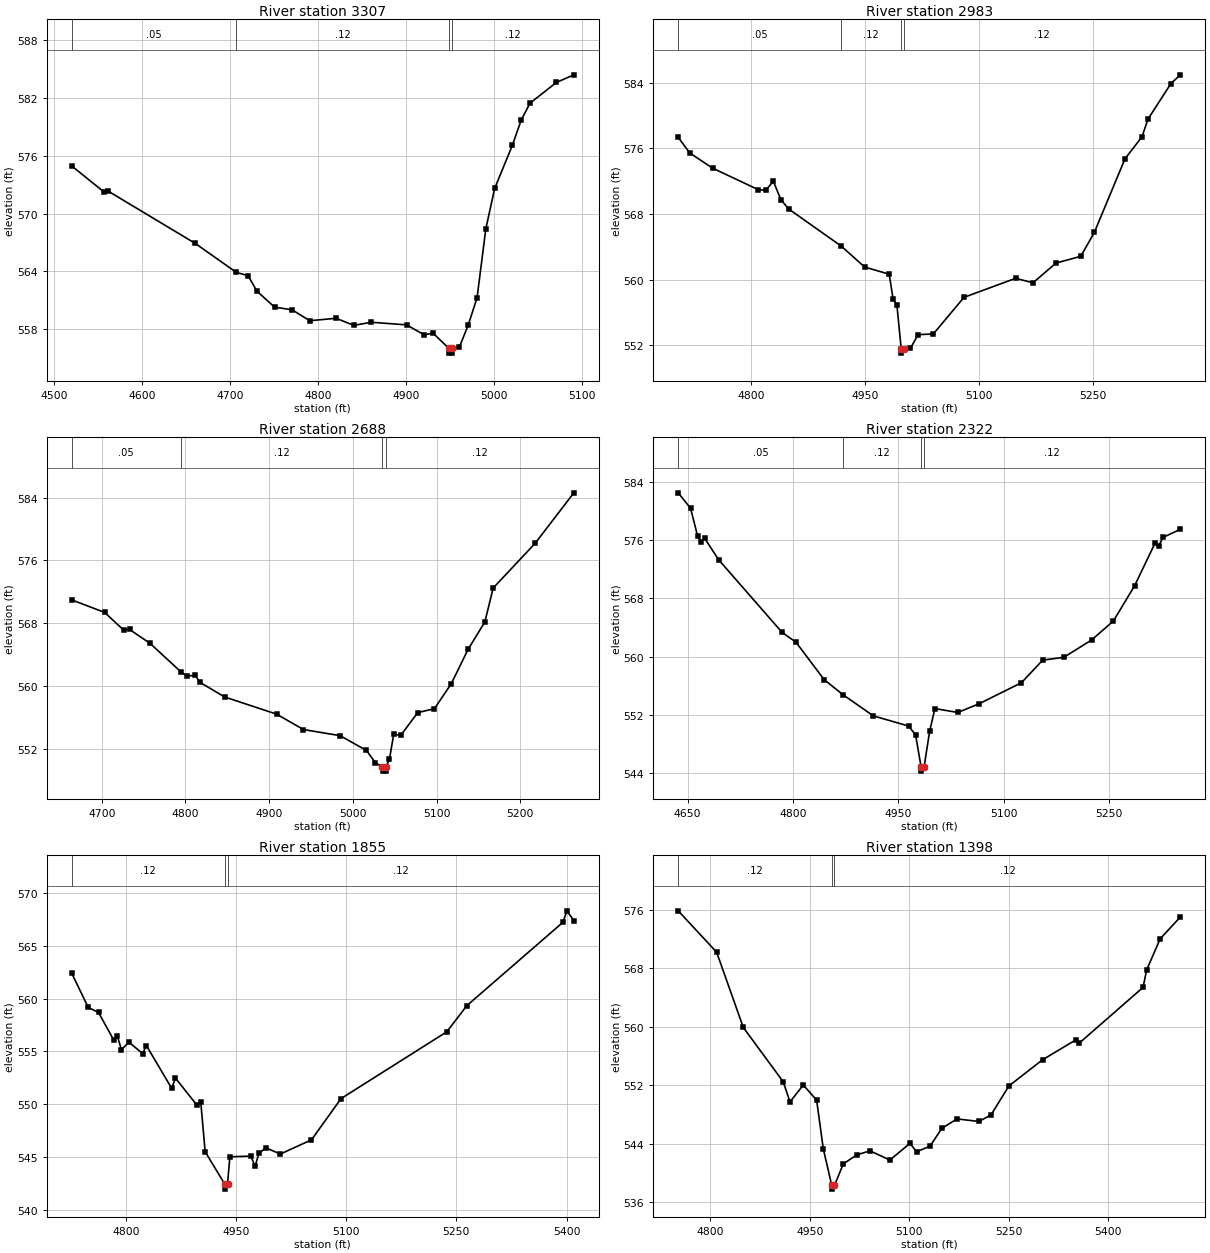
Type RM Length L Ch R = 1,3307,324,324,324
BEGIN DESCRIPTION:
LWE S 039 8.0
END DESCRIPTION:
XS GIS Cut Line= 3
      2384698.90      7041914.13      2385133.80      7041924.13
      2385268.79      7041919.13
#Sta/Elev= 30
  4520.2  574.93  4556.6  572.25  4561.6  572.32  4660.3  566.91  4707.1  563.90
  4720.4  563.56  4730.4  561.96  4750.4  560.30  4770.4  560.02  4790.4  558.89
  4820.4  559.14  4840.4  558.41  4860.4  558.73  4900.4  558.46  4920.4  557.43
  4930.4  557.60  4948.3  556.03  4948.6  555.53  4952.1  555.53  4952.3  556.03
  4960.4  556.17  4970.4  558.45  4980.4  561.27  4990.4  568.44  5000.4  572.60
  5020.5  577.08  5030.5  579.68  5040.5  581.44  5070.5  583.59  5090.3  584.38
#Mann=4,-1,0
  4520.2    0.05       0  4707.1    0.12       0  4948.3    0.07       0
  4952.3    0.12       0
Bank Sta=4948.3,4952.3
Exp/Cntr=0.3,0.1

Type RM Length L Ch R = 1,2983,295,295,295
BEGIN DESCRIPTION:
LWE S 039 7.0
END DESCRIPTION:
XS GIS Cut Line= 3
      2384683.91      7042116.59      2384961.34      7042124.09
      2385341.26      7042171.58
#Sta/Elev= 30
  4704.2  577.34  4719.3  575.44  4749.3  573.59  4809.3  570.97  4819.3  570.88
  4829.3  571.99  4839.3  569.73  4849.3  568.62  4918.8  564.07  4949.4  561.53
  4981.7  560.66  4986.8  557.63  4991.8  556.92  4997.5  551.54  4997.8  551.04
  5001.5  551.54  5009.6  551.62  5019.7  553.29  5039.8  553.38  5080.1  557.84
  5148.0  560.16  5170.8  559.61  5201.1  562.02  5233.7  562.84  5251.5  565.75
  5291.8  574.72  5314.3  577.42  5322.0  579.55  5352.2  583.89  5364.6  584.96
#Mann=4,-1,0
  4704.2    0.05       0  4918.8    0.12       0  4997.5    0.07       0
  5001.5    0.12       0
Bank Sta=4997.5,5001.5
Exp/Cntr=0.3,0.1

Type RM Length L Ch R = 1,2688,366,366,366
BEGIN DESCRIPTION:
LWE S 039 6.0
END DESCRIPTION:
XS GIS Cut Line= 3
      2384761.38      7042239.06      2385103.81      7042374.03
      2385335.08      7042391.44
#Sta/Elev= 30
  4664.1  570.96  4703.4  569.36  4726.0  567.12  4733.1  567.19  4757.5  565.43
  4794.3  561.81  4801.3  561.25  4811.7  561.34  4817.0  560.47  4846.8  558.58
  4908.8  556.40  4941.0  554.43  4984.8  553.65  5016.3  551.76  5026.9  550.20
  5035.4  549.63  5035.6  549.13  5039.1  549.13  5039.4  549.63  5043.7  550.62
  5048.8  553.81  5057.4  553.71  5077.5  556.59  5097.5  557.09  5117.6  560.27
  5137.7  564.65  5157.7  568.14  5167.7  572.47  5217.9  578.18  5264.1  584.61
#Mann=4,-1,0
  4664.1    0.05       0  4794.3    0.12       0  5035.4    0.07       0
  5039.4    0.12       0
Bank Sta=5035.4,5039.4
Exp/Cntr=0.3,0.1

Type RM Length L Ch R = 1,2322,467,467,467
BEGIN DESCRIPTION:
LWE S 039 5.0
END DESCRIPTION:
XS GIS Cut Line= 3
      2384611.46      7042676.46      2384979.00      7042660.00
      2385323.75      7042621.48
#Sta/Elev= 30
  4636.6  582.45  4654.2  580.32  4664.2  576.51  4669.2  575.70  4674.2  576.22
  4694.2  573.27  4784.3  563.34  4804.3  561.97  4844.3  556.85  4871.2  554.78
  4914.4  551.88  4964.5  550.49  4974.5  549.28  4982.5  544.81  4982.7  544.31
  4986.5  544.81  4994.5  549.76  5002.0  552.88  5034.7  552.35  5064.9  553.54
  5125.3  556.43  5155.4  559.52  5185.6  559.91  5225.2  562.29  5256.1  564.88
  5286.3  569.71  5315.5  575.57  5320.6  575.17  5326.5  576.33  5351.4  577.45
#Mann=4,-1,0
  4636.6    0.05       0  4871.2    0.12       0  4982.5    0.07       0
  4986.5    0.12       0
Bank Sta=4982.5,4986.5
Exp/Cntr=0.3,0.1

Type RM Length L Ch R = 1,1855,457,457,457
BEGIN DESCRIPTION:
LWE S 039 4.0
END DESCRIPTION:
XS GIS Cut Line= 3
      2384813.87      7043131.36      2385113.81      7043048.88
      2385483.71      7043003.89
#Sta/Elev= 30
  4726.3  562.38  4748.7  559.16  4762.7  558.68  4783.2  556.11  4788.3  556.47
  4793.9  555.16  4804.2  555.87  4822.8  554.79  4827.9  555.55  4862.4  551.51
  4867.5  552.48  4896.8  549.91  4902.0  550.19  4907.9  545.52  4934.4  542.48
  4934.6  541.98  4938.4  542.48  4941.6  545.04  4970.2  545.10  4976.0  544.13
  4981.2  545.40  4990.9  545.87  5010.4  545.30  5052.7  546.64  5093.0  550.54
  5237.1  556.86  5264.2  559.32  5395.2  567.21  5400.5  568.29  5410.0  567.37
#Mann=3,-1,0
  4726.3    0.12       0  4934.4    0.07       0  4938.4    0.12       0
Bank Sta=4934.4,4938.4
Exp/Cntr=0.3,0.1

Type RM Length L Ch R = 1,1398,418,418,418
BEGIN DESCRIPTION:
LWE S 039 3.0
END DESCRIPTION:
XS GIS Cut Line= 3
      2384631.40      7043321.32      2384998.83      7043358.81
      2385378.77      7043436.30
#Sta/Elev= 30
  4751.8  575.89  4809.7  570.23  4849.9  559.93  4910.2  552.48  4920.3  549.74
  4940.4  552.05  4960.5  549.98  4970.5  543.33  4983.3  538.30  4983.6  537.80
  4987.4  538.30  5000.7  541.25  5020.8  542.48  5040.9  543.04  5071.0  541.78
  5101.2  544.07  5111.3  542.92  5131.5  543.68  5149.5  546.14  5172.3  547.41
  5205.1  547.06  5223.4  547.95  5250.5  551.93  5301.1  555.50  5351.6  558.24
  5356.7  557.80  5452.7  565.41  5458.1  567.78  5478.5  572.06  5508.9  575.04
#Mann=3,-1,0
  4751.8    0.12       0  4983.3    0.07       0  4987.4    0.12       0
Bank Sta=4983.3,4987.4
Exp/Cntr=0.3,0.1

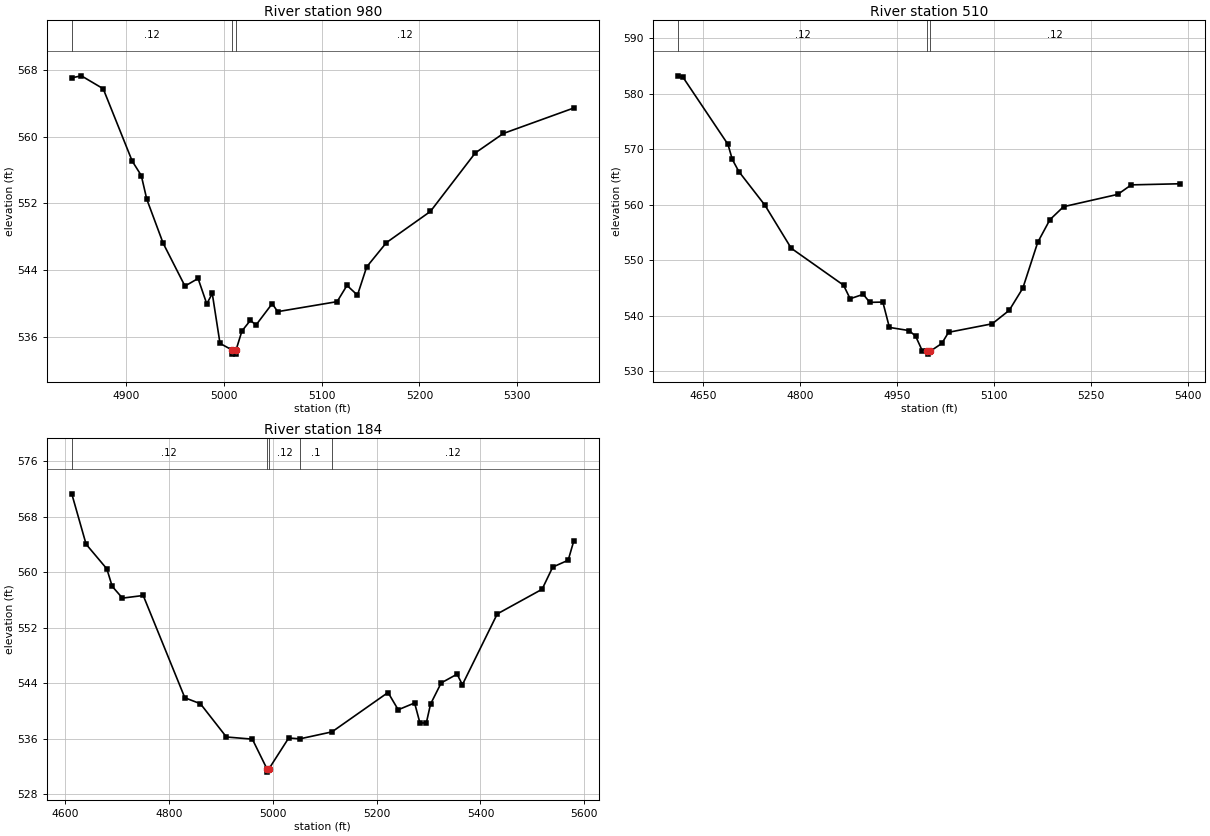
Type RM Length L Ch R = 1,980,470,470,470
BEGIN DESCRIPTION:
LWE S 039 2.0
END DESCRIPTION:
XS GIS Cut Line= 3
      2384593.93      7043641.25      2384806.38      7043748.73
      2385078.85      7043783.72
#Sta/Elev= 30
  4844.9  567.07  4854.7  567.31  4877.0  565.76  4906.6  557.08  4915.9  555.34
  4921.5  552.50  4938.2  547.22  4960.5  542.07  4973.9  542.98  4982.8  539.93
  4988.4  541.18  4996.3  535.19  5008.6  534.40  5008.9  533.90  5012.4  533.90
  5012.7  534.40  5018.7  536.68  5027.4  537.96  5033.0  537.38  5049.6  539.96
  5055.2  539.00  5115.9  540.20  5126.0  542.15  5136.7  540.98  5146.1  544.37
  5166.3  547.29  5211.2  551.03  5257.0  558.05  5285.7  560.39  5357.7  563.45
#Mann=3,-1,0
  4844.9    0.12       0  5008.6    0.07       0  5012.7    0.12       0
Bank Sta=5008.6,5012.7
Exp/Cntr=0.3,0.1

Type RM Length L Ch R = 1,510,326,326,326
BEGIN DESCRIPTION:
LWE S 039 1.0
END DESCRIPTION:
XS GIS Cut Line= 3
      2384346.47      7044206.13      2384763.89      7044143.64
      2385101.27      7044038.68
#Sta/Elev= 30
  4612.2  583.21  4619.8  582.91  4689.0  570.87  4695.7  568.16  4705.8  565.98
  4746.2  559.90  4786.7  552.17  4867.5  545.52  4877.7  543.08  4897.9  543.88
  4908.0  542.43  4928.2  542.48  4938.3  537.92  4968.7  537.35  4978.8  536.35
  4988.9  533.76  4996.9  533.61  4997.2  533.11  5001.1  533.61  5019.2  535.03
  5029.7  537.04  5097.1  538.57  5123.4  541.00  5144.4  544.99  5167.4  553.24
  5186.2  557.31  5207.2  559.65  5291.0  561.87  5311.9  563.58  5387.6  563.78
#Mann=3,-1,0
  4612.2    0.12       0  4996.9    0.07       0  5001.1    0.12       0
Bank Sta=4996.9,5001.1
Exp/Cntr=0.3,0.1

Type RM Length L Ch R = 1,184,0,0,0
BEGIN DESCRIPTION:
LWE S 039 0.3
END DESCRIPTION:
XS GIS Cut Line= 3
      2384341.45      7044421.08      2384898.86      7044451.07
      2385298.79      7044363.58
#Sta/Elev= 30
  4612.3  571.32  4639.9  564.05  4679.9  560.49  4690.2  557.97  4710.0  556.27
  4750.0  556.65  4830.2  541.89  4860.2  541.03  4910.3  536.23  4960.3  535.92
  4988.3  531.66  4988.6  531.16  4992.5  531.66  5030.4  536.09  5051.7  535.96
  5113.8  536.97  5221.8  542.65  5241.4  540.16  5273.0  541.14  5283.3  538.25
  5295.6  538.26  5303.7  540.97  5324.2  544.03  5354.9  545.30  5365.1  543.77
  5432.3  553.99  5518.7  557.55  5539.2  560.75  5569.0  561.74  5579.9  564.55
#Mann=5,-1,0
  4612.3    0.12       0  4988.3    0.07       0  4992.5    0.12       0
  5051.7     0.1       0  5113.8    0.12       0
Bank Sta=4988.3,4992.5
Exp/Cntr=0.3,0.1

Chan Stop Cuts=-1