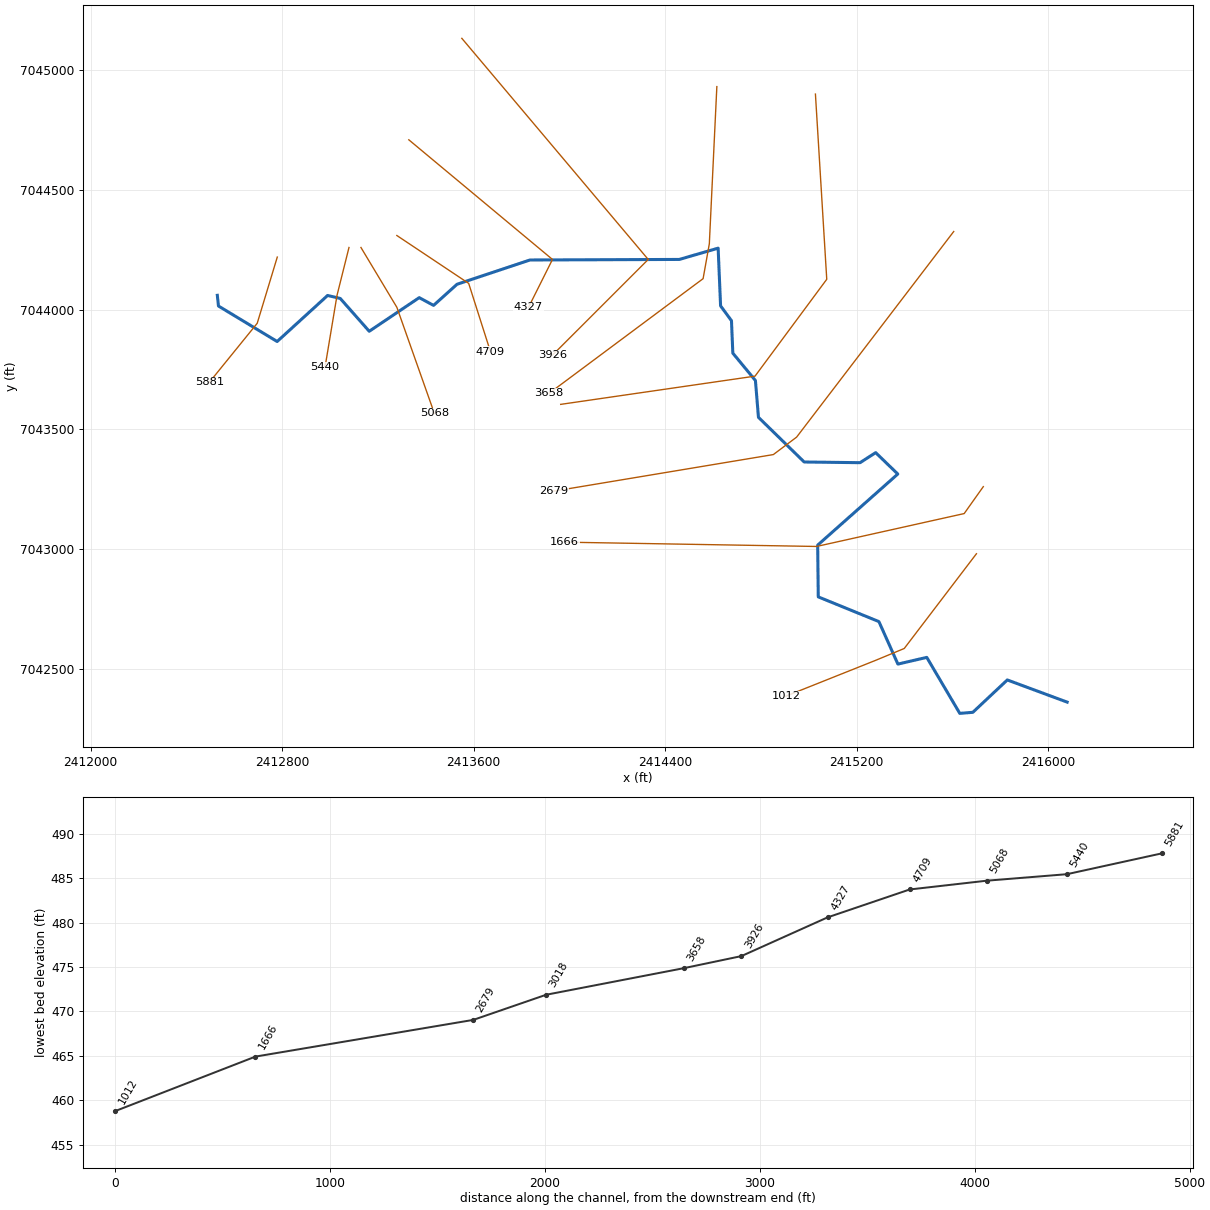
--- LWE S 062.prj (project) ---

Proj Title=LWE S 062 Base Level Engineering
Current Plan=p01
Default Exp/Contr=0.3,0.1
English Units
Geom File=g01
Flow File=f01
Plan File=p01
BEGIN DESCRIPTION:
LWE S 062
END DESCRIPTION:

--- LWE S 062.p01 (plan) ---

Plan Title=Multiple Run
Short Identifier=Multiple
Geom File=g01
Flow File=f01
Subcritical Flow
K Sum by GR= 0
Std Step Tol= 0.01
Critical Tol= 0.01
Num of Std Step Trials= 20
Max Error Tol= 0.3
Flow Tol Ratio= 0.001
Split Flow NTrial= 30
Split Flow Tol= 0.02
Split Flow Ratio= 0.02
Log Output Level= 0
Friction Slope Method= 1
Unsteady Friction Slope Method= 2
Unsteady Bridges Friction Slope Method= 1
Parabolic Critical Depth
Global Vel Dist=  1 , 1 , 1
Global Log Level= 0
CheckData=True
Encroach Param= -1, 0, 0, 0
BEGIN DESCRIPTION:
Multiple Run
END DESCRIPTION:

--- LWE S 062.f01 (steady flow) ---

Flow Title=Multiple
Number of Profiles=7
Profile Names=10-year,25-year,50-year,1pct_min,100-year,1pct_plu,500-year
River Rch & RM= LWE S 062,Reach-1,5881
     817    1136    1403     858    1713    3417    2553
Boundary for River Rch & Prof#=LWE S 062,Reach-1,1
Up Type=0
Dn Type=3
Dn Slope=0.005
Boundary for River Rch & Prof#=LWE S 062,Reach-1,2
Up Type=0
Dn Type=3
Dn Slope=0.005
Boundary for River Rch & Prof#=LWE S 062,Reach-1,3
Up Type=0
Dn Type=3
Dn Slope=0.005
Boundary for River Rch & Prof#=LWE S 062,Reach-1,4
Up Type=0
Dn Type=3
Dn Slope=0.005
Boundary for River Rch & Prof#=LWE S 062,Reach-1,5
Up Type=0
Dn Type=3
Dn Slope=0.005
Boundary for River Rch & Prof#=LWE S 062,Reach-1,6
Up Type=0
Dn Type=3
Dn Slope=0.005
Boundary for River Rch & Prof#=LWE S 062,Reach-1,7
Up Type=0
Dn Type=3
Dn Slope=0.005

--- LWE S 062.g01 (geometry) ---

Geom Title=Existing Conditions

River Reach=LWE S 062,Reach-1
Reach XY= 30
      2412529.00      7044060.00      2412533.90      7044015.28
      2412779.00      7043867.08      2412989.69      7044059.47
      2413042.56      7044047.03      2413163.58      7043909.87
      2413372.45      7044050.41      2413432.33      7044018.01
      2413530.50      7044106.36      2413834.94      7044207.74
      2414458.97      7044210.07      2414621.05      7044257.19
      2414631.26      7044015.94      2414676.72      7043954.05
      2414682.41      7043818.44      2414776.76      7043704.09
      2414789.48      7043550.20      2414980.46      7043363.54
      2415213.84      7043360.66      2415279.13      7043402.68
      2415371.49      7043313.18      2415036.81      7043016.19
      2415039.32      7042799.83      2415292.63      7042696.55
      2415371.94      7042519.01      2415492.56      7042547.01
      2415630.43      7042313.01      2415685.03      7042317.45
      2415828.90      7042452.69      2416079.00      7042360.00

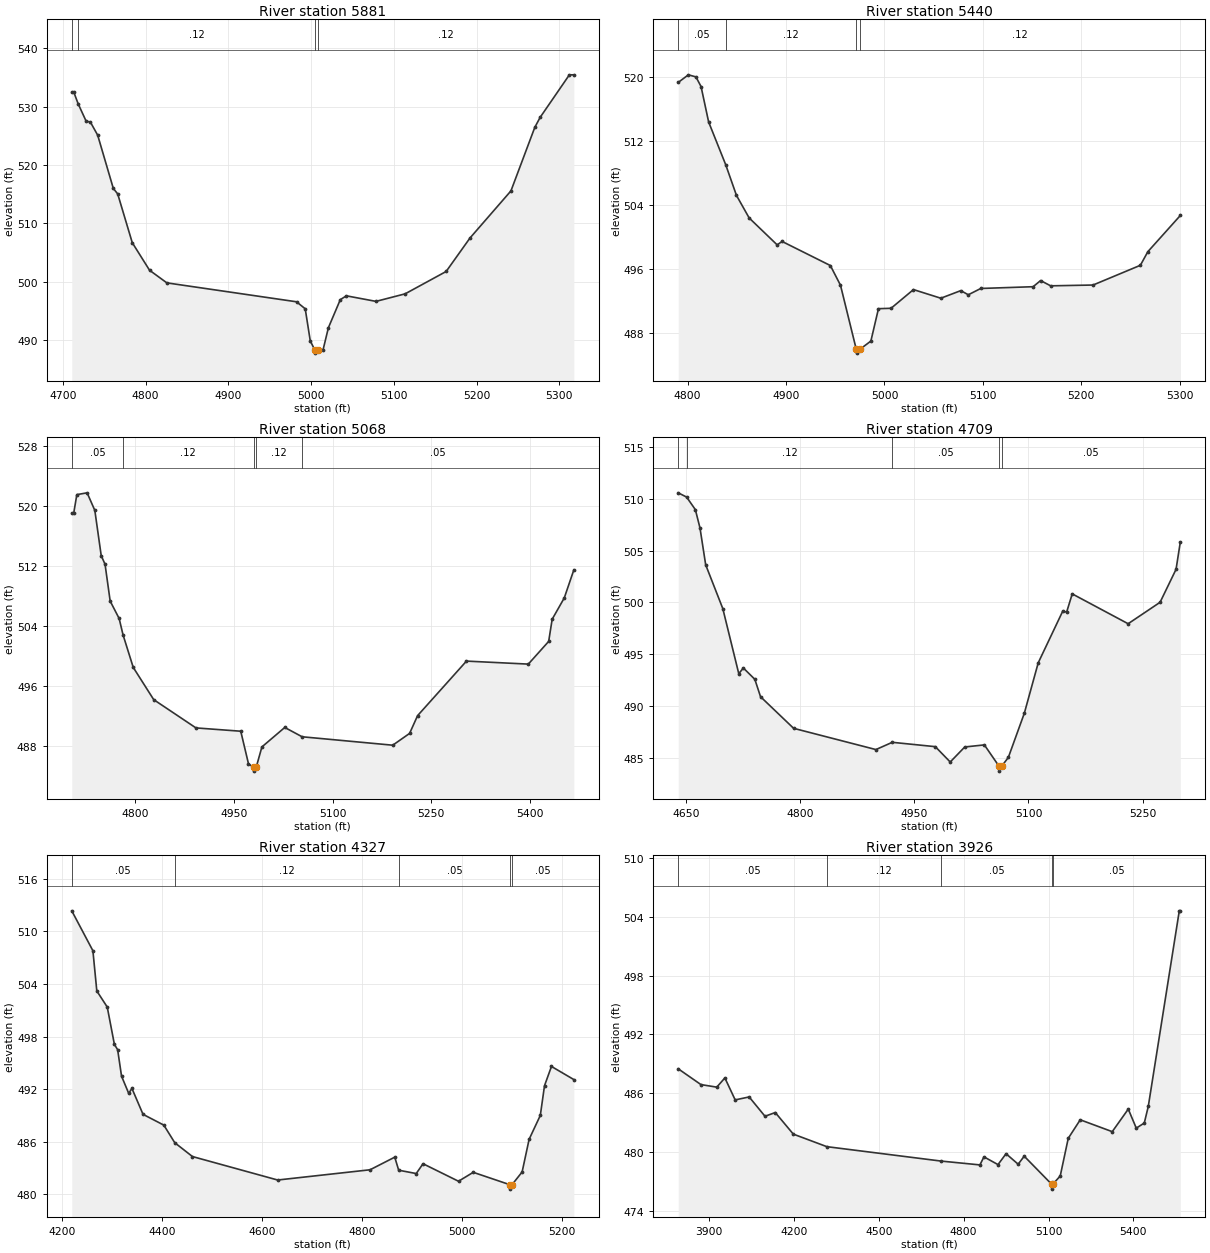
Type RM Length L Ch R = 1,5881,441,441,441
BEGIN DESCRIPTION:
LWE S 062 13.0
END DESCRIPTION:
XS GIS Cut Line= 3
      2412779.51      7044219.96      2412695.68      7043943.29
      2412495.68      7043696.57
#Sta/Elev= 30
  4710.9  532.41  4713.5  532.41  4718.6  530.47  4728.2  527.51  4733.4  527.34
  4742.2  525.10  4761.1  515.98  4766.4  515.04  4784.0  506.69  4804.9  501.97
  4825.8  499.81  4982.5  496.57  4993.0  495.37  4999.1  489.88  5004.7  488.28
  5004.9  487.78  5008.7  488.28  5014.6  488.37  5021.0  492.13  5035.4  496.94
  5042.8  497.59  5078.5  496.64  5113.7  497.93  5163.3  501.76  5192.1  507.49
  5241.6  515.56  5270.4  526.43  5276.8  528.13  5312.2  535.43  5317.6  535.43
#Mann=4,-1,0
  4710.9    0.05       0  4718.6    0.12       0  5004.7    0.07       0
  5008.7    0.12       0
Bank Sta=5004.7,5008.7
Exp/Cntr=0.3,0.1

Type RM Length L Ch R = 1,5440,372,372,372
BEGIN DESCRIPTION:
LWE S 062 12.0
END DESCRIPTION:
XS GIS Cut Line= 3
      2413078.99      7044259.97      2413029.00      7044060.00
      2412978.99      7043759.96
#Sta/Elev= 30
  4790.4  519.31  4800.7  520.26  4808.4  520.00  4813.6  518.79  4821.3  514.36
  4838.6  509.03  4849.6  505.17  4862.5  502.35  4890.9  498.99  4896.0  499.41
  4945.0  496.40  4955.3  493.94  4971.3  485.94  4971.6  485.44  4975.3  485.94
  4986.2  486.95  4993.9  491.00  5006.7  491.05  5029.5  493.39  5057.3  492.31
  5077.6  493.26  5085.2  492.74  5097.9  493.53  5151.1  493.75  5158.7  494.52
  5168.9  493.86  5212.0  493.96  5260.1  496.43  5267.7  498.13  5300.7  502.66
#Mann=4,-1,0
  4790.4    0.05       0  4838.6    0.12       0  4971.3    0.07       0
  4975.3    0.12       0
Bank Sta=4971.3,4975.3
Exp/Cntr=0.3,0.1

Type RM Length L Ch R = 1,5068,359,359,359
BEGIN DESCRIPTION:
LWE S 062 11.0
END DESCRIPTION:
XS GIS Cut Line= 3
      2413129.01      7044259.98      2413279.00      7044010.00
      2413435.79      7043566.31
#Sta/Elev= 30
  4704.2  519.01  4707.1  519.01  4711.9  521.50  4727.5  521.74  4739.2  519.40
  4748.9  513.38  4754.7  512.24  4762.5  507.33  4776.1  505.02  4782.0  502.85
  4797.5  498.51  4828.6  494.22  4892.7  490.46  4960.7  490.02  4972.4  485.70
  4980.1  485.21  4980.4  484.71  4984.1  485.21  4992.8  487.93  5027.5  490.52
  5053.9  489.28  5191.4  488.16  5217.0  489.73  5229.1  492.09  5303.3  499.35
  5397.2  498.95  5428.1  501.97  5433.4  504.92  5451.8  507.76  5466.3  511.49
#Mann=5,-1,0
  4704.2    0.05       0  4782.0    0.12       0  4980.1    0.07       0
  4984.1    0.12       0  5053.9    0.05       0
Bank Sta=4980.1,4984.1
Exp/Cntr=0.3,0.1

Type RM Length L Ch R = 1,4709,382,382,382
BEGIN DESCRIPTION:
LWE S 062 10.0
END DESCRIPTION:
XS GIS Cut Line= 3
      2413278.99      7044310.01      2413579.00      7044110.00
      2413670.00      7043824.62
#Sta/Elev= 30
  4639.5  510.57  4650.5  510.16  4662.0  508.95  4668.1  507.18  4675.6  503.62
  4698.1  499.40  4719.1  493.12  4725.1  493.67  4740.2  492.58  4747.7  490.90
  4791.2  487.85  4899.4  485.80  4920.9  486.50  4977.5  486.08  4997.1  484.60
  5016.2  486.05  5042.0  486.25  5061.0  484.22  5061.3  483.72  5065.0  484.22
  5073.5  485.04  5094.5  489.30  5112.8  494.17  5145.0  499.15  5150.2  499.07
  5157.5  500.82  5231.0  497.94  5273.0  500.01  5294.0  503.19  5299.6  505.82
#Mann=5,-1,0
  4639.5    0.05       0  4650.5    0.12       0  4920.9    0.05       0
  5061.0   0.033       0  5065.0    0.05       0
Bank Sta=5061,5065
Exp/Cntr=0.3,0.1

Type RM Length L Ch R = 1,4327,401,401,401
BEGIN DESCRIPTION:
LWE S 062 9.0
END DESCRIPTION:
XS GIS Cut Line= 3
      2413328.98      7044710.01      2413929.00      7044210.00
      2413828.98      7044009.96
#Sta/Elev= 30
  4219.1  512.36  4261.4  507.80  4269.2  503.21  4290.1  501.37  4304.4  497.11
  4310.9  496.50  4318.7  493.48  4333.0  491.52  4339.5  492.08  4361.7  489.12
  4403.3  487.89  4425.2  485.88  4460.6  484.30  4631.1  481.62  4816.0  482.79
  4865.4  484.23  4873.3  482.74  4908.4  482.36  4922.0  483.48  4993.0  481.48
  5022.5  482.50  5096.0  481.08  5096.2  480.58  5100.0  481.08  5120.3  482.54
  5134.3  486.27  5156.7  489.00  5165.1  492.39  5179.0  494.59  5223.8  493.09
#Mann=5,-1,0
  4219.1    0.05       0  4425.2    0.12       0  4873.3    0.05       0
  5096.0   0.033       0  5100.0    0.05       0
Bank Sta=5096,5100
Exp/Cntr=0.3,0.1

Type RM Length L Ch R = 1,3926,268,268,268
BEGIN DESCRIPTION:
LWE S 062 8.0
END DESCRIPTION:
XS GIS Cut Line= 3
      2413550.36      7045134.06      2414329.00      7044210.00
      2413928.97      7043809.97
#Sta/Elev= 30
  3791.6  488.49  3871.8  486.88  3927.8  486.62  3956.4  487.56  3992.8  485.32
  4042.2  485.62  4098.2  483.65  4134.5  484.03  4198.2  481.83  4316.7  480.55
  4720.6  479.08  4857.6  478.69  4871.9  479.51  4921.5  478.72  4949.9  479.83
  4992.8  478.76  5014.1  479.58  5111.1  476.72  5111.4  476.22  5115.1  476.72
  5141.4  477.56  5169.7  481.40  5212.1  483.29  5325.2  482.08  5381.8  484.38
  5410.1  482.44  5438.4  482.96  5452.5  484.65  5562.1  504.60  5565.7  504.60
#Mann=5,-1,0
  3791.6    0.05       0  4316.7    0.12       0  4720.6    0.05       0
  5111.1   0.033       0  5115.1    0.05       0
Bank Sta=5111.1,5115.1
Exp/Cntr=0.3,0.1

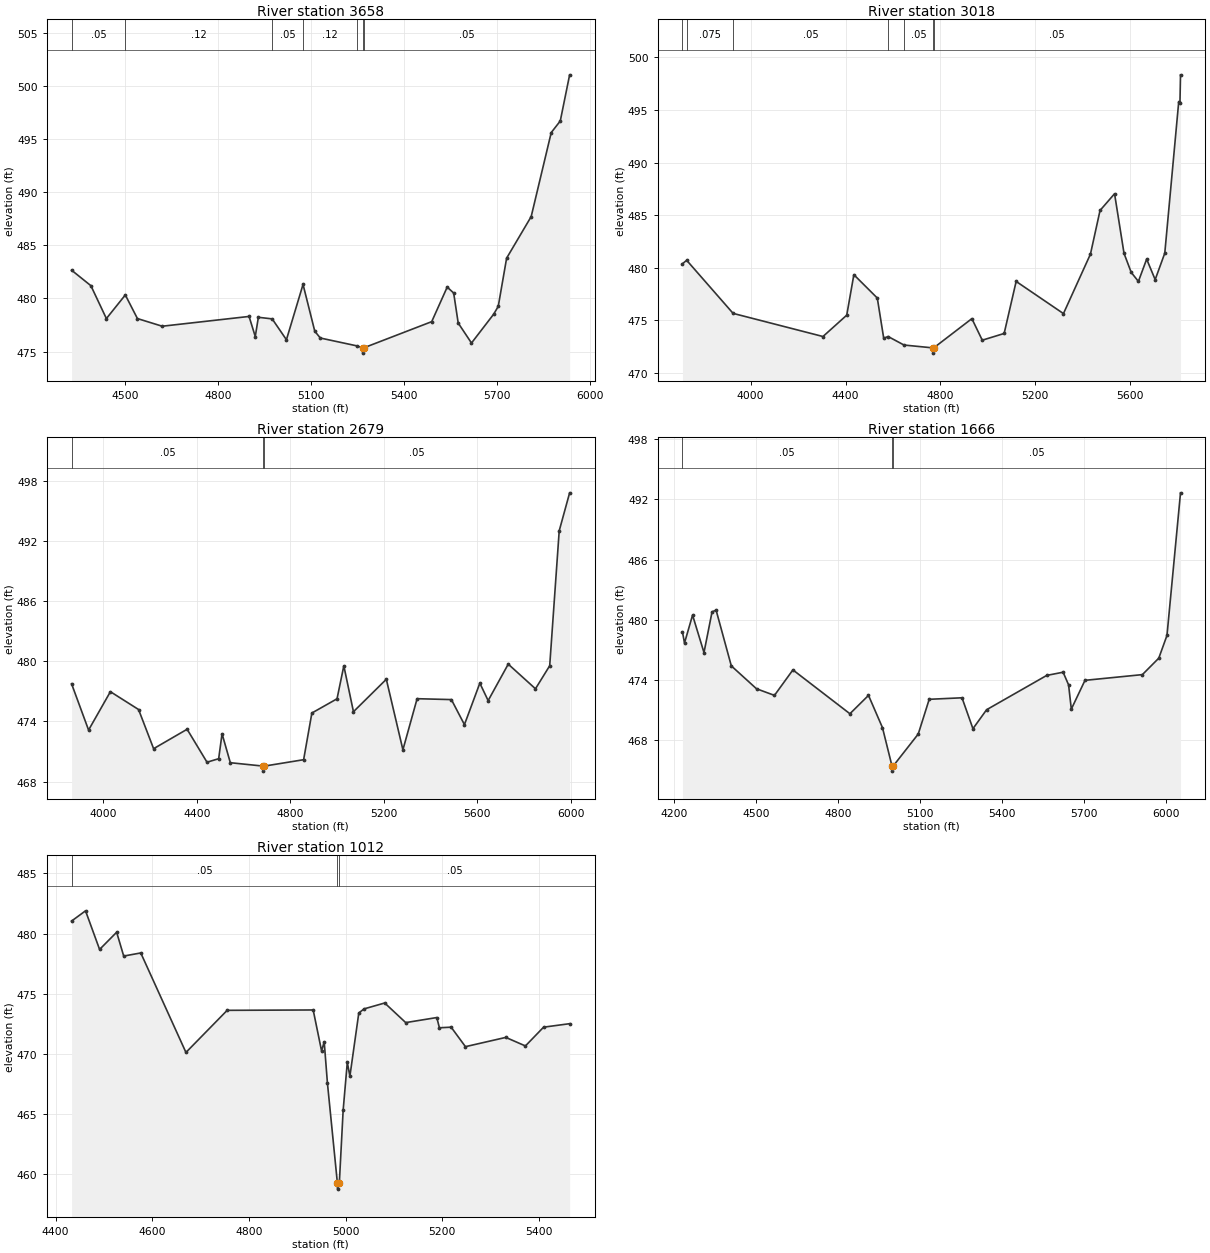
Type RM Length L Ch R = 1,3658,640,640,640
BEGIN DESCRIPTION:
Mapping XS f6b73f0e
END DESCRIPTION:
XS GIS Cut Line= 4
      2414615.64      7044932.31      2414584.25      7044275.53
      2414558.21      7044129.70      2413914.95      7043650.51
#Sta/Elev= 30
  4327.7  482.66  4390.1  481.20  4440.1  478.11  4501.2  480.33  4540.3  478.11
  4620.3  477.39  4900.7  478.31  4920.7  476.42  4930.7  478.23  4975.3  478.08
  5021.3  476.12  5074.9  481.32  5112.8  476.92  5130.7  476.28  5249.1  475.54
  5267.2  475.36  5267.5  474.86  5271.2  475.36  5490.3  477.82  5540.3  481.07
  5561.2  480.51  5575.8  477.69  5618.7  475.81  5690.5  478.53  5705.1  479.26
  5732.1  483.79  5811.4  487.70  5876.1  495.60  5905.3  496.69  5935.5  501.03
#Mann=7,-1,0
  4327.7    0.05       0  4501.2    0.12       0  4975.3    0.05       0
  5074.9    0.12       0  5249.1    0.05       0  5267.2   0.033       0
  5271.2    0.05       0
Bank Sta=5267.2,5271.2
Exp/Cntr=0.3,0.1

Type RM Length L Ch R = 1,3018,339,339,339
BEGIN DESCRIPTION:
Mapping XS a7fc6d99
END DESCRIPTION:
XS GIS Cut Line= 4
      2415027.42      7044901.16      2415074.74      7044127.09
      2414775.17      7043722.35      2413963.36      7043604.39
#Sta/Elev= 30
  3712.7  480.37  3730.5  480.70  3926.2  475.65  4305.0  473.45  4405.2  475.48
  4435.2  479.33  4534.0  477.11  4561.1  473.28  4579.5  473.45  4646.6  472.64
  4767.9  472.37  4768.1  471.87  4771.9  472.37  4932.6  475.15  4976.5  473.10
  5068.7  473.74  5119.3  478.69  5318.7  475.63  5432.5  481.29  5472.9  485.44
  5534.1  487.03  5574.0  481.36  5604.3  479.55  5634.6  478.69  5669.4  480.81
  5705.3  478.86  5745.8  481.38  5804.6  495.79  5809.7  495.64  5812.1  498.34
#Mann=7,-1,0
  3712.7    0.05       0  3730.5   0.075       0  3926.2    0.05       0
  4579.5    0.12       0  4646.6    0.05       0  4767.9   0.033       0
  4771.9    0.05       0
Bank Sta=4767.9,4771.9
Exp/Cntr=0.3,0.1

Type RM Length L Ch R = 1,2679,1013,1013,1013
BEGIN DESCRIPTION:
Mapping XS 0c689262
END DESCRIPTION:
XS GIS Cut Line= 4
      2415605.14      7044326.81      2414948.84      7043467.47
      2414851.62      7043394.55      2413934.99      7043241.78
#Sta/Elev= 30
  3863.4  477.76  3936.2  473.14  4029.6  476.97  4150.2  475.19  4214.6  471.28
  4358.0  473.22  4443.2  469.93  4493.1  470.28  4507.6  472.77  4543.0  469.88
  4684.3  469.54  4684.6  469.04  4688.3  469.54  4856.8  470.18  4892.1  474.84
  4999.8  476.26  5028.9  479.55  5070.1  474.97  5210.8  478.21  5281.8  471.17
  5342.6  476.27  5489.4  476.18  5545.2  473.68  5611.1  477.82  5646.7  476.08
  5732.7  479.72  5849.3  477.26  5910.2  479.56  5950.9  493.03  5995.5  496.82
#Mann=3,-1,0
  3863.4    0.05       0  4684.3   0.033       0  4688.3    0.05       0
Bank Sta=4684.3,4688.3
Exp/Cntr=0.3,0.1

Type RM Length L Ch R = 1,1666,654,654,654
BEGIN DESCRIPTION:
Mapping XS 055446a8
END DESCRIPTION:
XS GIS Cut Line= 4
      2415728.69      7043260.55      2415648.83      7043148.06
      2415032.11      7043010.54      2413979.49      7043028.53
#Sta/Elev= 30
  4231.8  478.79  4239.3  477.68  4268.8  480.46  4310.6  476.73  4340.1  480.78
  4354.9  480.96  4410.6  475.40  4502.8  473.12  4568.5  472.46  4636.0  475.00
  4844.6  470.63  4912.6  472.46  4963.8  469.24  4998.7  465.41  4998.9  464.91
  5002.7  465.41  5094.7  468.61  5134.8  472.07  5254.8  472.22  5294.8  469.14
  5344.8  471.03  5564.8  474.45  5624.8  474.77  5644.8  473.51  5654.8  471.09
  5704.8  473.96  5914.9  474.53  5974.9  476.17  6004.9  478.44  6054.4  492.65
#Mann=3,-1,0
  4231.8    0.05       0  4998.7   0.033       0  5002.7    0.05       0
Bank Sta=4998.7,5002.7
Exp/Cntr=0.3,0.1

Type RM Length L Ch R = 1,1012,0,0,0
BEGIN DESCRIPTION:
LWE S 062 7.0
END DESCRIPTION:
XS GIS Cut Line= 4
      2415699.93      7042980.07      2415398.43      7042584.18
      2415276.90      7042533.83      2414903.98      7042384.99
#Sta/Elev= 30
  4432.9  481.04  4461.8  481.89  4490.9  478.68  4526.2  480.11  4540.8  478.13
  4576.1  478.39  4669.6  470.12  4754.9  473.62  4932.9  473.65  4950.3  470.24
  4955.7  471.01  4962.4  467.57  4983.0  459.26  4983.3  458.76  4987.0  459.26
  4994.9  465.31  5003.5  469.29  5008.9  468.15  5027.3  473.40  5038.2  473.74
  5080.9  474.23  5124.4  472.60  5188.7  473.02  5194.1  472.17  5218.4  472.22
  5248.0  470.60  5331.5  471.37  5372.1  470.66  5409.7  472.22  5463.6  472.51
#Mann=3,-1,0
  4432.9    0.05       0  4983.0   0.033       0  4987.0    0.05       0
Bank Sta=4983,4987
Exp/Cntr=0.3,0.1

Chan Stop Cuts=-1