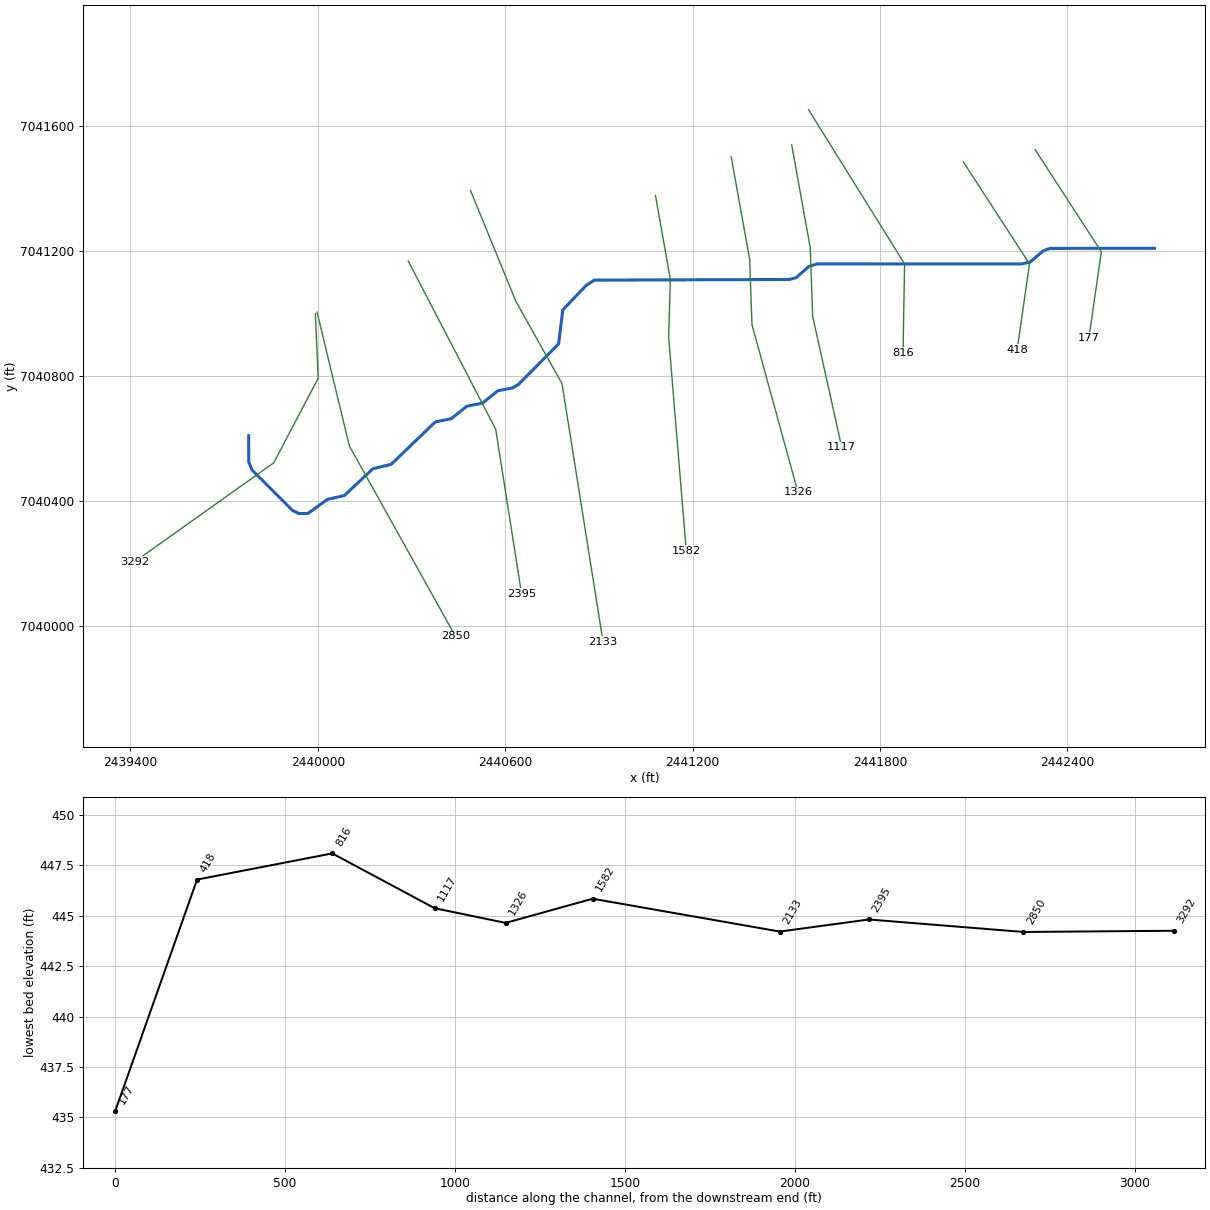
--- LWE S 066.prj (project) ---

Proj Title=LWE S 066 Base Level Engineering
Current Plan=p01
Default Exp/Contr=0.3,0.1
English Units
Geom File=g01
Flow File=f01
Plan File=p01
Y Axis Title=Elevation
X Axis Title(PF)=Main Channel Distance
X Axis Title(XS)=Station
BEGIN DESCRIPTION:
LWE S 066
END DESCRIPTION:
DSS Export Rating Curves= 0
DSS Export Rating Curve Sorted= 0
DSS Export Volume Flow Curves= 0
DXF OffsetX= 0
DXF OffsetY= 0
DXF ScaleX= 1
DXF ScaleY= 10

--- LWE S 066.p01 (plan) ---

Plan Title=Multiple Run
Program Version=4.10
Short Identifier=Multiple
Geom File=g01
Flow File=f01
Subcritical Flow
K Sum by GR= 0
Std Step Tol= 0.01
Critical Tol= 0.01
Num of Std Step Trials= 20
Max Error Tol= 0.3
Flow Tol Ratio= 0.001
Split Flow NTrial= 30
Split Flow Tol= 0.02
Split Flow Ratio= 0.02
Log Output Level= 0
Friction Slope Method= 1
Unsteady Friction Slope Method= 2
Unsteady Bridges Friction Slope Method= 1
Parabolic Critical Depth
Global Vel Dist= 1 , 1 , 1
Global Log Level= 0
CheckData=True
Encroach Param=-1 ,0,0, 0
BEGIN DESCRIPTION:
Multiple Run
END DESCRIPTION:
Computation Interval=1HOUR
Output Interval=1HOUR
Run HTab= 0
Run UNet= 0
Run PostProcess= 0
Run WQNet= 0
UNET Theta= 1
UNET Theta Warmup= 1
UNET ZTol= 0.02
UNET ZSATol= 0.05
UNET MxIter= 20
UNET MaxInSteps= 0
UNET DtIC= 0
UNET DtMin= 0
UNET MaxCRTS= 20
UNET WFStab= 2
UNET SFStab= 1
UNET WFX= 1
UNET SFX= 1
UNET DSS MLevel= 4
UNET DZMax Abort= 100
UNET Convert EG Bridges= 0
UNET Use Existing IB Tables=-1
UNET Froude Reduction=False
UNET Froude Limit= 1
UNET Froude Power= 10
UNET Time Slicing=0,0, 5
UNET Junction Losses=0
Instantaneous Interval=1HOUR
Write IC File= 0
Write IC File at Sim End=0
Echo Input=False
Echo Parameters=False
Echo Output=False
Write Detailed= 0
WQ AD Non Conservative
WQ ULTIMATE=-1
WQ Max Comp Step=1HOUR
WQ Output Interval=15MIN
WQ Output Selected Increments= 0
WQ Output face flow=0
WQ Output face velocity=0
WQ Output face area=0
WQ Output face dispersion=0
WQ Output cell volume=0
WQ Output cell surface area=0
WQ Output cell continuity=0
WQ Output cumulative cell continuity=0
WQ Output face conc=0
WQ Output face dconc_dx=0
WQ Output face courant=0
WQ Output face peclet=0
WQ Output face adv mass=0
WQ Output face disp mass=0
WQ Output cell mass=0
WQ Output cell source sink temp=0
WQ Output cell source sink nsm=0
WQ Output MaxMinRange=-1
WQ Daily Max Min Mean=-1
WQ Daily Range=0
WQ Daily Time=0
WQ Create Restart=0
WQ Fixed Restart=0
WQ System Summary=0
WQ Use Fixed Temperature=0
Sorting and Armoring Iterations= 10
XS Update Threshold= 0.02
Hydraulics Update Threshold= 0.02
Energy Slope Method= 1
Volume Change Method= 0
XS Weighting Method= 0
Number of US Weighted Cross Sections= 1
Number of DS Weighted Cross Sections= 1
Upstream XS Weight=0.25
Main XS Weight=0.5
Downstream XS Weight=0.25
Number of DS XS's Weighted with US Boundary= 1
Upstream Boundary Weight= 1
Weight of XSs Associated with US Boundary= 0
Number of US XS's Weighted with DS Boundary= 1
Downstream Boundary Weight= 0.5
Weight of XSs Associated with DS Boundary= 0.5
Sediment Output Level= 4
Mass or Volume Output= 0
Output Increment Type= 1
Profile and TS Output Increment= 10
XS Output Flag= 0
XS Output Increment= 10
Disregard all LS=0
Disregard all Conn=0
Disregard all Breaches=0
Disregard all Pumps=0

--- LWE S 066.f01 (steady flow) ---

Flow Title=Multiple
Number of Profiles=7
Profile Names=10-year,25-year,50-year,1pct_min,100-year,1pct_plu,500-year
River Rch & RM= LWE S 066,Reach-1,3292
     377     489     577     337     673    1343     916
Boundary for River Rch & Prof#=LWE S 066,Reach-1,1
Up Type=0
Dn Type=3
Dn Slope=0.005
Boundary for River Rch & Prof#=LWE S 066,Reach-1,2
Up Type=0
Dn Type=3
Dn Slope=0.005
Boundary for River Rch & Prof#=LWE S 066,Reach-1,3
Up Type=0
Dn Type=3
Dn Slope=0.005
Boundary for River Rch & Prof#=LWE S 066,Reach-1,4
Up Type=0
Dn Type=3
Dn Slope=0.005
Boundary for River Rch & Prof#=LWE S 066,Reach-1,5
Up Type=0
Dn Type=3
Dn Slope=0.005
Boundary for River Rch & Prof#=LWE S 066,Reach-1,6
Up Type=0
Dn Type=3
Dn Slope=0.005
Boundary for River Rch & Prof#=LWE S 066,Reach-1,7
Up Type=0
Dn Type=3
Dn Slope=0.005

--- LWE S 066.g01 (geometry) ---

Geom Title=Existing Conditions

River Reach=LWE S 066,Reach-1
Reach XY= 30
      2439779.00      7040610.00      2439779.12      7040525.05
      2439789.43      7040500.18      2439919.32      7040370.19
      2439939.62      7040360.59      2439968.30      7040360.70
      2440030.73      7040405.75      2440085.05      7040418.15
      2440176.72      7040504.13      2440235.05      7040518.16
      2440376.70      7040654.17      2440427.26      7040664.19
      2440476.80      7040703.92      2440527.28      7040714.16
      2440576.81      7040753.90      2440622.97      7040762.50
      2440642.22      7040773.62      2440771.14      7040903.83
      2440784.52      7041012.44      2440858.79      7041090.41
      2440884.84      7041107.95      2441508.97      7041110.07
      2441531.33      7041115.75      2441572.94      7041151.86
      2441599.03      7041159.93      2442254.08      7041159.80
      2442281.33      7041165.75      2442322.94      7041201.86
      2442344.22      7041209.48      2442679.00      7041210.00

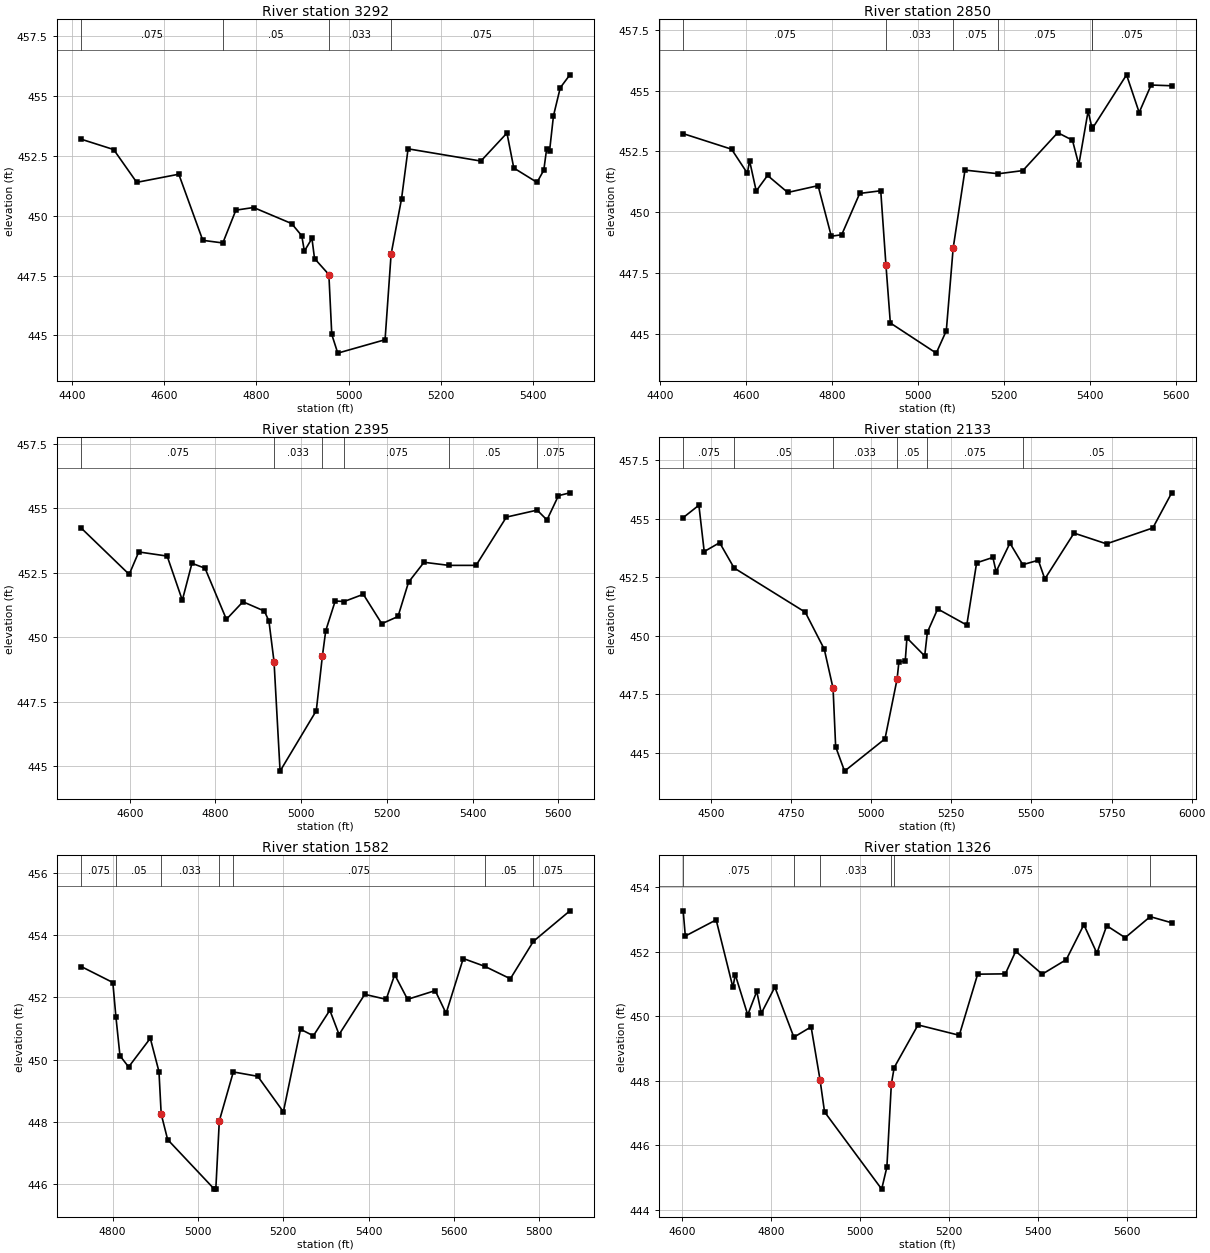
Type RM Length L Ch R = 1,3292,442,442,442
BEGIN DESCRIPTION:
LWE S 066 6.0
END DESCRIPTION:
XS GIS Cut Line= 4
      2439992.27      7040999.98      2440001.40      7040793.78
      2439858.87      7040522.85      2439412.90      7040205.84
#Sta/Elev= 30
  4420.5  453.19  4490.6  452.76  4540.6  451.39  4631.9  451.73  4683.9  448.97
  4727.4  448.86  4755.7  450.23  4794.1  450.34  4876.6  449.67  4898.6  449.16
  4904.3  448.52  4920.7  449.05  4926.3  448.21  4957.4  447.54  4963.7  445.04
  4976.7  444.26  5079.3  444.82  5092.4  448.39  5115.0  450.70  5129.2  452.79
  5287.2  452.28  5343.7  453.45  5358.5  451.99  5408.9  451.39  5423.6  451.90
  5429.8  452.79  5436.0  452.68  5444.6  454.17  5459.3  455.34  5480.2  455.88
#Mann=4,-1,0
  4420.5   0.075       0  4727.4    0.05       0  4957.4   0.033       0
  5092.4   0.075       0
Bank Sta=4957.4,5092.4
Exp/Cntr=0.3,0.1

Type RM Length L Ch R = 1,2850,455,455,455
BEGIN DESCRIPTION:
LWE S 066 5.0
END DESCRIPTION:
XS GIS Cut Line= 3
      2439997.75      7041005.40      2440101.22      7040576.71
      2440440.53      7039968.10
#Sta/Elev= 30
  4453.1  453.23  4565.8  452.59  4602.6  451.60  4607.7  452.12  4623.2  450.87
  4649.6  451.51  4696.6  450.81  4767.3  451.09  4798.1  449.01  4822.3  449.07
  4864.2  450.77  4913.2  450.88  4925.4  447.81  4935.6  445.44  5042.5  444.20
  5065.9  445.12  5081.9  448.52  5109.4  451.73  5187.2  451.58  5244.2  451.71
  5325.4  453.27  5359.7  452.96  5374.5  451.95  5396.2  454.16  5404.8  453.49
  5406.0  453.44  5485.7  455.65  5515.1  454.10  5542.9  455.23  5590.9  455.20
#Mann=6,-1,0
  4453.1   0.075       0  4925.4   0.033       0  5081.9   0.075       0
  5187.2   0.075       0  5404.8    0.05       0  5406.0   0.075       0
Bank Sta=4925.4,5081.9
Exp/Cntr=0.3,0.1

Type RM Length L Ch R = 1,2395,262,262,262
BEGIN DESCRIPTION:
LWE S 066 4.6
END DESCRIPTION:
XS GIS Cut Line= 3
      2440289.72      7041169.11      2440569.76      7040630.56
      2440652.52      7040103.63
#Sta/Elev= 30
  4486.9  454.23  4598.6  452.44  4620.9  453.31  4687.2  453.15  4722.6  451.44
  4745.1  452.87  4775.6  452.68  4825.5  450.70  4864.1  451.38  4914.2  451.02
  4924.8  450.63  4936.7  449.06  4950.8  444.82  5035.3  447.16  5049.5  449.27
  5057.4  450.26  5079.5  451.41  5100.4  451.39  5145.1  451.67  5188.2  450.53
  5226.1  450.81  5250.7  452.14  5286.8  452.91  5344.6  452.79  5408.3  452.79
  5479.1  454.66  5550.8  454.93  5573.8  454.55  5600.6  455.49  5627.3  455.60
#Mann=6,-1,0
  4486.9   0.075       0  4936.7   0.033       0  5049.5   0.075       0
  5100.4   0.075       0  5344.6    0.05       0  5550.8   0.075       0
Bank Sta=4936.7,5049.5
Exp/Cntr=0.3,0.1

Type RM Length L Ch R = 1,2133,551,551,551
BEGIN DESCRIPTION:
LWE S 066 4.4
END DESCRIPTION:
XS GIS Cut Line= 4
      2440488.97      7041395.33      2440634.39      7041039.87
      2440782.13      7040776.26      2440913.62      7039949.09
#Sta/Elev= 30
  4414.0  455.05  4463.0  455.58  4479.6  453.60  4527.7  453.98  4572.8  452.90
  4794.8  451.01  4854.1  449.43  4881.5  447.76  4889.6  445.26  4917.4  444.22
  5043.5  445.60  5081.2  448.15  5086.9  448.89  5106.6  448.92  5111.9  449.91
  5167.3  449.14  5175.6  450.15  5207.8  451.15  5298.6  450.46  5329.3  453.12
  5380.0  453.35  5390.1  452.74  5433.2  453.96  5473.3  453.04  5521.7  453.23
  5542.0  452.43  5633.1  454.39  5734.4  453.93  5878.9  454.61  5937.8  456.11
#Mann=6,-1,0
  4414.0   0.075       0  4572.8    0.05       0  4881.5   0.033       0
  5081.2    0.05       0  5175.6   0.075       0  5473.3    0.05       0
Bank Sta=4881.5,5081.2
Exp/Cntr=0.3,0.1

Type RM Length L Ch R = 1,1582,256,256,256
BEGIN DESCRIPTION:
LWE S 066 4.0
END DESCRIPTION:
XS GIS Cut Line= 4
      2441081.40      7041379.14      2441129.00      7041110.00
      2441123.52      7040925.13      2441179.99      7040240.92
#Sta/Elev= 30
  4726.7  452.99  4800.5  452.48  4807.7  451.38  4817.2  450.13  4837.5  449.77
  4888.3  450.69  4908.6  449.62  4913.8  448.26  4928.9  447.44  5038.3  445.85
  5041.8  445.85  5050.0  448.04  5082.8  449.61  5140.1  449.47  5200.1  448.33
  5240.3  450.98  5270.4  450.77  5309.0  451.59  5330.6  450.81  5390.8  452.10
  5441.0  451.94  5461.0  452.73  5491.1  451.94  5555.9  452.22  5581.4  451.49
  5621.6  453.25  5671.9  453.00  5732.0  452.60  5785.9  453.80  5871.5  454.78
#Mann=7,-1,0
  4726.7   0.075       0  4807.7    0.05       0  4913.8   0.033       0
  5050.0    0.05       0  5082.8   0.075       0  5671.9    0.05       0
  5785.9   0.075       0
Bank Sta=4913.8,5050
Exp/Cntr=0.3,0.1

Type RM Length L Ch R = 1,1326,209,209,209
BEGIN DESCRIPTION:
LWE S 066 3.2
END DESCRIPTION:
XS GIS Cut Line= 4
      2441323.74      7041503.04      2441382.98      7041174.51
      2441390.37      7040965.30      2441537.57      7040428.90
#Sta/Elev= 30
  4601.6  453.26  4606.4  452.48  4675.8  452.98  4713.6  450.89  4718.7  451.29
  4746.9  450.04  4767.2  450.77  4777.4  450.09  4807.9  450.90  4850.7  449.35
  4889.5  449.67  4909.5  448.04  4919.7  447.04  5048.3  444.65  5060.0  445.33
  5070.0  447.89  5076.4  448.41  5130.1  449.73  5222.9  449.41  5264.3  451.30
  5326.6  451.31  5350.0  452.01  5409.5  451.30  5463.7  451.75  5503.3  452.83
  5532.6  451.95  5554.7  452.80  5596.2  452.43  5652.6  453.08  5701.0  452.89
#Mann=6,-1,0
  4601.6   0.075       0  4850.7    0.05       0  4909.5   0.033       0
  5070.0    0.05       0  5076.4   0.075       0  5652.6    0.05       0
Bank Sta=4909.5,5070
Exp/Cntr=0.3,0.1

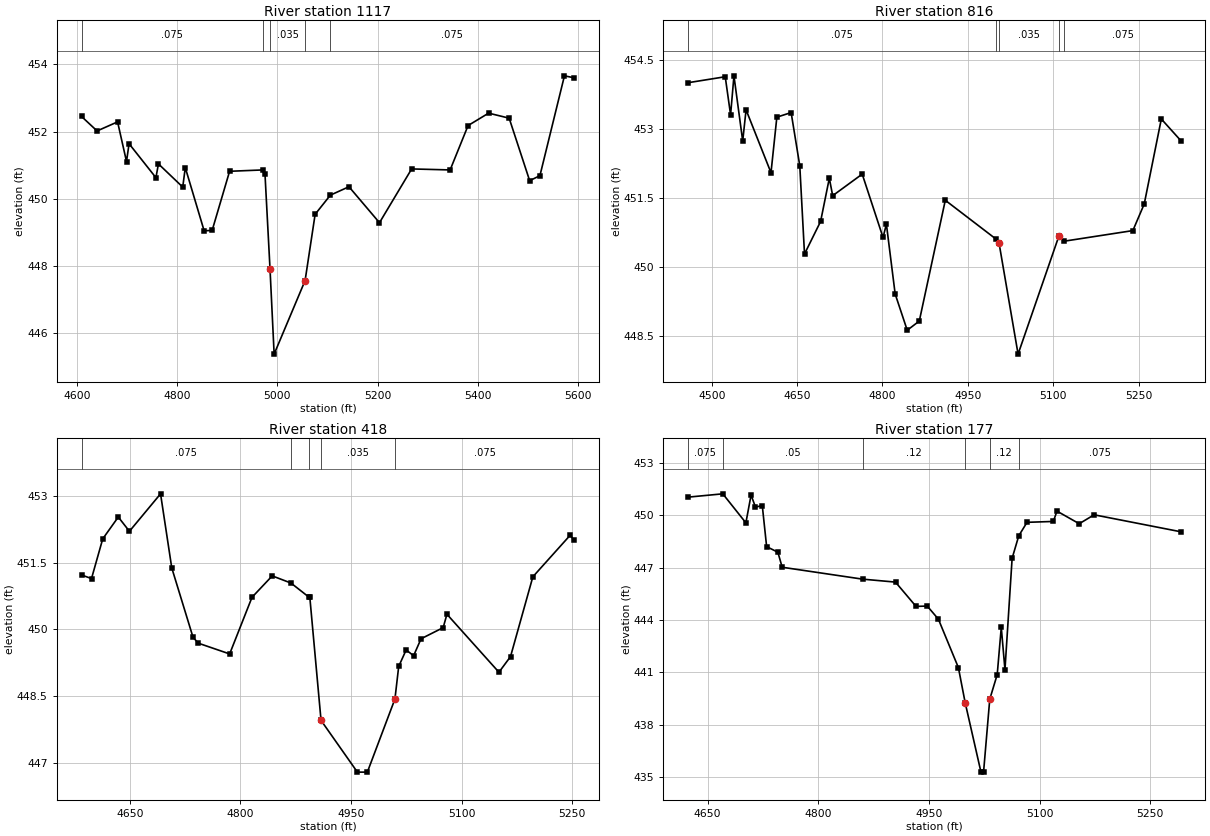
Type RM Length L Ch R = 1,1117,301,301,301
BEGIN DESCRIPTION:
LWE S 066 3.0
END DESCRIPTION:
XS GIS Cut Line= 4
      2441517.62      7041540.73      2441576.87      7041212.21
      2441584.62      7040992.56      2441677.65      7040573.06
#Sta/Elev= 30
  4609.3  452.45  4640.3  452.02  4681.2  452.29  4699.0  451.11  4704.1  451.64
  4757.7  450.63  4762.7  451.04  4811.2  450.35  4816.3  450.93  4853.9  449.05
  4869.9  449.06  4904.7  450.82  4970.9  450.86  4975.3  450.75  4985.4  447.91
  4993.6  445.38  5055.4  447.57  5075.4  449.54  5105.8  450.11  5142.9  450.36
  5203.8  449.29  5268.0  450.89  5344.8  450.86  5380.6  452.18  5421.6  452.55
  5462.6  452.40  5503.5  450.54  5524.0  450.69  5572.9  453.66  5592.6  453.60
#Mann=5,-1,0
  4609.3   0.075       0  4970.9    0.05       0  4985.4   0.035       0
  5055.4    0.05       0  5105.8   0.075       0
Bank Sta=4985.4,5055.4
Exp/Cntr=0.3,0.1

Type RM Length L Ch R = 1,816,398,398,398
BEGIN DESCRIPTION:
LWE S 066 2.0
END DESCRIPTION:
XS GIS Cut Line= 3
      2441571.50      7041653.79      2441879.00      7041160.00
      2441874.14      7040875.85
#Sta/Elev= 30
  4458.3  454.01  4523.7  454.14  4533.1  453.31  4539.0  454.16  4554.4  452.74
  4560.3  453.42  4604.1  452.05  4614.4  453.26  4639.5  453.36  4654.7  452.20
  4663.0  450.28  4691.3  450.99  4706.6  451.93  4712.5  451.55  4764.4  452.02
  4801.0  450.64  4806.9  450.93  4822.3  449.41  4843.5  448.62  4864.7  448.82
  4910.4  451.45  4999.0  450.61  5004.7  450.53  5038.3  448.10  5110.0  450.67
  5119.8  450.56  5240.0  450.79  5260.0  451.37  5290.0  453.22  5324.2  452.75
#Mann=5,-1,0
  4458.3   0.075       0  4999.0    0.05       0  5004.7   0.035       0
  5110.0    0.05       0  5119.8   0.075       0
Bank Sta=5004.7,5110
Exp/Cntr=0.3,0.1

Type RM Length L Ch R = 1,418,241,241,241
BEGIN DESCRIPTION:
LWE S 066 1.0
END DESCRIPTION:
XS GIS Cut Line= 3
      2442066.96      7041486.85      2442279.00      7041160.00
      2442239.38      7040884.34
#Sta/Elev= 30
  4584.6  451.22  4598.1  451.14  4613.3  452.03  4634.4  452.52  4649.5  452.20
  4691.7  453.04  4706.9  451.38  4735.8  449.82  4743.1  449.69  4785.4  449.45
  4815.7  450.72  4843.1  451.20  4868.5  451.04  4892.4  450.73  4894.1  450.72
  4909.3  447.96  4958.6  446.80  4972.1  446.80  5009.5  448.44  5014.6  449.17
  5024.7  449.54  5034.8  449.41  5044.9  449.79  5074.9  450.04  5080.0  450.34
  5150.5  449.04  5166.2  449.39  5196.5  451.18  5247.0  452.11  5252.7  452.00
#Mann=5,-1,0
  4584.6   0.075       0  4868.5    0.05       0  4892.4   0.075       0
  4909.3   0.035       0  5009.5   0.075       0
Bank Sta=4909.3,5009.5
Exp/Cntr=0.3,0.1

Type RM Length L Ch R = 1,177,0,0,0
BEGIN DESCRIPTION:
LWE S 066 0.8
END DESCRIPTION:
XS GIS Cut Line= 3
      2442296.94      7041525.80      2442509.00      7041198.90
      2442469.46      7040923.79
#Sta/Elev= 30
  4623.6  451.03  4670.7  451.22  4702.0  449.56  4709.0  451.15  4715.0  450.46
  4724.2  450.55  4730.1  448.20  4745.3  447.88  4751.2  447.02  4860.0  446.34
  4904.7  446.17  4932.5  444.78  4947.7  444.80  4962.8  444.05  4989.9  441.28
  4999.1  439.27  5020.5  435.30  5024.0  435.30  5032.4  439.47  5042.5  440.88
  5048.0  443.58  5053.0  441.16  5062.7  447.53  5071.7  448.82  5082.9  449.59
  5118.5  449.64  5123.5  450.23  5153.6  449.51  5173.8  450.02  5291.2  449.05
#Mann=6,-1,0
  4623.6   0.075       0  4670.7    0.05       0  4860.0    0.12       0
  4999.1   0.035       0  5032.4    0.12       0  5071.7   0.075       0
Bank Sta=4999.1,5032.4
Exp/Cntr=0.3,0.1

Chan Stop Cuts=-1