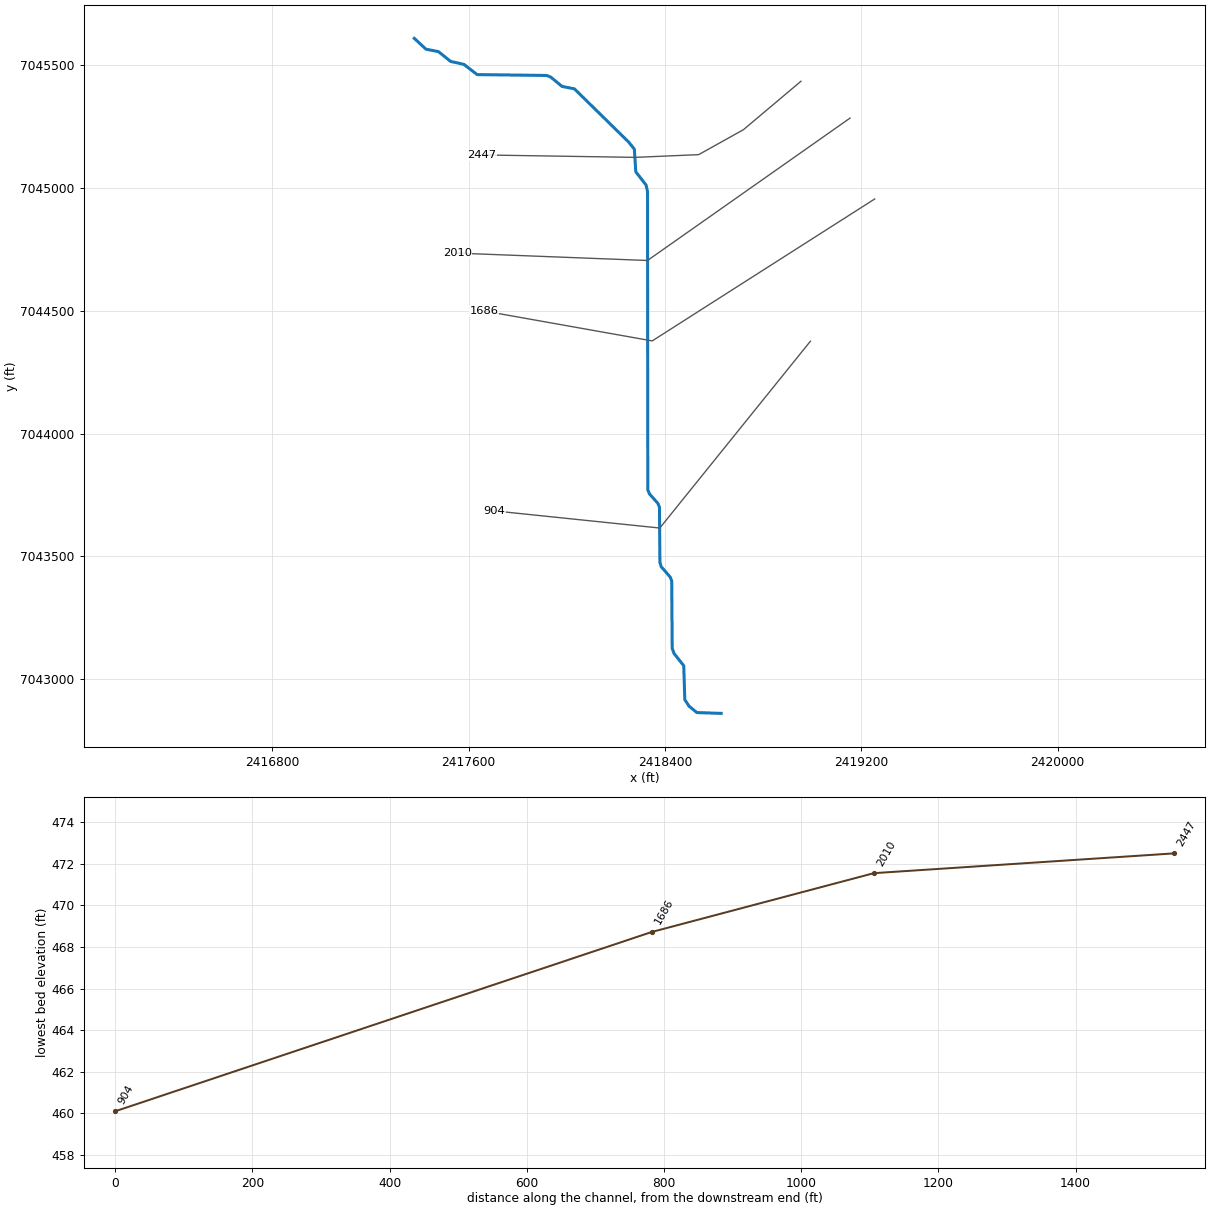
--- LWE S 069.prj (project) ---

Proj Title=LWE S 069 Base Level Engineering
Current Plan=p01
Default Exp/Contr=0.3,0.1
English Units
Geom File=g01
Flow File=f01
Plan File=p01
BEGIN DESCRIPTION:
LWE S 069
END DESCRIPTION:

--- LWE S 069.p01 (plan) ---

Plan Title=Multiple Run
Short Identifier=Multiple
Geom File=g01
Flow File=f01
Subcritical Flow
K Sum by GR= 0
Std Step Tol= 0.01
Critical Tol= 0.01
Num of Std Step Trials= 20
Max Error Tol= 0.3
Flow Tol Ratio= 0.001
Split Flow NTrial= 30
Split Flow Tol= 0.02
Split Flow Ratio= 0.02
Log Output Level= 0
Friction Slope Method= 1
Unsteady Friction Slope Method= 2
Unsteady Bridges Friction Slope Method= 1
Parabolic Critical Depth
Global Vel Dist=  1 , 1 , 1
Global Log Level= 0
CheckData=True
Encroach Param= -1, 0, 0, 0
BEGIN DESCRIPTION:
Multiple Run
END DESCRIPTION:

--- LWE S 069.f01 (steady flow) ---

Flow Title=Multiple
Number of Profiles=7
Profile Names=10-year,25-year,50-year,1pct_min,100-year,1pct_plu,500-year
River Rch & RM= LWE S 069,Reach-1,2447
     615     840    1025     621    1239    2472    1806
Boundary for River Rch & Prof#=LWE S 069,Reach-1,1
Up Type=0
Dn Type=3
Dn Slope=0.005
Boundary for River Rch & Prof#=LWE S 069,Reach-1,2
Up Type=0
Dn Type=3
Dn Slope=0.005
Boundary for River Rch & Prof#=LWE S 069,Reach-1,3
Up Type=0
Dn Type=3
Dn Slope=0.005
Boundary for River Rch & Prof#=LWE S 069,Reach-1,4
Up Type=0
Dn Type=3
Dn Slope=0.005
Boundary for River Rch & Prof#=LWE S 069,Reach-1,5
Up Type=0
Dn Type=3
Dn Slope=0.005
Boundary for River Rch & Prof#=LWE S 069,Reach-1,6
Up Type=0
Dn Type=3
Dn Slope=0.005
Boundary for River Rch & Prof#=LWE S 069,Reach-1,7
Up Type=0
Dn Type=3
Dn Slope=0.005

--- LWE S 069.g01 (geometry) ---

Geom Title=Existing Conditions

River Reach=LWE S 069,Reach-1
Reach XY= 30
      2417379.00      7045610.00      2417426.64      7045565.67
      2417477.33      7045555.96      2417526.80      7045516.07
      2417581.18      7045503.88      2417634.93      7045462.24
      2417918.50      7045458.80      2417935.08      7045451.91
      2417980.75      7045414.22      2418031.30      7045404.17
      2418252.82      7045186.87      2418275.39      7045158.50
      2418281.36      7045065.98      2418323.26      7045012.34
      2418329.20      7044985.08      2418330.22      7043770.50
      2418337.14      7043753.94      2418370.86      7043716.06
      2418377.78      7043699.50      2418379.52      7043475.22
      2418384.75      7043457.67      2418420.86      7043416.06
      2418427.78      7043399.50      2418429.52      7043125.22
      2418437.14      7043103.94      2418476.73      7043054.06
      2418480.97      7042915.65      2418498.37      7042889.35
      2418530.11      7042863.26      2418629.00      7042860.00

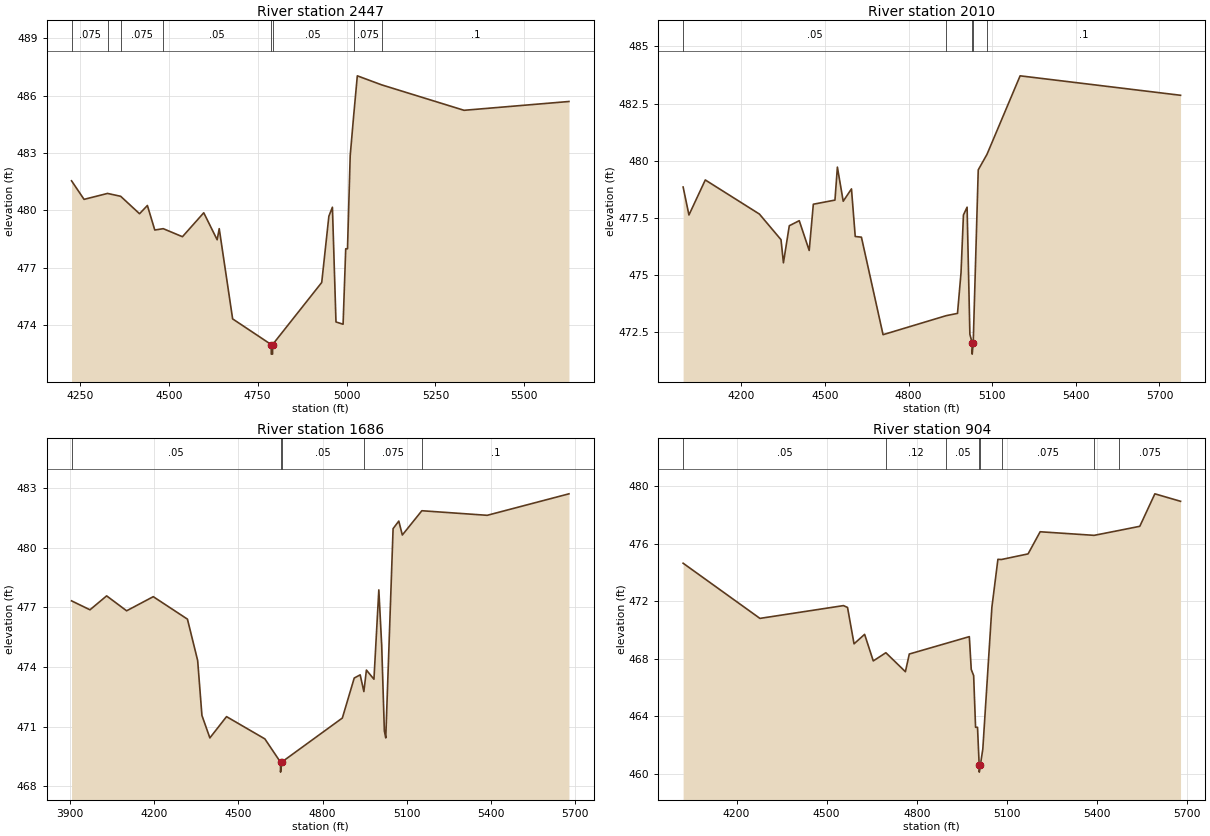
Type RM Length L Ch R = 1,2447,437,437,437
BEGIN DESCRIPTION:
LWE S 069 6.0
END DESCRIPTION:
XS GIS Cut Line= 5
      2418954.01      7045435.01      2418719.71      7045237.76
      2418537.42      7045136.19      2418279.21      7045125.09
      2417653.99      7045135.00
#Sta/Elev= 30
  4226.6  481.55  4261.8  480.58  4327.9  480.89  4364.8  480.74  4417.8  479.83
  4439.9  480.26  4460.7  478.98  4484.4  479.05  4538.5  478.63  4598.4  479.88
  4636.1  478.47  4641.9  479.05  4679.6  474.34  4788.0  473.00  4788.3  472.50
  4791.8  472.50  4792.0  473.00  4930.1  476.24  4950.2  479.70  4960.2  480.17
  4970.2  474.18  4990.2  474.06  4997.6  478.00  5002.6  478.00  5010.2  482.86
  5019.8  484.92  5030.2  487.03  5098.4  486.56  5330.3  485.23  5625.3  485.69
#Mann=8,-1,0
  4226.6   0.075       0  4327.9    0.05       0  4364.8   0.075       0
  4484.4    0.05       0  4788.0    0.05       0  4792.0    0.05       0
  5019.8   0.075       0  5098.4     0.1       0
Bank Sta=4788,4792
Exp/Cntr=0.3,0.1

Type RM Length L Ch R = 1,2010,324,324,324
BEGIN DESCRIPTION:
LWE S 069 5.0
END DESCRIPTION:
XS GIS Cut Line= 3
      2419154.02      7045285.01      2418329.01      7044704.99
      2417553.99      7044735.00
#Sta/Elev= 30
  3991.5  478.85  4012.4  477.63  4071.0  479.16  4265.1  477.67  4342.6  476.55
  4351.3  475.54  4372.3  477.16  4408.0  477.38  4443.7  476.08  4458.5  478.10
  4536.1  478.28  4544.8  479.72  4565.7  478.23  4595.3  478.77  4608.8  476.69
  4631.0  476.66  4708.6  472.40  4934.9  473.23  4975.6  473.33  4988.2  475.10
  4996.9  477.63  5010.0  477.97  5020.0  472.42  5028.0  472.05  5028.3  471.55
  5032.0  472.05  5050.0  479.60  5081.4  480.28  5200.2  483.71  5775.6  482.86
#Mann=5,-1,0
  3991.5    0.05       0  4934.9   0.075       0  5028.0    0.07       0
  5032.0   0.075       0  5081.4     0.1       0
Bank Sta=5028,5032
Exp/Cntr=0.3,0.1

Type RM Length L Ch R = 1,1686,782,782,782
BEGIN DESCRIPTION:
Mapping XS 37ed58aa
END DESCRIPTION:
XS GIS Cut Line= 3
      2419254.40      7044955.46      2418348.19      7044377.36
      2417662.38      7044499.45
#Sta/Elev= 30
  3905.6  477.33  3971.3  476.88  4030.6  477.58  4101.8  476.83  4196.7  477.54
  4318.4  476.41  4354.8  474.33  4370.0  471.57  4398.3  470.44  4457.6  471.51
  4594.2  470.39  4649.8  469.22  4650.0  468.72  4653.8  469.22  4870.1  471.44
  4912.4  473.45  4933.6  473.61  4946.7  472.77  4955.8  473.85  4982.6  473.39
  5000.0  477.88  5010.2  475.10  5019.7  470.79  5024.7  470.44  5050.8  480.96
  5071.1  481.34  5083.7  480.64  5153.2  481.86  5386.0  481.63  5677.1  482.71
#Mann=5,-1,0
  3905.6    0.05       0  4649.8    0.07       0  4653.8    0.05       0
  4946.7   0.075       0  5153.2     0.1       0
Bank Sta=4649.8,4653.8
Exp/Cntr=0.3,0.1

Type RM Length L Ch R = 1,904,0,0,0
BEGIN DESCRIPTION:
LWE S 069 3.0
END DESCRIPTION:
XS GIS Cut Line= 3
      2418992.80      7044376.25      2418379.09      7043615.04
      2417704.00      7043685.00
#Sta/Elev= 30
  4022.2  474.64  4278.0  470.80  4556.2  471.69  4569.7  471.56  4591.4  469.03
  4626.6  469.69  4655.4  467.84  4697.4  468.41  4762.4  467.09  4775.4  468.32
  4897.8  469.06  4975.3  469.53  4981.7  467.25  4989.7  466.82  4996.1  463.22
  5002.6  463.22  5008.1  460.60  5008.4  460.10  5012.1  460.60  5020.2  461.70
  5050.4  471.57  5070.5  474.91  5082.6  474.90  5171.0  475.29  5211.2  476.83
  5390.9  476.58  5473.7  476.92  5543.0  477.21  5593.2  479.47  5678.7  478.95
#Mann=8,-1,0
  4022.2    0.05       0  4697.4    0.12       0  4897.8    0.05       0
  5008.1    0.05       0  5012.1    0.05       0  5082.6   0.075       0
  5390.9     0.1       0  5473.7   0.075       0
Bank Sta=5008.1,5012.1
Exp/Cntr=0.3,0.1

Chan Stop Cuts=-1