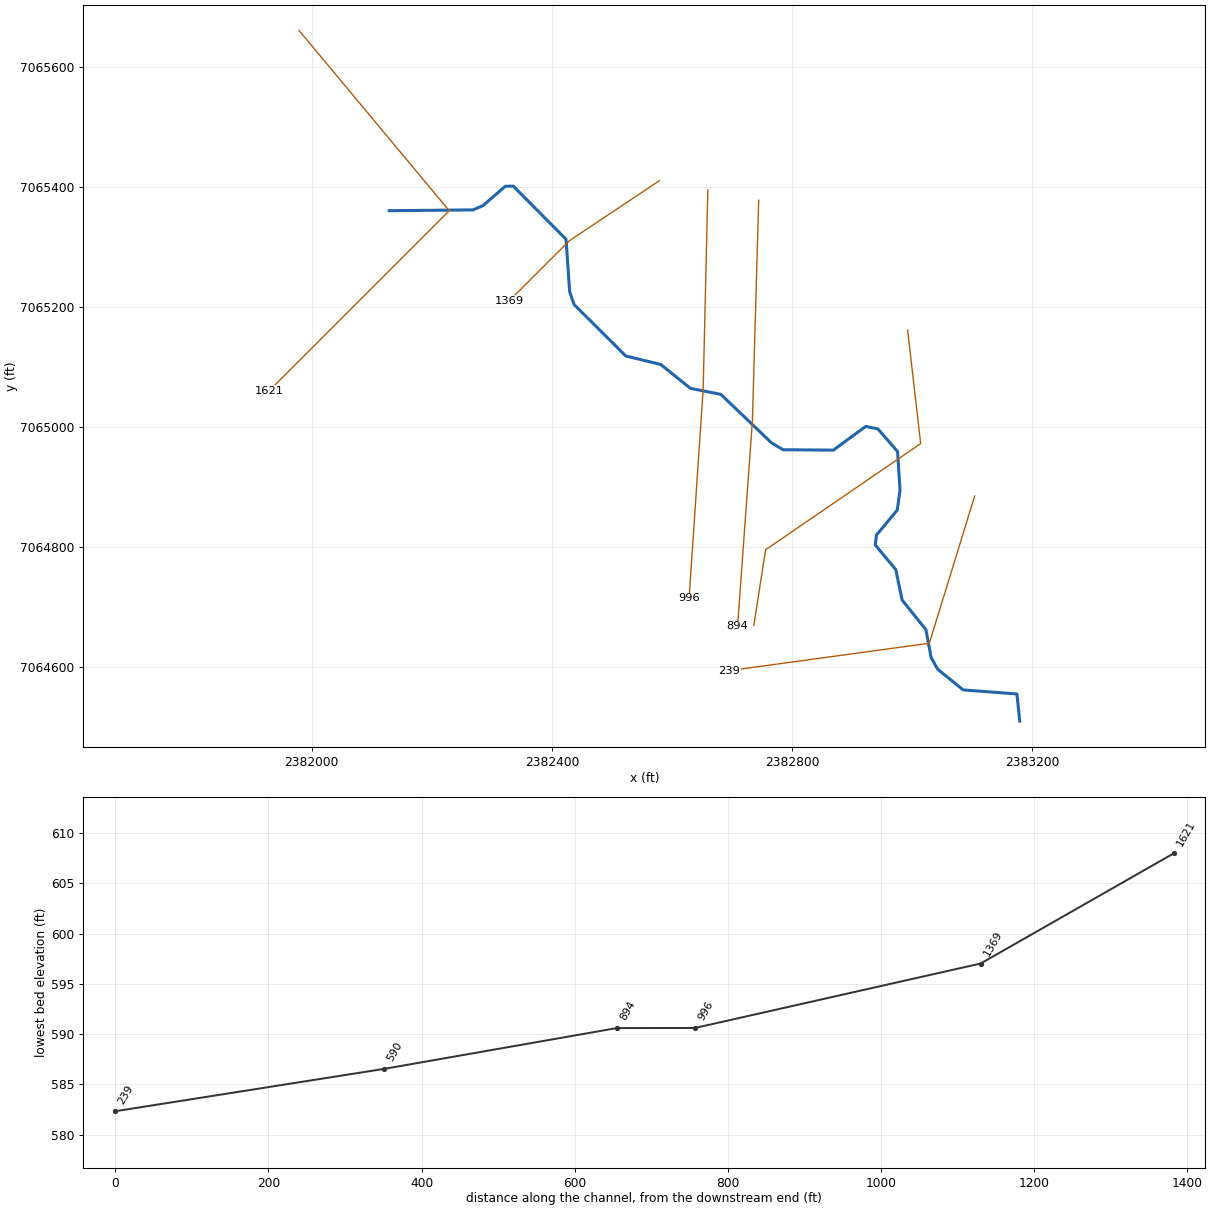
--- LWE S 073.prj (project) ---

Proj Title=LWE S 073 Base Level Engineering
Current Plan=p01
Default Exp/Contr=0.3,0.1
English Units
Geom File=g01
Flow File=f01
Plan File=p01
Y Axis Title=Elevation
X Axis Title(PF)=Main Channel Distance
X Axis Title(XS)=Station
BEGIN DESCRIPTION:
LWE S 073
END DESCRIPTION:
DSS Export Rating Curves= 0
DSS Export Rating Curve Sorted= 0
DSS Export Volume Flow Curves= 0
DXF OffsetX= 0
DXF OffsetY= 0
DXF ScaleX= 1
DXF ScaleY= 10

--- LWE S 073.p01 (plan) ---

Plan Title=Multiple Run
Short Identifier=Multiple
Geom File=g01
Flow File=f01
Subcritical Flow
K Sum by GR= 0
Std Step Tol= 0.01
Critical Tol= 0.01
Num of Std Step Trials= 20
Max Error Tol= 0.3
Flow Tol Ratio= 0.001
Split Flow NTrial= 30
Split Flow Tol= 0.02
Split Flow Ratio= 0.02
Log Output Level= 0
Friction Slope Method= 1
Unsteady Friction Slope Method= 2
Unsteady Bridges Friction Slope Method= 1
Parabolic Critical Depth
Global Vel Dist=  1 , 1 , 1
Global Log Level= 0
CheckData=True
Encroach Param= -1, 0, 0, 0
BEGIN DESCRIPTION:
Multiple Run
END DESCRIPTION:

--- LWE S 073.f01 (steady flow) ---

Flow Title=Multiple
Program Version=4.10
Number of Profiles= 7
Profile Names=10-year,25-year,50-year,1pct_min,100-year,1pct_plu,500-year
River Rch & RM=LWE S 073,Reach-1         ,1621
     200     255     297     173     346     690     467
Boundary for River Rch & Prof#=LWE S 073,Reach-1         , 1
Up Type= 0
Dn Type= 3
Dn Slope=0.0129
Boundary for River Rch & Prof#=LWE S 073,Reach-1         , 2
Up Type= 0
Dn Type= 3
Dn Slope=0.0129
Boundary for River Rch & Prof#=LWE S 073,Reach-1         , 3
Up Type= 0
Dn Type= 3
Dn Slope=0.0129
Boundary for River Rch & Prof#=LWE S 073,Reach-1         , 4
Up Type= 0
Dn Type= 3
Dn Slope=0.0129
Boundary for River Rch & Prof#=LWE S 073,Reach-1         , 5
Up Type= 0
Dn Type= 3
Dn Slope=0.0129
Boundary for River Rch & Prof#=LWE S 073,Reach-1         , 6
Up Type= 0
Dn Type= 3
Dn Slope=0.0129
Boundary for River Rch & Prof#=LWE S 073,Reach-1         , 7
Up Type= 0
Dn Type= 3
Dn Slope=0.0129
DSS Import GetInterval= 0
DSS Import GetPeak= 0
DSS Import FillOption= 0

--- LWE S 073.g01 (geometry) ---

Geom Title=Existing Conditions

River Reach=LWE S 073,Reach-1
Reach XY= 30
      2382129.00      7065360.00      2382268.59      7065361.35
      2382285.20      7065368.47      2382322.48      7065400.73
      2382335.76      7065400.88      2382423.48      7065312.46
      2382429.52      7065225.21      2382436.86      7065203.81
      2382522.93      7065118.13      2382581.19      7065103.90
      2382630.73      7065064.19      2382681.29      7065054.15
      2382765.71      7064973.36      2382784.90      7064961.98
      2382868.52      7064961.27      2382922.65      7065000.78
      2382942.81      7064996.64      2382975.54      7064958.98
      2382979.67      7064894.95      2382975.06      7064861.51
      2382940.46      7064819.90      2382938.42      7064803.38
      2382972.61      7064762.29      2382983.13      7064711.73
      2383022.88      7064662.16      2383031.42      7064615.83
      2383042.45      7064596.37      2383084.74      7064562.02
      2383174.32      7064555.25      2383179.00      7064510.00

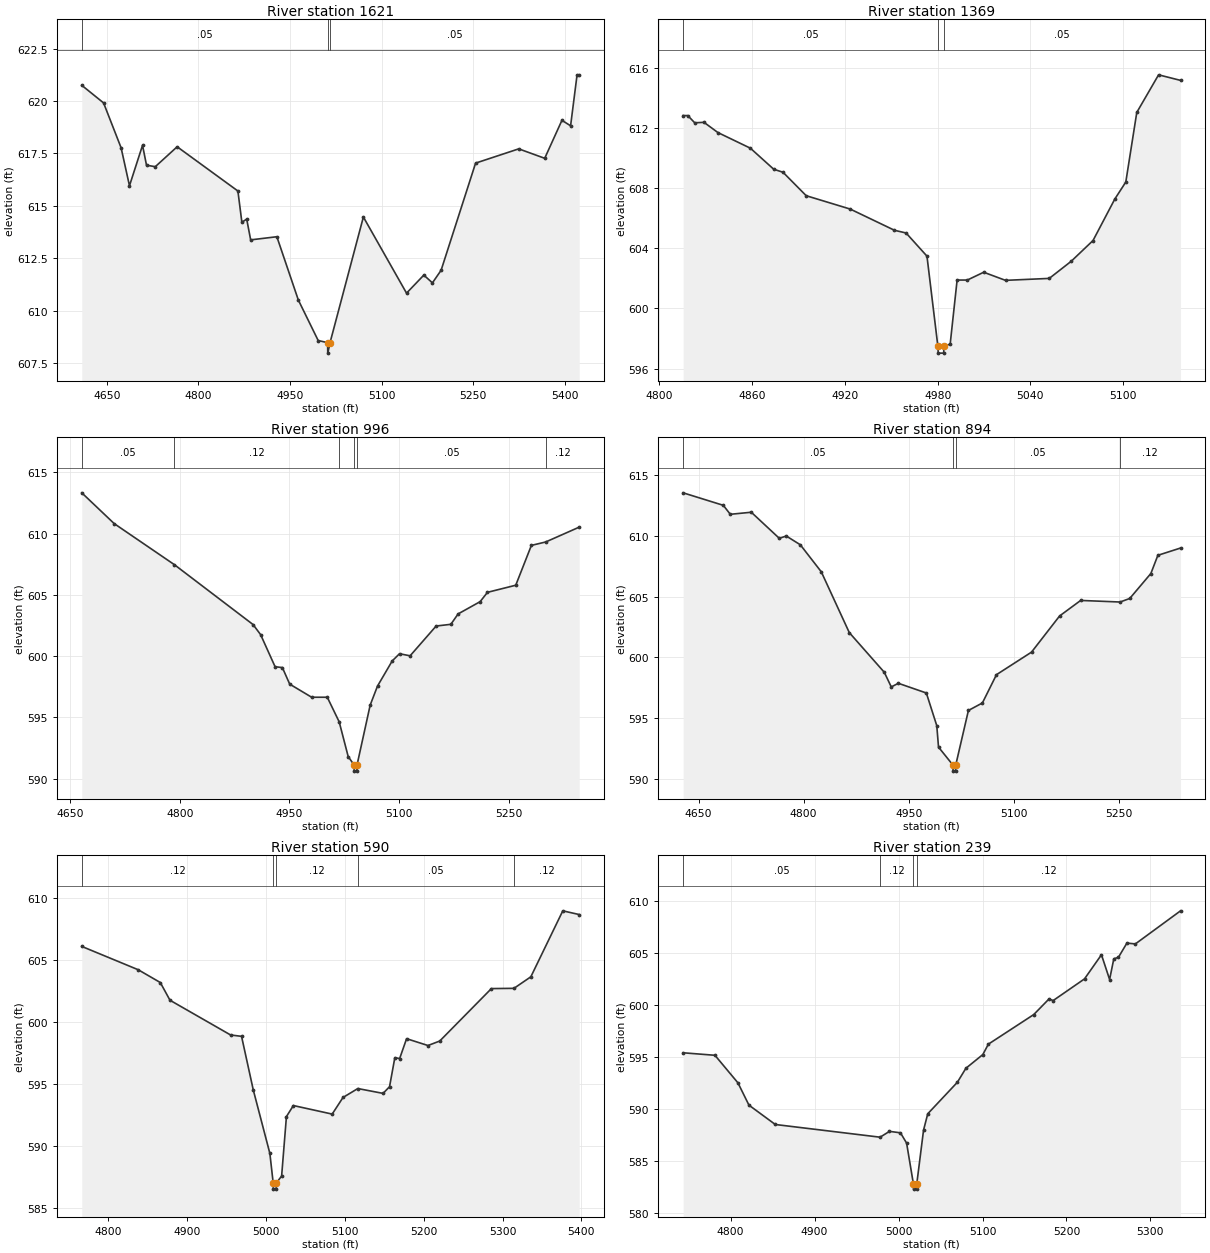
Type RM Length L Ch R = 1,1621,252,252,252
BEGIN DESCRIPTION:
LWE S 073 5.0
END DESCRIPTION:
XS GIS Cut Line= 3
      2381979.03      7065659.96      2382229.00      7065360.00
      2381929.02      7065060.02
#Sta/Elev= 30
  4608.9  620.75  4644.6  619.91  4673.3  617.77  4687.0  615.96  4708.4  617.89
  4714.9  616.94  4729.3  616.87  4765.1  617.82  4864.6  615.71  4871.1  614.22
  4879.0  614.37  4885.5  613.38  4928.4  613.53  4963.6  610.51  4996.1  608.58
  5011.5  608.48  5011.8  607.98  5015.5  608.48  5070.1  614.47  5140.8  610.84
  5169.1  611.70  5183.2  611.33  5197.4  611.93  5253.9  617.04  5324.6  617.72
  5367.1  617.27  5395.3  619.08  5409.5  618.82  5420.1  621.25  5423.6  621.25
#Mann=3,-1,0
  4608.9    0.05       0  5011.5    0.05       0  5015.5    0.05       0
Bank Sta=5011.5,5015.5
Exp/Cntr=0.3,0.1

Type RM Length L Ch R = 1,1369,373,373,373
BEGIN DESCRIPTION:
LWE S 073 4.0
END DESCRIPTION:
XS GIS Cut Line= 3
      2382578.97      7065409.98      2382429.00      7065310.00
      2382328.98      7065209.98
#Sta/Elev= 30
  4815.4  612.83  4818.4  612.83  4822.9  612.35  4828.9  612.38  4837.9  611.70
  4858.9  610.66  4874.0  609.26  4880.0  609.06  4895.0  607.50  4923.5  606.61
  4952.1  605.20  4959.6  605.02  4973.1  603.48  4980.1  597.53  4980.4  597.03
  4983.9  597.03  4984.1  597.53  4988.1  597.62  4992.6  601.89  4999.2  601.89
  5009.8  602.41  5023.9  601.87  5052.2  602.00  5066.4  603.14  5080.5  604.52
  5094.6  607.28  5101.7  608.41  5108.8  613.04  5122.9  615.54  5137.1  615.17
#Mann=3,-1,0
  4815.4    0.05       0  4980.1   0.033       0  4984.1    0.05       0
Bank Sta=4980.1,4984.1
Exp/Cntr=0.3,0.1

Type RM Length L Ch R = 1,996,102,102,102
BEGIN DESCRIPTION:
Mapping XS a1dcdd03
END DESCRIPTION:
XS GIS Cut Line= 3
      2382659.64      7065394.28      2382651.83      7065062.22
      2382628.40      7064714.76
#Sta/Elev= 30
  4665.9  613.33  4710.2  610.82  4792.5  607.47  4900.2  602.58  4910.5  601.76
  4930.3  599.14  4940.3  599.07  4950.3  597.72  4980.3  596.65  5001.7  596.65
  5018.0  594.64  5030.3  591.81  5038.4  591.12  5038.6  590.62  5042.1  590.62
  5042.4  591.12  5060.4  596.01  5070.4  597.56  5090.5  599.61  5100.5  600.20
  5115.0  600.03  5150.6  602.46  5170.7  602.60  5180.7  603.45  5210.8  604.45
  5220.8  605.21  5259.5  605.79  5280.9  609.04  5300.5  609.32  5346.3  610.53
#Mann=6,-1,0
  4665.9    0.05       0  4792.5    0.12       0  5018.0    0.05       0
  5038.4    0.07       0  5042.4    0.05       0  5300.5    0.12       0
Bank Sta=5038.4,5042.4
Exp/Cntr=0.3,0.1

Type RM Length L Ch R = 1,894,304,304,304
BEGIN DESCRIPTION:
Mapping XS a18eb64c
END DESCRIPTION:
XS GIS Cut Line= 3
      2382744.28      7065377.33      2382733.86      7065010.14
      2382709.12      7064667.67
#Sta/Elev= 30
  4627.8  613.55  4685.2  612.52  4695.2  611.78  4725.2  611.95  4765.2  609.80
  4775.2  609.99  4795.2  609.27  4825.2  607.04  4865.2  602.03  4915.2  598.76
  4925.2  597.55  4935.3  597.85  4975.3  597.05  4990.2  594.36  4992.7  592.59
  5013.3  591.11  5013.6  590.61  5017.1  590.61  5017.3  591.11  5035.4  595.61
  5055.4  596.23  5075.5  598.56  5125.6  600.42  5165.7  603.40  5195.8  604.68
  5252.1  604.55  5265.9  604.84  5296.1  606.90  5306.1  608.40  5338.5  609.00
#Mann=4,-1,0
  4627.8    0.05       0  5013.3    0.05       0  5017.3    0.05       0
  5252.1    0.12       0
Bank Sta=5013.3,5017.3
Exp/Cntr=0.3,0.1

Type RM Length L Ch R = 1,590,351,351,351
BEGIN DESCRIPTION:
Mapping XS 91a91b43
END DESCRIPTION:
XS GIS Cut Line= 4
      2382992.32      7065161.04      2383014.02      7064972.21
      2382755.78      7064795.34      2382736.24      7064669.43
#Sta/Elev= 30
  4766.7  606.12  4838.2  604.24  4866.2  603.21  4878.5  601.78  4955.3  598.98
  4969.2  598.87  4984.1  594.54  5005.1  589.43  5009.3  587.05  5009.6  586.55
  5013.1  586.55  5013.3  587.05  5020.0  587.60  5026.1  592.40  5034.9  593.29
  5084.1  592.60  5097.8  593.94  5116.6  594.66  5148.6  594.27  5156.8  594.81
  5163.5  597.15  5169.6  597.08  5178.4  598.68  5205.5  598.13  5220.4  598.49
  5285.9  602.72  5314.5  602.74  5335.9  603.67  5376.4  608.99  5397.2  608.69
#Mann=5,-1,0
  4766.7    0.12       0  5009.3    0.07       0  5013.3    0.12       0
  5116.6    0.05       0  5314.5    0.12       0
Bank Sta=5009.3,5013.3
Exp/Cntr=0.3,0.1

Type RM Length L Ch R = 1,239,0,0,0
BEGIN DESCRIPTION:
LWE S 073 1.0
END DESCRIPTION:
XS GIS Cut Line= 3
      2383103.99      7064884.96      2383028.48      7064639.72
      2382695.68      7064594.17
#Sta/Elev= 30
  4743.4  595.44  4781.3  595.20  4808.7  592.55  4821.8  590.41  4853.2  588.55
  4978.0  587.33  4989.2  587.89  5002.3  587.75  5009.6  586.76  5017.7  582.84
  5017.9  582.34  5021.4  582.34  5021.7  582.84  5029.8  588.02  5034.8  589.58
  5070.1  592.61  5080.2  593.95  5100.4  595.27  5107.0  596.27  5161.0  599.11
  5179.2  600.61  5184.2  600.46  5221.5  602.54  5241.7  604.86  5251.4  602.48
  5256.4  604.47  5261.9  604.61  5272.0  605.98  5282.1  605.90  5335.9  609.08
#Mann=4,-1,0
  4743.4    0.05       0  4978.0    0.12       0  5017.7    0.07       0
  5021.7    0.12       0
Bank Sta=5017.7,5021.7
Exp/Cntr=0.3,0.1

Chan Stop Cuts=-1