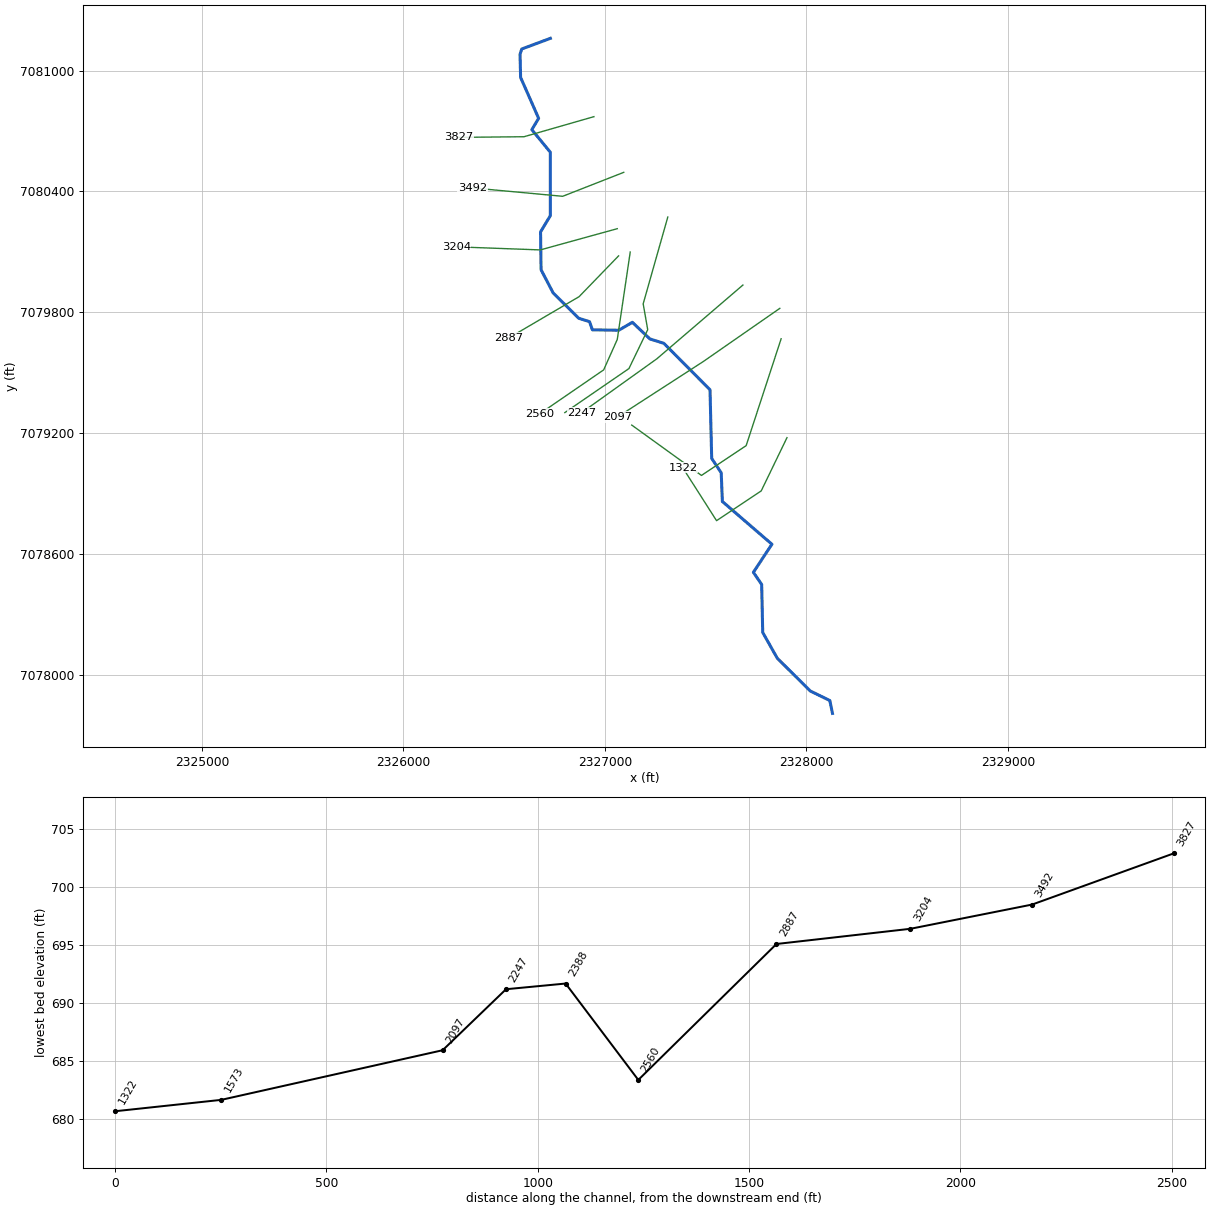
--- LWE S 093.prj (project) ---

Proj Title=LWE S 093 Base Level Engineering
Current Plan=p01
Default Exp/Contr=0.3,0.1
English Units
Geom File=g01
Flow File=f01
Plan File=p01
Y Axis Title=Elevation
X Axis Title(PF)=Main Channel Distance
X Axis Title(XS)=Station
BEGIN DESCRIPTION:
LWE S 093
END DESCRIPTION:
DSS Export Rating Curves= 0
DSS Export Rating Curve Sorted= 0
DSS Export Volume Flow Curves= 0
DXF OffsetX= 0
DXF OffsetY= 0
DXF ScaleX= 1
DXF ScaleY= 10

--- LWE S 093.p01 (plan) ---

Plan Title=Multiple Run
Program Version=4.10
Short Identifier=Multiple
Geom File=g01
Flow File=f01
Subcritical Flow
K Sum by GR= 0
Std Step Tol= 0.01
Critical Tol= 0.01
Num of Std Step Trials= 20
Max Error Tol= 0.3
Flow Tol Ratio= 0.001
Split Flow NTrial= 30
Split Flow Tol= 0.02
Split Flow Ratio= 0.02
Log Output Level= 0
Friction Slope Method= 1
Unsteady Friction Slope Method= 2
Unsteady Bridges Friction Slope Method= 1
Parabolic Critical Depth
Global Vel Dist= 1 , 1 , 1
Global Log Level= 0
CheckData=True
Encroach Param=-1 ,0,0, 0
BEGIN DESCRIPTION:
Multiple Run
END DESCRIPTION:
Computation Interval=1HOUR
Output Interval=1HOUR
Run HTab= 0
Run UNet= 0
Run PostProcess= 0
Run WQNet= 0
UNET Theta= 1
UNET Theta Warmup= 1
UNET ZTol= 0.02
UNET ZSATol= 0.05
UNET MxIter= 20
UNET MaxInSteps= 0
UNET DtIC= 0
UNET DtMin= 0
UNET MaxCRTS= 20
UNET WFStab= 2
UNET SFStab= 1
UNET WFX= 1
UNET SFX= 1
UNET DSS MLevel= 4
UNET DZMax Abort= 100
UNET Convert EG Bridges= 0
UNET Use Existing IB Tables=-1
UNET Froude Reduction=False
UNET Froude Limit= 1
UNET Froude Power= 10
UNET Time Slicing=0,0, 5
UNET Junction Losses=0
Instantaneous Interval=1HOUR
Write IC File= 0
Write IC File at Sim End=0
Echo Input=False
Echo Parameters=False
Echo Output=False
Write Detailed= 0
WQ AD Non Conservative
WQ ULTIMATE=-1
WQ Max Comp Step=1HOUR
WQ Output Interval=15MIN
WQ Output Selected Increments= 0
WQ Output face flow=0
WQ Output face velocity=0
WQ Output face area=0
WQ Output face dispersion=0
WQ Output cell volume=0
WQ Output cell surface area=0
WQ Output cell continuity=0
WQ Output cumulative cell continuity=0
WQ Output face conc=0
WQ Output face dconc_dx=0
WQ Output face courant=0
WQ Output face peclet=0
WQ Output face adv mass=0
WQ Output face disp mass=0
WQ Output cell mass=0
WQ Output cell source sink temp=0
WQ Output cell source sink nsm=0
WQ Output MaxMinRange=-1
WQ Daily Max Min Mean=-1
WQ Daily Range=0
WQ Daily Time=0
WQ Create Restart=0
WQ Fixed Restart=0
WQ System Summary=0
WQ Use Fixed Temperature=0
Sorting and Armoring Iterations= 10
XS Update Threshold= 0.02
Hydraulics Update Threshold= 0.02
Energy Slope Method= 1
Volume Change Method= 0
XS Weighting Method= 0
Number of US Weighted Cross Sections= 1
Number of DS Weighted Cross Sections= 1
Upstream XS Weight=0.25
Main XS Weight=0.5
Downstream XS Weight=0.25
Number of DS XS's Weighted with US Boundary= 1
Upstream Boundary Weight= 1
Weight of XSs Associated with US Boundary= 0
Number of US XS's Weighted with DS Boundary= 1
Downstream Boundary Weight= 0.5
Weight of XSs Associated with DS Boundary= 0.5
Sediment Output Level= 4
Mass or Volume Output= 0
Output Increment Type= 1
Profile and TS Output Increment= 10
XS Output Flag= 0
XS Output Increment= 10
Disregard all LS=0
Disregard all Conn=0
Disregard all Breaches=0
Disregard all Pumps=0

--- LWE S 093.f01 (steady flow) ---

Flow Title=Multiple
Number of Profiles=7
Profile Names=10-year,25-year,50-year,1pct_min,100-year,1pct_plu,500-year
River Rch & RM= LWE S 093,Reach-1,3827
     186     235     273     158     316     630     421
Boundary for River Rch & Prof#=LWE S 093,Reach-1,1
Up Type=0
Dn Type=3
Dn Slope=0.005
Boundary for River Rch & Prof#=LWE S 093,Reach-1,2
Up Type=0
Dn Type=3
Dn Slope=0.005
Boundary for River Rch & Prof#=LWE S 093,Reach-1,3
Up Type=0
Dn Type=3
Dn Slope=0.005
Boundary for River Rch & Prof#=LWE S 093,Reach-1,4
Up Type=0
Dn Type=3
Dn Slope=0.005
Boundary for River Rch & Prof#=LWE S 093,Reach-1,5
Up Type=0
Dn Type=3
Dn Slope=0.005
Boundary for River Rch & Prof#=LWE S 093,Reach-1,6
Up Type=0
Dn Type=3
Dn Slope=0.005
Boundary for River Rch & Prof#=LWE S 093,Reach-1,7
Up Type=0
Dn Type=3
Dn Slope=0.005

--- LWE S 093.g01 (geometry) ---

Geom Title=Existing Conditions

River Reach=LWE S 093,Reach-1
Reach XY= 30
      2326729.00      7081160.00      2326586.90      7081107.04
      2326578.36      7081080.58      2326581.25      7080965.95
      2326670.71      7080763.22      2326637.01      7080706.67
      2326728.61      7080594.84      2326728.93      7080280.03
      2326680.22      7080199.49      2326682.75      7080011.55
      2326742.62      7079896.78      2326869.57      7079770.84
      2326923.20      7079753.94      2326937.44      7079713.39
      2327068.55      7079711.37      2327135.73      7079750.85
      2327222.95      7079668.20      2327292.21      7079646.37
      2327521.19      7079416.19      2327529.52      7079075.22
      2327576.73      7079004.06      2327582.54      7078861.46
      2327828.45      7078649.37      2327736.33      7078510.10
      2327777.61      7078449.57      2327782.75      7078211.55
      2327855.29      7078083.18      2328019.33      7077920.77
      2328115.73      7077873.78      2328129.00      7077810.00

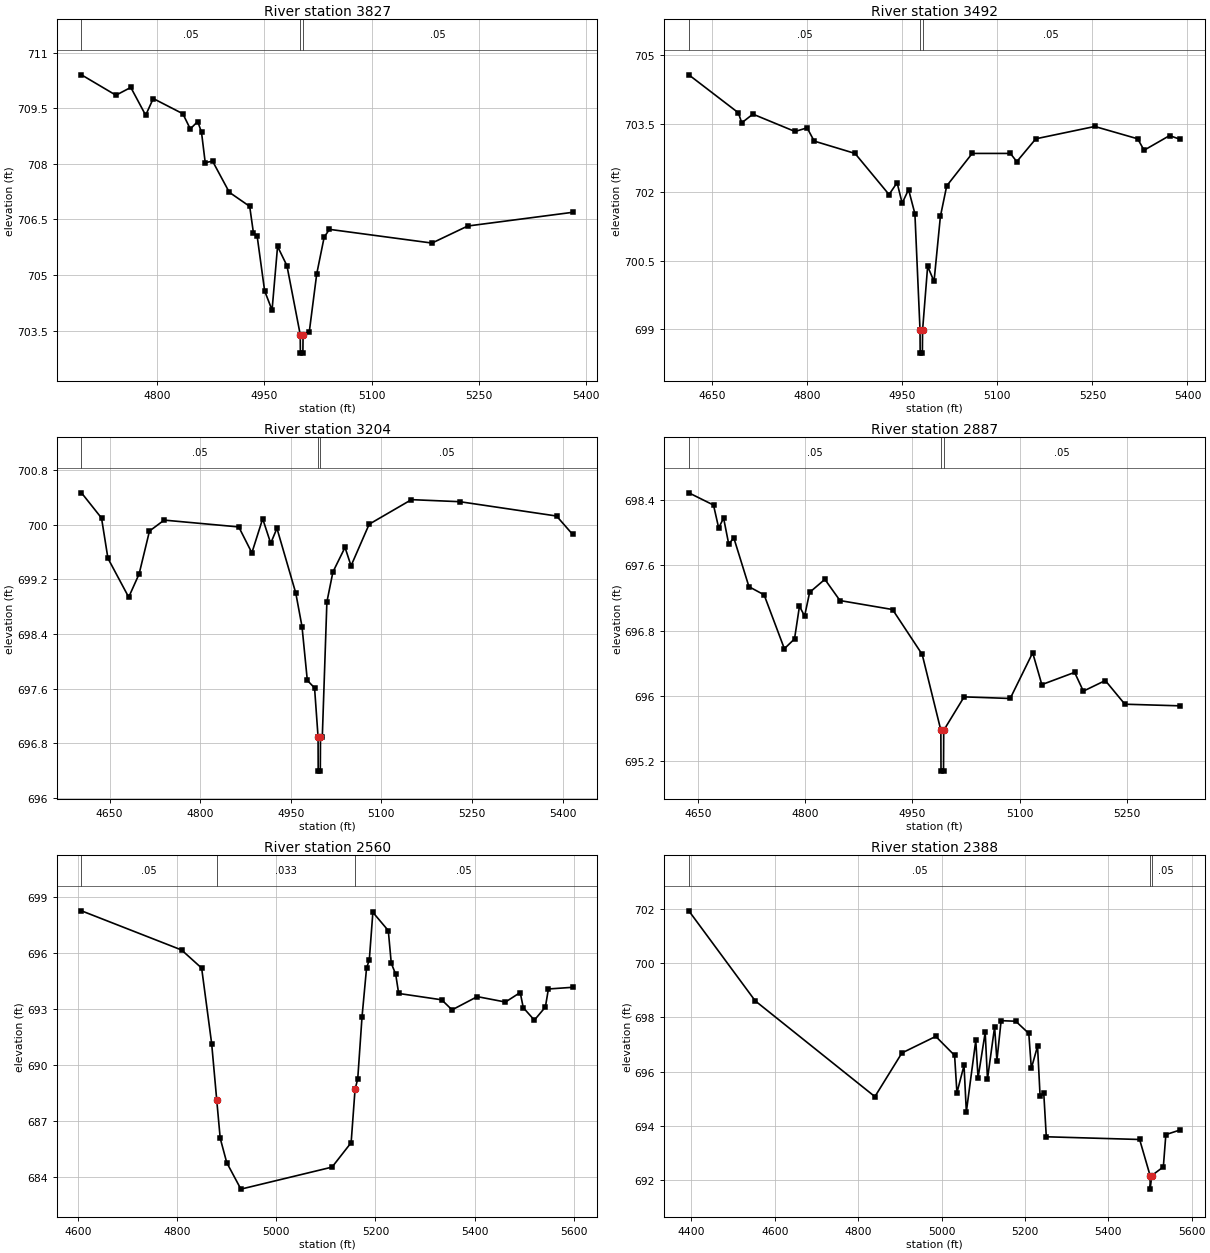
Type RM Length L Ch R = 1,3827,335,335,335
BEGIN DESCRIPTION:
LWE S 093 4.0
END DESCRIPTION:
XS GIS Cut Line= 3
      2326945.28      7080771.34      2326598.20      7080671.72
      2326272.22      7080668.52
#Sta/Elev= 30
  4694.2  710.40  4742.4  709.85  4763.2  710.06  4784.0  709.31  4794.6  709.76
  4836.0  709.35  4846.4  708.94  4856.8  709.14  4862.1  708.85  4867.3  708.03
  4877.6  708.07  4901.0  707.23  4929.5  706.85  4934.7  706.14  4940.0  706.04
  4950.4  704.57  4960.8  704.05  4968.5  705.77  4981.6  705.25  5000.2  703.39
  5000.4  702.89  5003.9  702.89  5004.2  703.39  5012.9  703.47  5023.3  705.03
  5033.7  706.02  5041.1  706.23  5184.5  705.86  5234.5  706.32  5381.3  706.69
#Mann=3,-1,0
  4694.2    0.05       0  5000.2   0.033       0  5004.2    0.05       0
Bank Sta=5000.2,5004.2
Exp/Cntr=0.3,0.1

Type RM Length L Ch R = 1,3492,288,288,288
BEGIN DESCRIPTION:
LWE S 093 3.0
END DESCRIPTION:
XS GIS Cut Line= 3
      2327093.12      7080494.94      2326790.06      7080376.07
      2326342.53      7080417.68
#Sta/Elev= 30
  4613.2  704.57  4691.3  703.74  4696.7  703.52  4714.3  703.71  4780.7  703.33
  4799.8  703.41  4811.0  703.12  4875.4  702.85  4929.1  701.95  4941.8  702.21
  4949.8  701.76  4959.9  702.06  4969.9  701.53  4978.0  698.98  4978.2  698.48
  4981.7  698.48  4982.0  698.98  4990.0  700.38  5000.1  700.05  5010.1  701.47
  5020.1  702.14  5060.3  702.85  5120.6  702.85  5130.6  702.67  5160.7  703.17
  5253.7  703.44  5321.4  703.17  5331.5  702.92  5371.7  703.24  5388.2  703.16
#Mann=3,-1,0
  4613.2    0.05       0  4978.0   0.033       0  4982.0    0.05       0
Bank Sta=4978,4982
Exp/Cntr=0.3,0.1

Type RM Length L Ch R = 1,3204,317,317,317
BEGIN DESCRIPTION:
LWE S 093 2.0
END DESCRIPTION:
XS GIS Cut Line= 3
      2327060.99      7080215.34      2326679.00      7080110.00
      2326262.33      7080125.30
#Sta/Elev= 30
  4603.6  700.47  4636.8  700.10  4647.4  699.51  4681.8  698.94  4699.0  699.28
  4716.2  699.91  4740.5  700.07  4864.0  699.97  4885.7  699.59  4903.6  700.09
  4916.9  699.73  4927.2  699.95  4958.4  699.00  4968.7  698.51  4977.5  697.72
  4989.5  697.61  4995.3  696.89  4995.5  696.39  4999.0  696.39  4999.3  696.89
  5002.3  696.89  5009.9  698.87  5019.9  699.31  5039.9  699.67  5049.9  699.40
  5079.9  700.01  5149.9  700.37  5230.0  700.34  5390.1  700.13  5416.8  699.86
#Mann=3,-1,0
  4603.6    0.05       0  4995.3   0.033       0  4999.3    0.05       0
Bank Sta=4995.3,4999.3
Exp/Cntr=0.3,0.1

Type RM Length L Ch R = 1,2887,327,327,327
BEGIN DESCRIPTION:
LWE S 093 1.8
END DESCRIPTION:
XS GIS Cut Line= 3
      2327067.42      7080080.35      2326871.38      7079877.88
      2326522.50      7079673.04
#Sta/Elev= 30
  4637.5  698.49  4672.0  698.34  4679.2  698.06  4686.1  698.18  4693.3  697.86
  4700.3  697.94  4721.5  697.34  4742.7  697.24  4771.0  696.58  4785.2  696.70
  4792.1  697.10  4799.3  696.98  4806.3  697.27  4827.6  697.43  4848.7  697.17
  4922.2  697.06  4963.6  696.51  4989.7  695.58  4989.9  695.08  4993.4  695.08
  4993.7  695.58  5022.2  695.99  5086.6  695.97  5118.0  696.53  5130.8  696.14
  5176.6  696.29  5188.8  696.06  5219.5  696.19  5246.8  695.90  5323.9  695.88
#Mann=3,-1,0
  4637.5    0.05       0  4989.7   0.033       0  4993.7    0.05       0
Bank Sta=4989.7,4993.7
Exp/Cntr=0.3,0.1

Type RM Length L Ch R = 1,2560,172,172,172
BEGIN DESCRIPTION:
LWE S 093 1.7
END DESCRIPTION:
XS GIS Cut Line= 4
      2327125.28      7080099.61      2327061.00      7079665.77
      2326993.51      7079514.71      2326675.36      7079296.18
#Sta/Elev= 30
  4607.4  698.28  4809.2  696.18  4849.6  695.21  4869.8  691.16  4880.0  688.14
  4887.0  686.09  4900.2  684.78  4928.7  683.36  5112.4  684.54  5150.9  685.85
  5158.8  688.71  5164.2  689.27  5172.8  692.58  5182.0  695.22  5187.5  695.64
  5194.7  698.20  5225.8  697.22  5231.8  695.47  5240.7  694.88  5246.7  693.85
  5333.4  693.51  5354.3  692.97  5405.1  693.68  5461.9  693.39  5491.7  693.90
  5497.8  693.09  5520.2  692.42  5542.4  693.12  5548.5  694.09  5597.4  694.18
#Mann=3,-1,0
  4607.4    0.05       0  4880.0   0.033       0  5158.8    0.05       0
Bank Sta=4880,5158.8
Exp/Cntr=0.3,0.1

Type RM Length L Ch R = 1,2388,141,141,141
BEGIN DESCRIPTION:
LWE S 093 1.6
END DESCRIPTION:
XS GIS Cut Line= 5
      2327311.70      7080273.23      2327189.56      7079842.53
      2327212.06      7079713.98      2327118.85      7079521.14
      2326800.65      7079302.58
#Sta/Elev= 30
  4393.8  701.93  4553.1  698.61  4840.2  695.08  4905.0  696.69  4986.2  697.30
  5031.4  696.60  5037.0  695.22  5054.0  696.23  5059.6  694.52  5082.2  697.15
  5087.7  695.77  5104.8  697.45  5110.3  695.73  5127.4  697.65  5132.9  696.41
  5143.0  697.88  5178.1  697.86  5209.4  697.41  5215.5  696.12  5230.4  696.94
  5236.5  695.10  5245.3  695.21  5251.4  693.60  5475.3  693.50  5500.4  692.17
  5500.6  691.67  5504.4  692.17  5532.2  692.49  5538.2  693.68  5572.2  693.85
#Mann=3,-1,0
  4393.8    0.05       0  5500.4   0.033       0  5504.4    0.05       0
Bank Sta=5500.4,5504.4
Exp/Cntr=0.3,0.1

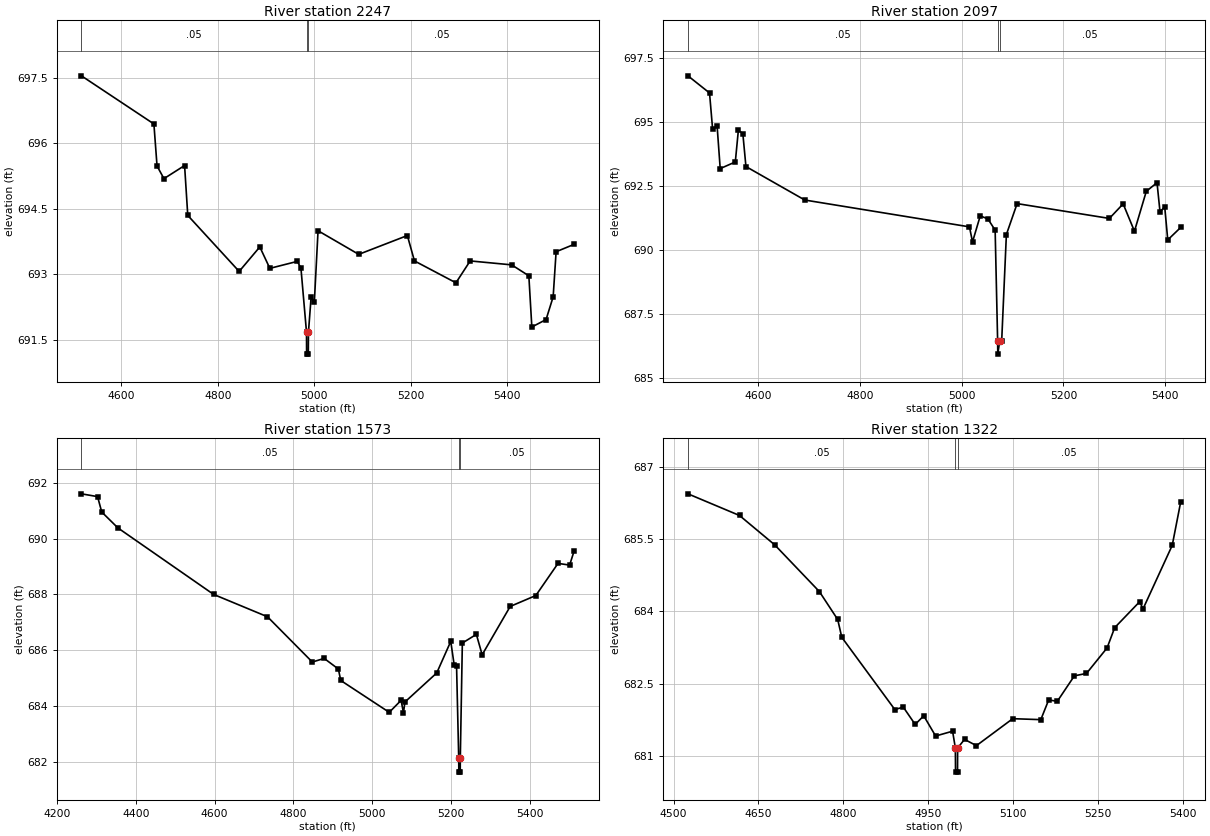
Type RM Length L Ch R = 1,2247,150,150,150
BEGIN DESCRIPTION:
LWE S 093 1.4
END DESCRIPTION:
XS GIS Cut Line= 3
      2327684.49      7079935.73      2327257.05      7079569.35
      2326884.23      7079302.59
#Sta/Elev= 30
  4517.2  697.54  4667.4  696.44  4673.9  695.48  4688.2  695.19  4731.0  695.49
  4737.6  694.35  4844.1  693.07  4886.9  693.63  4907.7  693.14  4964.8  693.30
  4972.2  693.14  4983.7  691.68  4983.9  691.18  4987.4  691.18  4987.7  691.68
  4993.3  692.49  4999.9  692.36  5007.6  694.00  5091.9  693.46  5192.7  693.89
  5207.4  693.31  5293.4  692.81  5322.9  693.31  5408.9  693.22  5444.5  692.97
  5450.7  691.80  5480.2  691.97  5494.9  692.49  5501.0  693.52  5538.6  693.69
#Mann=3,-1,0
  4517.2    0.05       0  4983.7   0.033       0  4987.7    0.05       0
Bank Sta=4983.7,4987.7
Exp/Cntr=0.3,0.1

Type RM Length L Ch R = 1,2097,524,524,524
BEGIN DESCRIPTION:
LWE S 093 1.2
END DESCRIPTION:
XS GIS Cut Line= 3
      2327867.67      7079820.02      2327488.45      7079556.49
      2327062.53      7079281.09
#Sta/Elev= 30
  4461.6  696.81  4504.0  696.14  4510.1  694.72  4518.9  694.85  4525.0  693.18
  4554.7  693.44  4560.7  694.68  4569.5  694.55  4575.6  693.26  4691.3  691.95
  5015.1  690.90  5021.1  690.31  5036.3  691.33  5051.4  691.21  5065.6  690.77
  5070.5  686.42  5070.8  685.92  5074.5  686.42  5078.5  686.45  5087.7  690.60
  5108.8  691.81  5290.2  691.23  5317.3  691.80  5339.5  690.73  5362.8  692.29
  5383.9  692.63  5389.8  691.48  5399.0  691.69  5405.0  690.39  5430.6  690.88
#Mann=3,-1,0
  4461.6    0.05       0  5070.5   0.033       0  5074.5    0.05       0
Bank Sta=5070.5,5074.5
Exp/Cntr=0.3,0.1

Type RM Length L Ch R = 1,1573,251,251,251
BEGIN DESCRIPTION:
LWE S 093 1.0
END DESCRIPTION:
XS GIS Cut Line= 4
      2327874.11      7079668.95      2327700.57      7079138.69
      2327478.81      7078990.85      2327132.86      7079240.70
#Sta/Elev= 30
  4261.7  691.60  4302.7  691.50  4313.2  690.95  4354.3  690.38  4597.3  688.00
  4734.1  687.20  4847.9  685.58  4878.0  685.71  4914.0  685.33  4920.1  684.92
  5043.2  683.78  5073.3  684.21  5079.3  683.76  5083.0  684.15  5163.8  685.19
  5199.4  686.32  5208.0  685.48  5214.1  685.44  5219.6  682.14  5219.9  681.64
  5223.4  681.64  5223.6  682.14  5228.8  686.26  5264.4  686.57  5279.1  685.84
  5350.3  687.57  5415.3  687.96  5471.7  689.11  5501.2  689.05  5512.9  689.57
#Mann=3,-1,0
  4261.7    0.05       0  5219.6   0.035       0  5223.6    0.05       0
Bank Sta=5219.6,5223.6
Exp/Cntr=0.3,0.1

Type RM Length L Ch R = 1,1322,0,0,0
BEGIN DESCRIPTION:
LWE S 093 0.5
END DESCRIPTION:
XS GIS Cut Line= 4
      2327903.11      7079178.18      2327775.41      7078914.15
      2327553.66      7078766.31      2327386.31      7079028.43
#Sta/Elev= 30
  4525.5  686.44  4616.6  685.99  4678.8  685.38  4757.7  684.41  4790.1  683.83
  4797.3  683.46  4891.0  681.96  4906.0  682.01  4927.0  681.65  4942.1  681.83
  4963.1  681.41  4993.1  681.51  4998.0  681.16  4998.3  680.66  5001.8  680.66
  5002.0  681.16  5014.2  681.34  5035.2  681.21  5099.4  681.77  5149.0  681.75
  5162.9  682.16  5178.1  682.13  5208.3  682.66  5229.7  682.71  5266.1  683.24
  5279.5  683.66  5323.7  684.20  5329.6  684.05  5381.2  685.37  5396.3  686.28
#Mann=3,-1,0
  4525.5    0.05       0  4998.0   0.035       0  5002.0    0.05       0
Bank Sta=4998,5002
Exp/Cntr=0.3,0.1

Chan Stop Cuts=-1