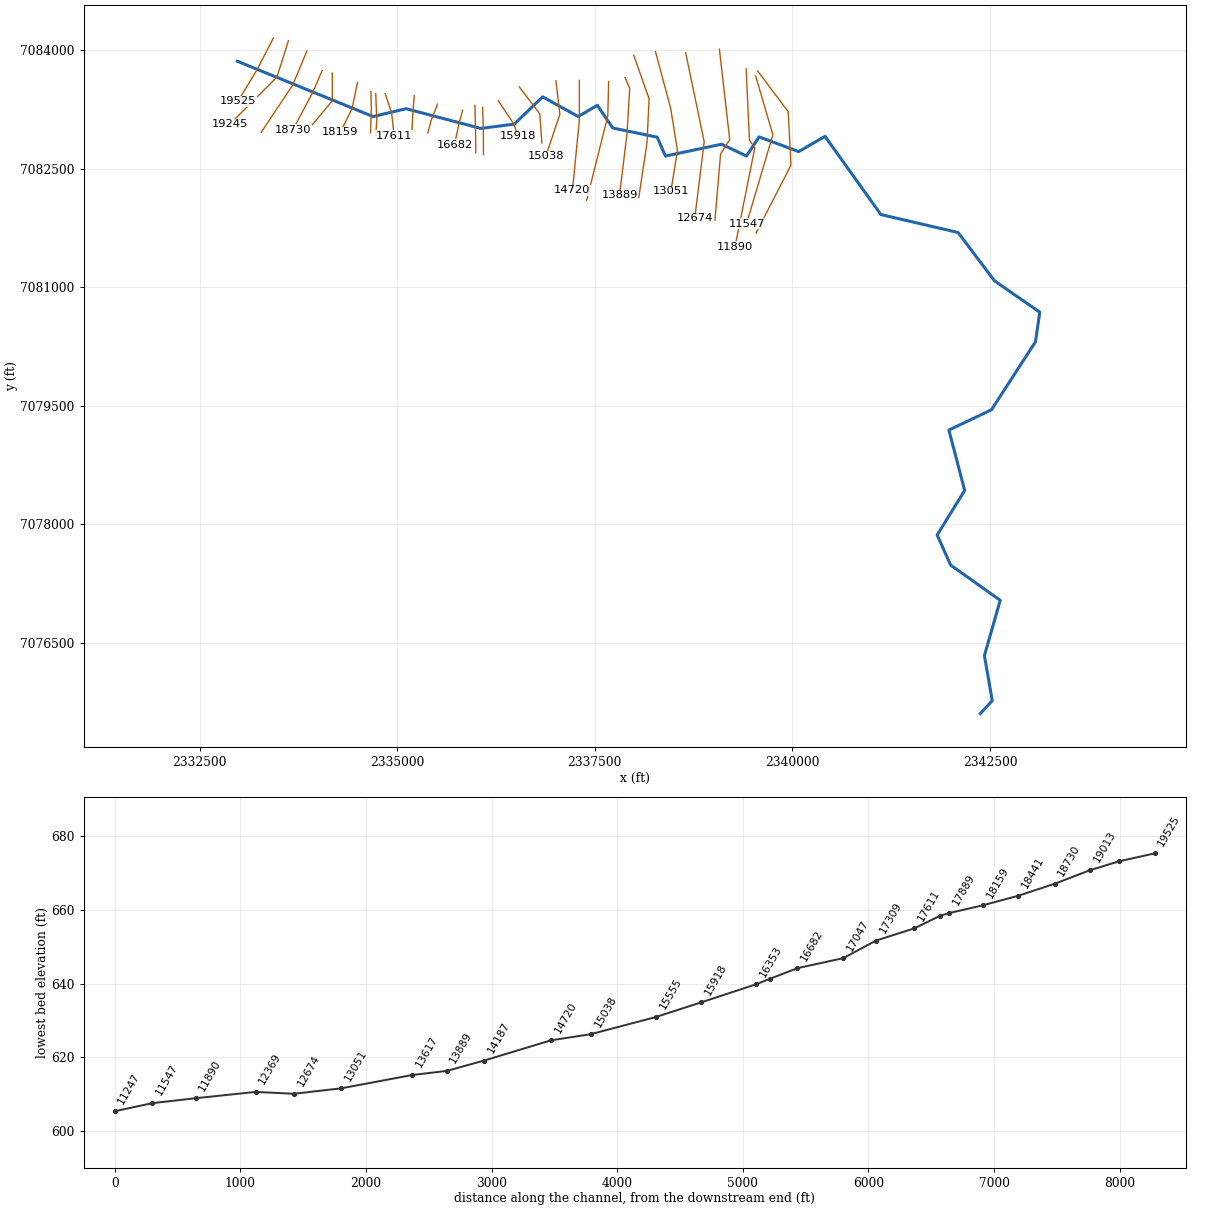
--- LWE S 099.prj (project) ---

Proj Title=LWE S 099 Base Level Engineering
Current Plan=p01
Default Exp/Contr=0.3,0.1
English Units
Geom File=g01
Flow File=f01
Plan File=p01
Y Axis Title=Elevation
X Axis Title(PF)=Main Channel Distance
X Axis Title(XS)=Station
BEGIN DESCRIPTION:
LWE S 099
END DESCRIPTION:
DSS Export Rating Curves= 0
DSS Export Rating Curve Sorted= 0
DSS Export Volume Flow Curves= 0
DXF OffsetX= 0
DXF OffsetY= 0
DXF ScaleX= 1
DXF ScaleY= 10

--- LWE S 099.p01 (plan) ---

Plan Title=Multiple Run
Program Version=4.10
Short Identifier=Multiple
Geom File=g01
Flow File=f01
Subcritical Flow
K Sum by GR= 0
Std Step Tol= 0.01
Critical Tol= 0.01
Num of Std Step Trials= 20
Max Error Tol= 0.3
Flow Tol Ratio= 0.001
Split Flow NTrial= 30
Split Flow Tol= 0.02
Split Flow Ratio= 0.02
Log Output Level= 0
Friction Slope Method= 1
Unsteady Friction Slope Method= 2
Unsteady Bridges Friction Slope Method= 1
Parabolic Critical Depth
Global Vel Dist= 1 , 1 , 1
Global Log Level= 0
CheckData=True
Encroach Param=-1 ,0,0, 0
BEGIN DESCRIPTION:
Multiple Run
END DESCRIPTION:
Computation Interval=1HOUR
Output Interval=1HOUR
Run HTab= 0
Run UNet= 0
Run PostProcess= 0
Run WQNet= 0
UNET Theta= 1
UNET Theta Warmup= 1
UNET ZTol= 0.02
UNET ZSATol= 0.05
UNET MxIter= 20
UNET MaxInSteps= 0
UNET DtIC= 0
UNET DtMin= 0
UNET MaxCRTS= 20
UNET WFStab= 2
UNET SFStab= 1
UNET WFX= 1
UNET SFX= 1
UNET DSS MLevel= 4
UNET DZMax Abort= 100
UNET Convert EG Bridges= 0
UNET Use Existing IB Tables=-1
UNET Froude Reduction=False
UNET Froude Limit= 1
UNET Froude Power= 10
UNET Time Slicing=0,0, 5
UNET Junction Losses=0
Instantaneous Interval=1HOUR
Write IC File= 0
Write IC File at Sim End=0
Echo Input=False
Echo Parameters=False
Echo Output=False
Write Detailed= 0
WQ AD Non Conservative
WQ ULTIMATE=-1
WQ Max Comp Step=1HOUR
WQ Output Interval=15MIN
WQ Output Selected Increments= 0
WQ Output face flow=0
WQ Output face velocity=0
WQ Output face area=0
WQ Output face dispersion=0
WQ Output cell volume=0
WQ Output cell surface area=0
WQ Output cell continuity=0
WQ Output cumulative cell continuity=0
WQ Output face conc=0
WQ Output face dconc_dx=0
WQ Output face courant=0
WQ Output face peclet=0
WQ Output face adv mass=0
WQ Output face disp mass=0
WQ Output cell mass=0
WQ Output cell source sink temp=0
WQ Output cell source sink nsm=0
WQ Output MaxMinRange=-1
WQ Daily Max Min Mean=-1
WQ Daily Range=0
WQ Daily Time=0
WQ Create Restart=0
WQ Fixed Restart=0
WQ System Summary=0
WQ Use Fixed Temperature=0
Sorting and Armoring Iterations= 10
XS Update Threshold= 0.02
Hydraulics Update Threshold= 0.02
Energy Slope Method= 1
Volume Change Method= 0
XS Weighting Method= 0
Number of US Weighted Cross Sections= 1
Number of DS Weighted Cross Sections= 1
Upstream XS Weight=0.25
Main XS Weight=0.5
Downstream XS Weight=0.25
Number of DS XS's Weighted with US Boundary= 1
Upstream Boundary Weight= 1
Weight of XSs Associated with US Boundary= 0
Number of US XS's Weighted with DS Boundary= 1
Downstream Boundary Weight= 0.5
Weight of XSs Associated with DS Boundary= 0.5
Sediment Output Level= 4
Mass or Volume Output= 0
Output Increment Type= 1
Profile and TS Output Increment= 10
XS Output Flag= 0
XS Output Increment= 10
Disregard all LS=0
Disregard all Conn=0
Disregard all Breaches=0
Disregard all Pumps=0

--- LWE S 099.f01 (steady flow) ---

Flow Title=Multiple
Number of Profiles=7
Profile Names=10-year,25-year,50-year,1pct_min,100-year,1pct_plu,500-year
River Rch & RM= LWE S 099,Reach-1,19525
     376     502     604     361     720    1438    1027
River Rch & RM= LWE S 099,Reach-1,16682
     589     807     987     599    1196    2385    1759
Boundary for River Rch & Prof#=LWE S 099,Reach-1,1
Up Type=0
Dn Type=3
Dn Slope=0.005
Boundary for River Rch & Prof#=LWE S 099,Reach-1,2
Up Type=0
Dn Type=3
Dn Slope=0.005
Boundary for River Rch & Prof#=LWE S 099,Reach-1,3
Up Type=0
Dn Type=3
Dn Slope=0.005
Boundary for River Rch & Prof#=LWE S 099,Reach-1,4
Up Type=0
Dn Type=3
Dn Slope=0.005
Boundary for River Rch & Prof#=LWE S 099,Reach-1,5
Up Type=0
Dn Type=3
Dn Slope=0.005
Boundary for River Rch & Prof#=LWE S 099,Reach-1,6
Up Type=0
Dn Type=3
Dn Slope=0.005
Boundary for River Rch & Prof#=LWE S 099,Reach-1,7
Up Type=0
Dn Type=3
Dn Slope=0.005

--- LWE S 099.g01 (geometry) ---

Geom Title=Existing Conditions
Program Version=4.10

River Reach=LWE S 099       ,Reach-1
Reach XY= 30
        2332979.        7083860.      2334694.22      7083160.52
      2335113.73      7083259.62      2336058.82      7083009.72
      2336481.55      7083064.99      2336840.14      7083409.66
      2337289.62      7083160.59      2337532.35      7083302.41
      2337726.53      7083015.45      2338289.06      7082899.39
      2338394.02      7082660.32      2339104.04       7082810.5
      2339418.71      7082660.97       2339578.8      7082903.02
      2340078.76      7082716.97      2340413.36      7082909.58
      2341118.58      7081920.75      2342095.68      7081693.36
      2342555.53      7081083.01      2343129.21      7080685.09
      2343075.17      7080311.58      2342518.22      7079450.32
      2341979.54      7079194.46      2342178.98       7078430.2
      2341831.26      7077865.94      2342001.85      7077486.16
      2342629.06      7077040.06      2342429.07      7076339.97
      2342528.13      7075770.33        2342379.        7075610.

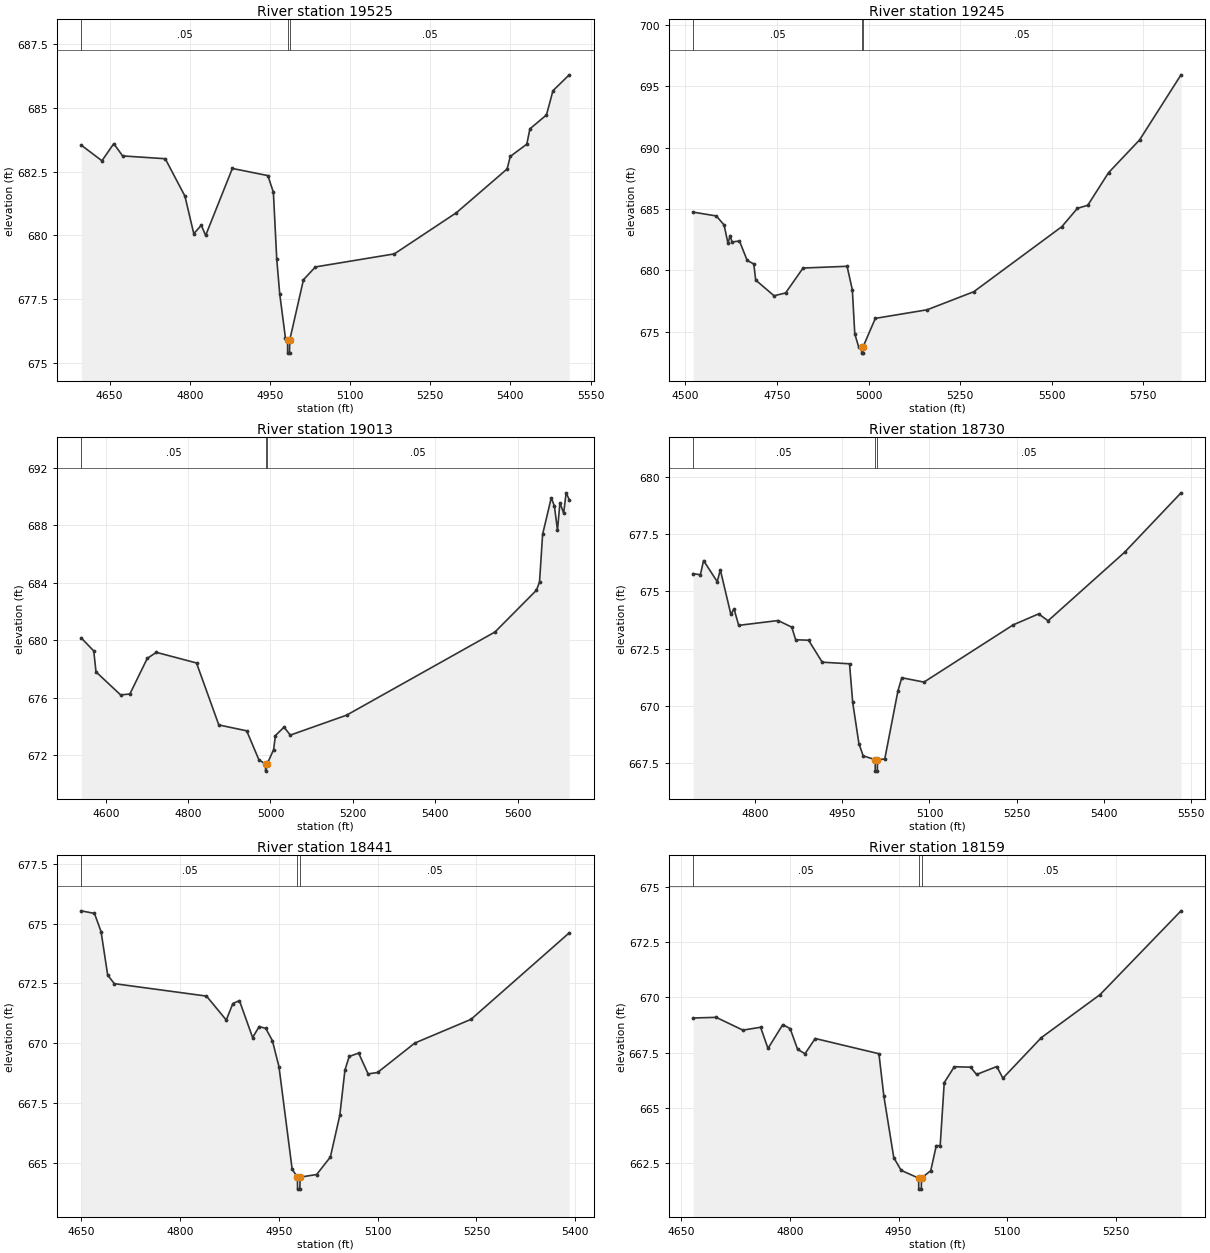
Type RM Length L Ch R = 1 ,19525   ,280,280,280
BEGIN DESCRIPTION:
LWE S 099 31.0
END DESCRIPTION:
XS GIS Cut Line= 3
      2333431.37       7084149.8      2333227.52      7083752.68
      2332984.63      7083354.03
#Sta/Elev= 30
  4596.9  683.53  4635.5  682.92  4657.7  683.59  4674.2  683.11    4754     683
  4790.8  681.54  4807.4  680.07  4821.5   680.4  4829.6     680  4879.6  682.62
  4946.1  682.34  4956.4  681.69  4962.7  679.07  4968.3  677.71  4978.9     676
  4982.9   675.9  4983.1   675.4  4986.6   675.4  4986.9   675.9  5012.7  678.27
  5035.1  678.77  5182.8  679.28    5299  680.89  5393.9   682.6  5399.8  683.09
  5430.7  683.57  5436.6  684.17  5467.5  684.71  5479.7  685.66  5510.1  686.28
#Mann= 3 ,-1 , 0
  4596.9     .05       0  4982.9    .033       0  4986.9     .05       0
Bank Sta=4982.9,4986.9
XS Rating Curve= 0 ,0
Exp/Cntr=0.3,0.1

Type RM Length L Ch R = 1 ,19245   ,232,232,232
BEGIN DESCRIPTION:
LWE S 099 30.0
END DESCRIPTION:
XS GIS Cut Line= 3
      2333624.62      7084120.65        2333479.        7083660.
      2332879.04      7083060.04
#Sta/Elev= 30
  4521.2  684.75  4584.6  684.44  4605.8   683.7  4616.3  682.21  4622.2  682.84
  4627.4  682.32  4647.7   682.4  4668.7  680.82  4686.8  680.53    4692  679.22
  4742.1  677.94  4773.6  678.17  4821.3   680.2  4941.4  680.34  4955.8  678.42
  4962.4  674.84  4972.9  673.79  4980.9  673.77  4981.2  673.27  4984.7  673.27
  4984.9  673.77  5018.5   676.1  5159.9   676.8  5287.2  678.27  5527.6  683.57
    5570  685.06  5598.3  685.31  5654.9  687.96  5739.7  690.63  5852.8  695.93
#Mann= 3 ,-1 , 0
  4521.2     .05       0  4980.9     .04       0  4984.9     .05       0
Bank Sta=4980.9,4984.9
XS Rating Curve= 0 ,0
Exp/Cntr=0.3,0.1

Type RM Length L Ch R = 1 ,19013   ,283,283,283
BEGIN DESCRIPTION:
LWE S 099 29.0
END DESCRIPTION:
XS GIS Cut Line= 3
      2333857.58      7083988.26        2333679.        7083560.
      2333279.01      7082960.01
#Sta/Elev= 30
  4540.5  680.15  4570.7  679.25  4576.2  677.79  4636.1  676.18  4658.5  676.25
  4700.7  678.73  4722.8  679.15  4820.3  678.41  4874.5  674.09  4942.2  673.68
    4972  671.65  4987.9  671.37  4988.1  670.87  4991.9  671.37  5007.5  672.36
    5012  673.35    5033  673.94  5048.1  673.38  5184.8  674.77  5545.3  680.57
    5646  683.48  5653.5  684.06    5661  687.38    5682  689.92  5689.6  689.35
  5697.1  687.67  5703.1  689.58  5712.1  688.85  5718.1  690.27  5725.6   689.8
#Mann= 3 ,-1 , 0
  4540.5     .05       0  4987.9     .04       0  4991.9     .05       0
Bank Sta=4987.9,4991.9
XS Rating Curve= 0 ,0
Exp/Cntr=0.3,0.1

Type RM Length L Ch R = 1 ,18730   ,289,289,289
BEGIN DESCRIPTION:
LWE S 099 28.0
END DESCRIPTION:
XS GIS Cut Line= 3
      2334050.85       7083742.1        2333929.        7083460.
      2333677.58      7082990.24
#Sta/Elev= 30
    4693  675.78  4705.5  675.73    4711  676.35  4734.5  675.43  4739.9  675.94
    4758     674  4763.4  674.24  4771.5  673.52  4839.4  673.73  4862.9  673.44
  4869.6  672.89  4891.8  672.87  4915.3  671.91  4962.3  671.84  4967.8  670.15
  4978.5  668.35  4985.8  667.82  5006.4  667.65  5006.7  667.15  5010.2  667.15
  5010.4  667.65    5023  667.68  5045.7  670.66  5052.3  671.23  5090.5  671.04
  5244.1  673.54  5287.9  674.02  5304.2  673.72  5435.8  676.71  5533.1  679.31
#Mann= 3 ,-1 , 0
    4693     .05       0  5006.4    .033       0  5010.4     .05       0
Bank Sta=5006.4,5010.4
XS Rating Curve= 0 ,0
Exp/Cntr=0.3,0.1

Type RM Length L Ch R = 1 ,18441   ,282,282,282
BEGIN DESCRIPTION:
LWE S 099 27.0
END DESCRIPTION:
XS GIS Cut Line= 3
        2334179.        7083710.        2334179.        7083360.
      2333929.01      7083060.01
#Sta/Elev= 30
  4650.4  675.53  4670.4  675.42  4680.4  674.66  4690.4  672.85  4700.4  672.49
  4840.4  671.97  4870.4  670.97  4880.4  671.66  4890.4  671.78  4910.4  670.24
  4920.4   670.7  4930.4  670.62  4940.4  670.11  4950.4  669.02  4970.4  664.74
  4978.4  664.41  4978.6  663.91  4982.1  663.91  4982.4  664.41  5007.6  664.52
  5028.4  665.25  5042.7  666.99  5050.5  668.88    5057  669.45  5071.3  669.59
  5085.7  668.72    5100  668.78  5156.6  670.01  5241.9     671  5390.9  674.61
#Mann= 3 ,-1 , 0
  4650.4     .05       0  4978.4     .04       0  4982.4     .05       0
Bank Sta=4978.4,4982.4
XS Rating Curve= 0 ,0
Exp/Cntr=0.3,0.1

Type RM Length L Ch R = 1 ,18159   ,270,270,270
BEGIN DESCRIPTION:
LWE S 099 26.0
END DESCRIPTION:
XS GIS Cut Line= 3
      2334498.26       7083591.2        2334429.        7083260.
      2334278.99      7082959.98
#Sta/Elev= 30
  4666.3  669.07  4698.2   669.1    4735  668.52  4759.5  668.65  4769.7  667.69
  4790.1  668.77  4800.3  668.59  4810.6  667.65  4820.8  667.45  4834.9  668.14
  4922.9  667.45  4929.7  665.53  4943.4  662.74  4953.6  662.16  4977.7  661.81
  4977.9  661.31  4981.4  661.31  4981.7  661.81  4994.5  662.15  5002.1  663.28
  5007.5  663.28  5013.1  666.14    5027  666.86  5049.4  666.84  5057.8  666.51
  5085.7  666.87  5094.1  666.34  5147.2  668.18  5228.3  670.13  5340.1  673.93
#Mann= 3 ,-1 , 0
  4666.3     .05       0  4977.7    .033       0  4981.7     .05       0
Bank Sta=4977.7,4981.7
XS Rating Curve= 0 ,0
Exp/Cntr=0.3,0.1

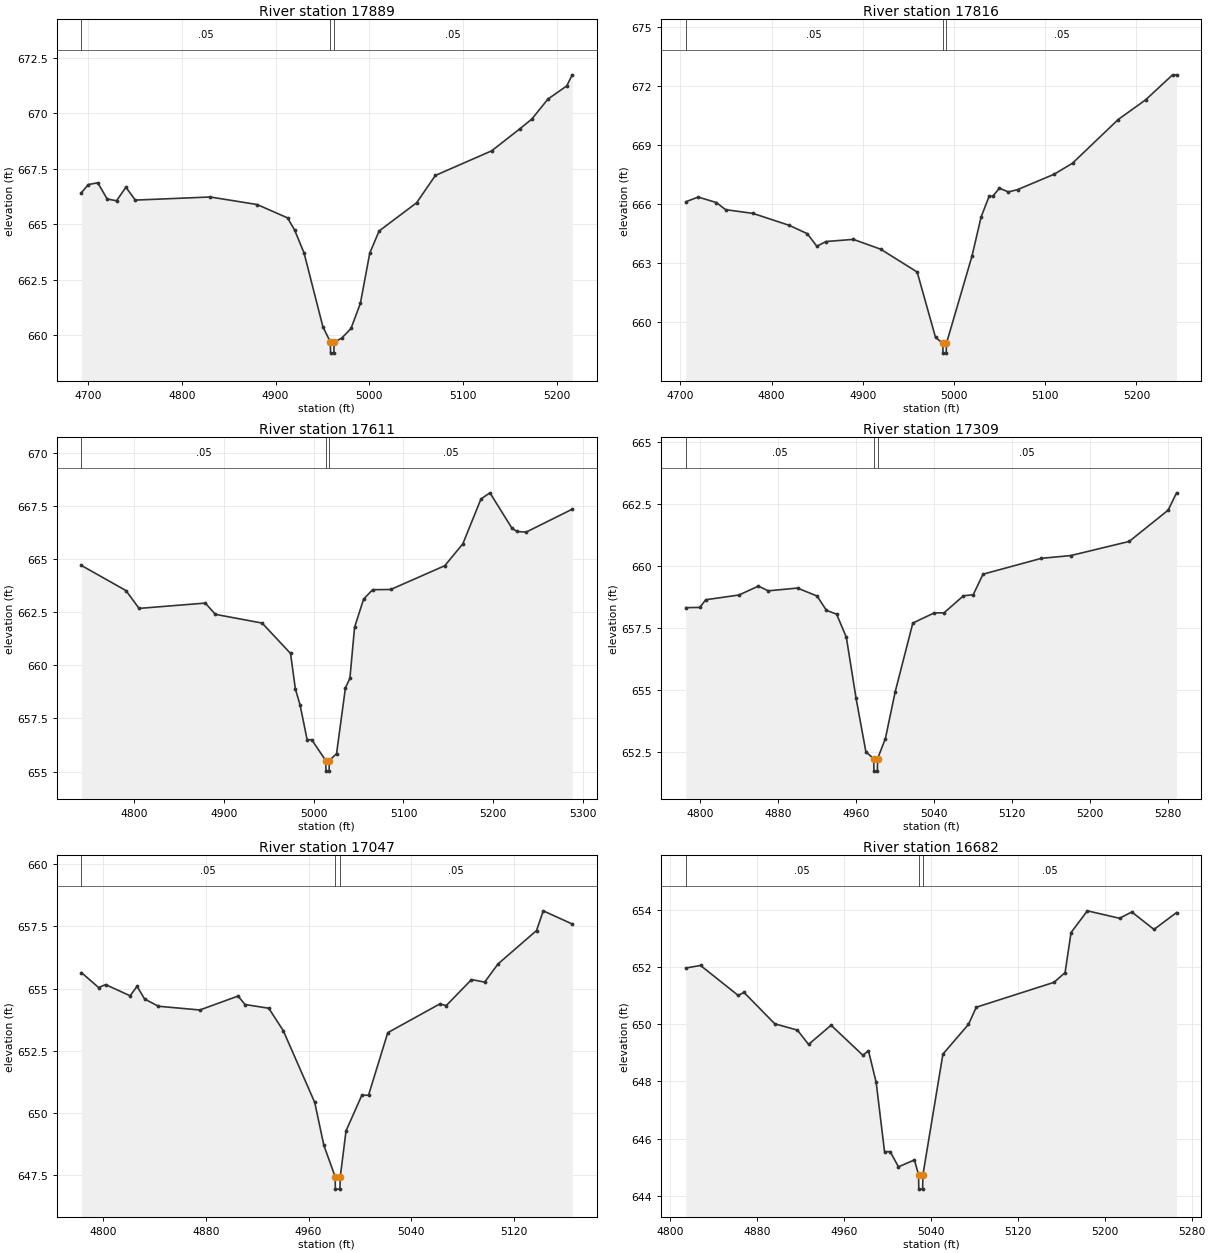
Type RM Length L Ch R = 1 ,17889   ,73,73,73
BEGIN DESCRIPTION:
LWE S 099 25.0
END DESCRIPTION:
XS GIS Cut Line= 3
      2334667.69      7083477.38      2334672.98      7083257.62
      2334662.43      7082954.13
#Sta/Elev= 30
  4692.9  666.42  4700.3  666.78  4710.3  666.86  4720.3  666.13  4730.3  666.05
  4740.3  666.66  4750.3  666.08  4830.3  666.22  4880.3  665.88  4912.7  665.28
  4920.3  664.73  4930.4  663.69  4950.4  660.38  4958.4  659.69  4958.6  659.19
  4962.1  659.19  4962.4  659.69  4970.4  659.86  4980.4   660.3  4990.4  661.43
  5000.4  663.69  5010.4  664.69  5050.4  665.96  5070.4  667.19  5130.5   668.3
  5160.5  669.29  5173.3  669.73  5190.5  670.63  5210.5  671.22  5216.4  671.72
#Mann= 3 ,-1 , 0
  4692.9     .05       0  4958.4    .033       0  4962.4     .05       0
Bank Sta=4958.4,4962.4
XS Rating Curve= 0 ,0
Exp/Cntr=0.3,0.1

Type RM Length L Ch R = 1 ,17816   ,205,205,205
BEGIN DESCRIPTION:
LWE S 099 23.8
END DESCRIPTION:
XS GIS Cut Line= 3
      2334728.58      7083453.54      2334741.82      7083117.31
      2334728.58      7082916.14
#Sta/Elev= 30
  4705.9  666.11  4719.5  666.35  4739.5  666.07  4749.5  665.71  4779.5  665.52
  4819.5  664.91  4839.1  664.49  4849.6  663.85  4859.6  664.09  4889.6   664.2
  4919.6   663.7  4959.6  662.54  4979.7  659.22  4987.7  658.92  4987.9  658.42
  4991.4  658.42  4991.7  658.92  5019.7  663.35  5029.7  665.34  5038.5  666.39
  5042.4  666.39  5049.7   666.8  5059.7  666.61  5069.8  666.73  5109.8  667.51
  5129.9  668.07    5180  670.29  5210.1  671.29  5239.6  672.56    5244  672.56
#Mann= 3 ,-1 , 0
  4705.9     .05       0  4987.7     .04       0  4991.7     .05       0
Bank Sta=4987.7,4991.7
XS Rating Curve= 0 ,0
Exp/Cntr=0.3,0.1

Type RM Length L Ch R = 1 ,17611   ,302,302,302
BEGIN DESCRIPTION:
LWE S 099 24.0
END DESCRIPTION:
XS GIS Cut Line= 3
      2334847.72      7083450.85        2334929.        7083210.
      2334961.54       7082918.8
#Sta/Elev= 30
    4741   664.7  4790.6  663.52  4805.2  662.68  4879.1  662.93  4890.3   662.4
  4942.4  661.99  4974.1  660.56  4979.5  658.89  4984.7  658.14  4992.6   656.5
  4997.7   656.5  5013.3  655.52  5013.6  655.02  5017.1  655.02  5017.3  655.52
  5025.4  655.84  5035.3  658.94  5040.3  659.39  5045.5  661.79  5055.6  663.12
  5065.6  663.56  5085.8  663.57  5146.1  664.69  5166.2  665.72  5186.4  667.83
  5196.4  668.12  5220.9  666.46  5226.6   666.3  5236.7  666.27  5288.2  667.35
#Mann= 3 ,-1 , 0
    4741     .05       0  5013.3     .04       0  5017.3     .05       0
Bank Sta=5013.3,5017.3
XS Rating Curve= 0 ,0
Exp/Cntr=0.3,0.1

Type RM Length L Ch R = 1 ,17309   ,262,262,262
BEGIN DESCRIPTION:
LWE S 099 23.0
END DESCRIPTION:
XS GIS Cut Line= 3
       2335215.7       7083424.4      2335197.16      7083188.79
      2335183.93      7082921.36
#Sta/Elev= 30
  4785.2  658.33  4799.6  658.34  4805.7  658.65  4839.8  658.84  4859.8   659.2
  4869.9  659.01    4900  659.12    4920   658.8  4929.7  658.22  4940.1  658.07
  4950.1  657.14  4960.1  654.68  4970.2  652.52  4978.2  652.24  4978.5  651.74
    4982  651.74  4982.2  652.24  4990.2  653.05  5000.3  654.94  5018.4  657.71
  5040.4  658.12  5050.4  658.12  5070.4  658.81  5080.4  658.85  5090.5  659.68
  5150.5  660.32  5180.5  660.43  5240.6     661  5280.6  662.26  5289.3  662.96
#Mann= 3 ,-1 , 0
  4785.2     .05       0  4978.2    .033       0  4982.2     .05       0
Bank Sta=4978.2,4982.2
XS Rating Curve= 0 ,0
Exp/Cntr=0.3,0.1

Type RM Length L Ch R = 1 ,17047   ,365,365,365
BEGIN DESCRIPTION:
LWE S 099 22.0
END DESCRIPTION:
XS GIS Cut Line= 3
      2335509.55      7083315.85        2335429.        7083110.
        2335388.      7082954.05
#Sta/Elev= 30
  4783.1  655.64  4796.5  655.04  4801.9  655.16    4821  654.71  4826.4  655.09
  4832.3  654.58  4843.1  654.29  4875.3  654.14  4905.1   654.7  4910.5  654.36
    4929  654.21  4940.3  653.31  4964.8  650.43  4971.9  648.71  4980.7  647.45
  4980.9  646.95  4984.4  646.95  4984.7  647.45  4989.2  649.29  5001.5  650.72
  5006.7  650.72  5021.7  653.23  5062.1  654.38  5067.3  654.32  5086.9  655.36
  5097.2  655.26  5107.6  655.99  5137.6  657.33  5142.8  658.12  5165.4  657.59
#Mann= 3 ,-1 , 0
  4783.1     .05       0  4980.7    .033       0  4984.7     .05       0
Bank Sta=4980.7,4984.7
XS Rating Curve= 0 ,0
Exp/Cntr=0.3,0.1

Type RM Length L Ch R = 1 ,16682   ,215,215,215
BEGIN DESCRIPTION:
LWE S 099 21.0
END DESCRIPTION:
XS GIS Cut Line= 3
      2335827.25      7083239.12        2335779.        7083060.
        2335724.      7082799.65
#Sta/Elev= 30
  4814.5  651.96  4828.1  652.05  4862.8     651    4868  651.11  4896.4  650.01
  4917.2  649.79  4927.5  649.29  4948.2  649.96  4977.5  648.91  4982.6  649.07
  4989.7  647.96  4997.4  645.54  5002.6  645.54  5010.2  645.01  5024.9  645.25
  5028.7  644.73  5028.9  644.23  5032.4  644.23  5032.7  644.73  5051.1  648.95
  5074.6  649.99  5081.8  650.59  5153.3  651.46  5163.5   651.8    5169   653.2
    5184  653.96  5213.6   653.7  5224.9  653.92  5245.3  653.31  5266.1   653.9
#Mann= 3 ,-1 , 0
  4814.5     .05       0  5028.7    .033       0  5032.7     .05       0
Bank Sta=5028.7,5032.7
XS Rating Curve= 0 ,0
Exp/Cntr=0.3,0.1

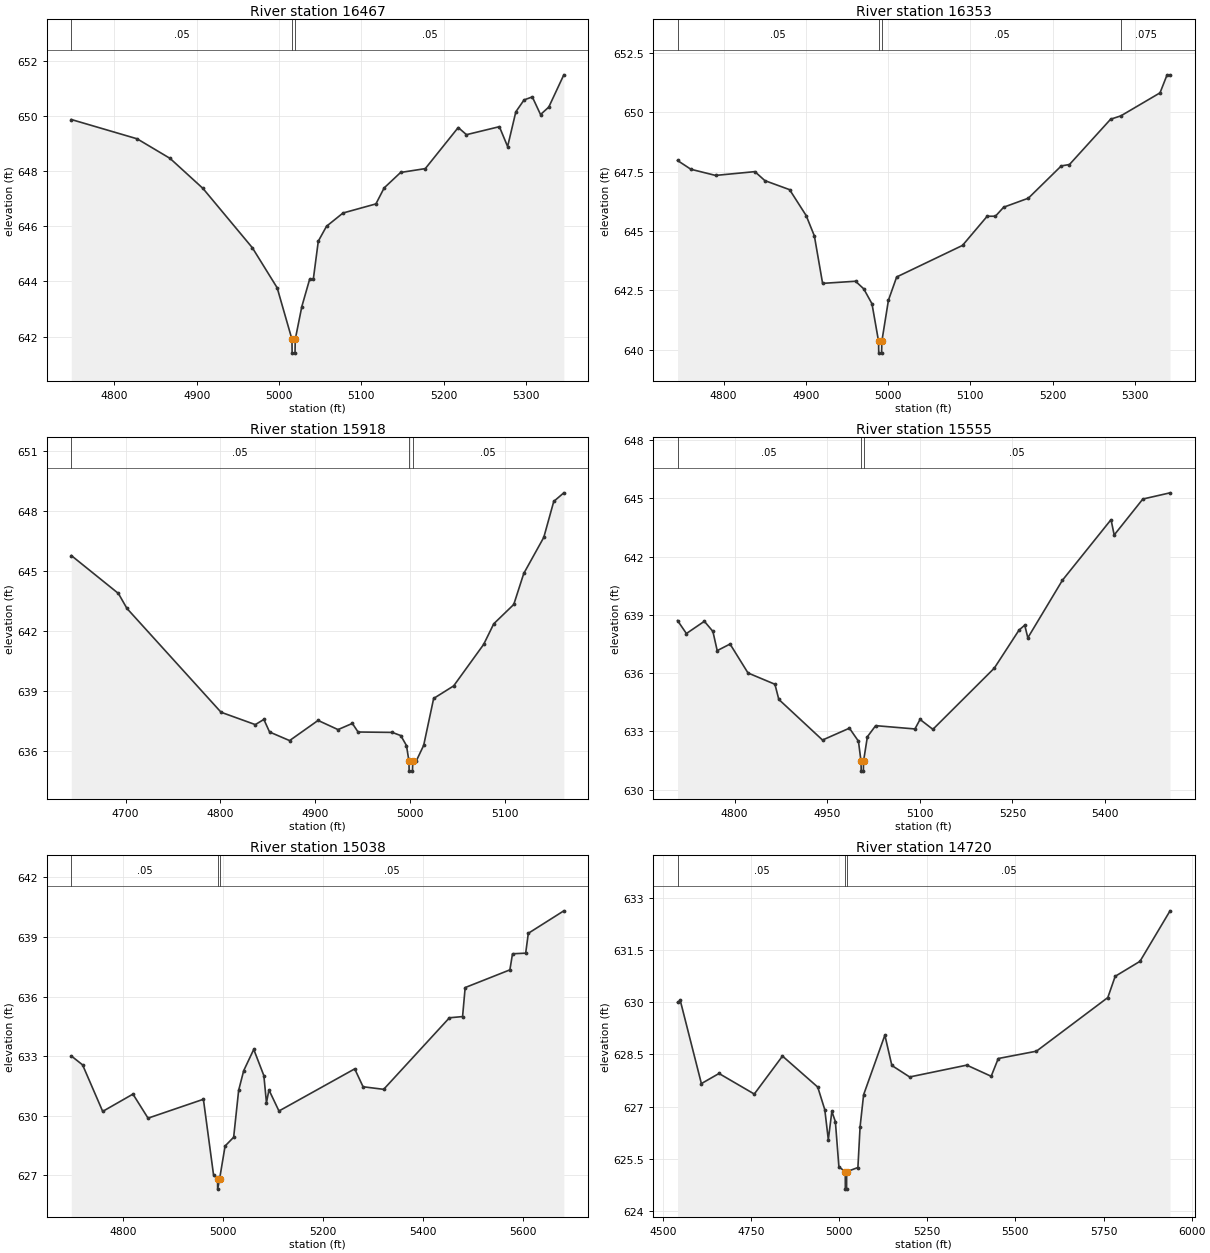
Type RM Length L Ch R = 1 ,16467   ,114,114,114
BEGIN DESCRIPTION:
LWE S 099 20.2
END DESCRIPTION:
XS GIS Cut Line= 3
      2335983.43      7083299.96      2335991.38      7083006.12
      2335994.02      7082701.68
#Sta/Elev= 30
  4747.7  649.87  4827.7  649.17  4867.7  648.46  4907.7  647.37  4967.7  645.22
  4997.8  643.77  5015.8   641.9    5016   641.4  5019.5   641.4  5019.8   641.9
  5027.8  643.09  5037.2  644.07  5041.7  644.07  5047.8  645.46  5057.8     646
  5077.8  646.48  5117.8  646.81  5127.8  647.39  5147.8  647.95  5177.8  648.09
  5217.8  649.58  5227.8  649.32  5267.8  649.61  5277.8  648.89  5287.8  650.15
  5297.8  650.58  5307.8  650.69  5317.8  650.05  5327.8  650.32  5346.1  651.49
#Mann= 3 ,-1 , 0
  4747.7     .05       0  5015.8    .033       0  5019.8     .05       0
Bank Sta=5015.8,5019.8
XS Rating Curve= 0 ,0
Exp/Cntr=0.3,0.1

Type RM Length L Ch R = 1 ,16353   ,435,435,435
BEGIN DESCRIPTION:
LWE S 099 20.0
END DESCRIPTION:
XS GIS Cut Line= 3
      2336081.39       7083276.2      2336089.33      7082982.29
      2336091.98      7082677.82
#Sta/Elev= 30
  4744.1  647.97  4760.3   647.6  4790.3  647.34  4838.1   647.5  4850.3  647.12
  4880.3  646.74  4900.4  645.65  4910.4  644.79  4920.4  642.79  4960.4  642.88
  4970.4  642.56  4980.4  641.93  4988.4  640.35  4988.6  639.85  4992.1  639.85
  4992.4  640.35  5000.4  642.08  5010.4  643.06  5090.4  644.39  5120.4  645.62
  5130.4  645.62  5140.4     646  5170.4  646.38  5210.4  647.74  5220.4   647.8
  5270.4  649.71  5282.8  649.85  5330.4  650.82    5339  651.58  5342.6  651.58
#Mann= 4 ,-1 , 0
  4744.1     .05       0  4988.4    .033       0  4992.4     .05       0
  5282.8    .075       0
Bank Sta=4988.4,4992.4
XS Rating Curve= 0 ,0
Exp/Cntr=0.3,0.1

Type RM Length L Ch R = 1 ,15918   ,363,363,363
BEGIN DESCRIPTION:
LWE S 099 19.0
END DESCRIPTION:
XS GIS Cut Line= 3
        2336279.        7083360.        2336479.        7083060.
      2336529.01      7082909.97
#Sta/Elev= 30
  4642.9  645.77  4692.5  643.87  4701.5  643.12  4800.6  637.92  4836.7   637.3
  4845.7  637.56  4851.7  636.93  4872.8   636.5  4902.8  637.51  4923.8  637.05
  4938.9  637.36  4944.9  636.93  4980.9  636.91  4989.9  636.75  4995.9  636.25
  4998.5  635.47  4998.7  634.97  5002.2  634.97  5002.5  635.47  5006.1  635.47
    5014  636.26  5024.5  638.61  5045.6  639.24  5077.2  641.32  5087.8  642.35
  5108.9  643.32  5119.4  644.87  5140.5  646.68    5151  648.48  5161.6  648.91
#Mann= 3 ,-1 , 0
  4642.9     .05       0  4998.5    .033       0  5002.5     .05       0
Bank Sta=4998.5,5002.5
XS Rating Curve= 0 ,0
Exp/Cntr=0.3,0.1

Type RM Length L Ch R = 1 ,15555   ,517,517,517
BEGIN DESCRIPTION:
LWE S 099 18.0
END DESCRIPTION:
XS GIS Cut Line= 3
      2336544.65      7083535.63      2336804.12      7083194.08
       2336830.6      7082826.06
#Sta/Elev= 30
  4707.4  638.71  4721.8  638.04  4750.9  638.67  4764.7  638.15  4771.7  637.16
  4792.5   637.5  4821.6  636.01  4865.2  635.43  4871.5  634.65  4942.3  632.56
  4985.9  633.17  5000.5   632.5  5004.7  631.46    5005  630.96  5008.5  630.96
  5008.7  631.46    5015  632.73  5028.4   633.3    5092  633.13  5100.3  633.62
  5121.1  633.11  5220.6  636.26  5260.7  638.22  5269.9  638.47  5274.9  637.82
  5330.9  640.78  5409.7   643.9  5414.8  643.11  5461.2  644.96  5505.3  645.28
#Mann= 3 ,-1 , 0
  4707.4     .05       0  5004.7    .033       0  5008.7     .05       0
Bank Sta=5004.7,5008.7
XS Rating Curve= 0 ,0
Exp/Cntr=0.3,0.1

Type RM Length L Ch R = 1 ,15038   ,318,318,318
BEGIN DESCRIPTION:
LWE S 099 17.0
END DESCRIPTION:
XS GIS Cut Line= 3
      2337007.96       7083612.4      2337058.27      7083188.79
      2336880.89       7082659.3
#Sta/Elev= 30
  4695.9  633.01  4718.5  632.56  4758.7  630.22  4819.2  631.09  4849.4  629.88
  4960.1  630.83  4980.3  627.04  4988.4  626.81  4988.6  626.31  4992.4  626.81
  5003.5  628.48  5020.6  628.92  5030.6  631.28  5040.7  632.27  5060.8  633.34
    5081  632.02  5086.2  630.66  5091.2   631.3  5111.2  630.24  5262.7  632.36
  5279.4  631.46  5320.6  631.33  5452.1  634.93  5478.4  634.99  5483.6  636.45
    5573  637.34  5578.3  638.15  5604.6  638.18  5609.9  639.18  5680.9  640.31
#Mann= 3 ,-1 , 0
  4695.9     .05       0  4988.4    .033       0  4992.4     .05       0
Bank Sta=4988.4,4992.4
XS Rating Curve= 0 ,0
Exp/Cntr=0.3,0.1

Type RM Length L Ch R = 1 ,14720   ,533,533,533
BEGIN DESCRIPTION:
LWE S 099 16.6
END DESCRIPTION:
XS GIS Cut Line= 3
      2337304.47      7083617.71      2337304.47      7083112.01
      2337217.11       7082225.1
#Sta/Elev= 30
  4541.8  629.99  4549.5  630.05  4609.5  627.66  4659.5  627.95  4759.5  627.36
  4839.5  628.45  4939.5  627.56  4959.5  626.91  4969.5  626.05  4979.5  626.86
  4989.5  626.57  4999.5  625.27  5017.5  625.13  5017.8  624.63  5021.3  624.63
  5021.5  625.13  5053.4  625.25  5059.6  626.42  5069.6  627.34  5129.9  629.05
  5149.7  628.18  5200.2  627.85  5362.2  628.19  5431.4  627.87  5451.5  628.38
  5559.7  628.59  5762.2  630.13  5783.1  630.74  5853.4  631.17  5938.7  632.62
#Mann= 3 ,-1 , 0
  4541.8     .05       0  5017.5    .033       0  5021.5     .05       0
Bank Sta=5017.5,5021.5
XS Rating Curve= 0 ,0
Exp/Cntr=0.3,0.1

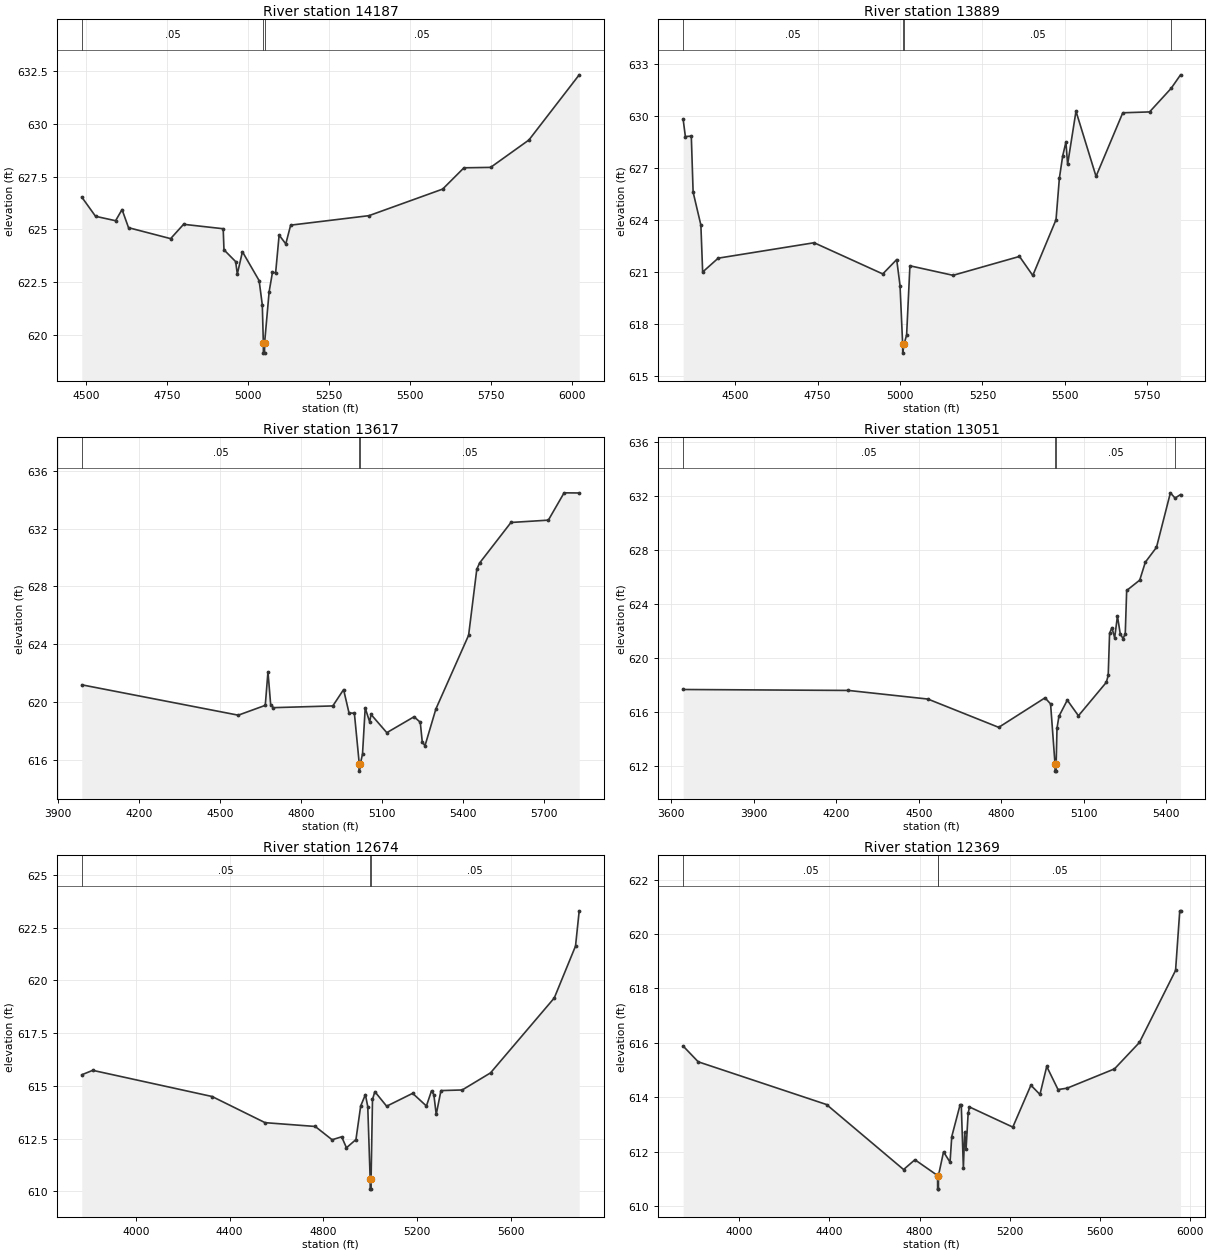
Type RM Length L Ch R = 1 ,14187   ,298,298,298
BEGIN DESCRIPTION:
LWE S 099 16.4
END DESCRIPTION:
XS GIS Cut Line= 3
      2337675.11      7083604.41      2337664.52      7083167.61
      2337397.14      7082100.73
#Sta/Elev= 30
    4486  626.53  4528.5  625.62  4590.4  625.41  4610.4  625.94  4630.4  625.08
  4760.5  624.56  4800.5  625.24  4922.9  625.03  4925.3  624.03  4961.4  623.47
  4966.5  622.88  4982.3  623.94  5033.9  622.57  5043.7  621.42  5046.9  619.63
  5047.1  619.13  5050.6  619.13  5050.9  619.63  5064.8  622.04  5075.1  622.96
  5084.9  622.94  5095.7  624.73  5116.3  624.31  5131.3   625.2  5373.2  625.65
  5600.9  626.91  5666.7  627.92  5749.1  627.94  5867.5  629.24  6022.8  632.33
#Mann= 3 ,-1 , 0
    4486     .05       0  5046.9    .033       0  5050.9     .05       0
Bank Sta=5046.9,5050.9
XS Rating Curve= 0 ,0
Exp/Cntr=0.3,0.1

Type RM Length L Ch R = 1 ,13889   ,272,272,272
BEGIN DESCRIPTION:
LWE S 099 16.0
END DESCRIPTION:
XS GIS Cut Line= 4
      2337882.67      7083654.32      2337942.13      7083516.49
      2337905.74       7082925.1      2337812.07      7082165.37
#Sta/Elev= 30
  4342.5  629.81  4349.3  628.81  4367.3  628.83  4372.8   625.6  4396.3   623.7
  4401.7  620.99  4448.8  621.79  4739.6  622.68  4947.8  620.88    4990  621.71
  5000.1  620.21  5008.1  616.81  5008.3  616.31  5012.1  616.81  5020.1  617.36
  5030.1  621.35  5160.8   620.8  5362.3  621.89  5402.6  620.79  5473.1  624.01
  5483.2   626.4  5493.3  627.69  5503.1  628.49  5508.2   627.2  5533.6  630.27
  5594.4  626.51  5675.5  630.18  5756.7  630.23  5822.1  631.59  5850.6  632.37
#Mann= 4 ,-1 , 0
  4342.5     .05       0  5008.1    .033       0  5012.1     .05       0
  5822.1    .075       0
Bank Sta=5008.1,5012.1
XS Rating Curve= 0 ,0
Exp/Cntr=0.3,0.1

Type RM Length L Ch R = 1 ,13617   ,566,566,566
BEGIN DESCRIPTION:
LWE S 099 15.0
END DESCRIPTION:
XS GIS Cut Line= 4
      2337992.06      7083936.61       2338186.6      7083386.09
      2338160.71      7082831.43      2338056.71       7082134.6
#Sta/Elev= 30
  3988.5  621.19  4568.5  619.09  4668.6  619.77  4678.6  622.09  4688.6  619.82
  4698.6  619.61  4918.9  619.73  4958.9  620.86  4978.9  619.25  4998.9  619.22
    5017  615.72  5017.2  615.22    5021  615.72    5029   616.4    5039  619.59
  5055.6  618.62  5060.6  619.14  5119.1  617.88  5220.1  618.98  5243.1   618.6
  5250.4  617.25  5260.5  616.97    5301  619.52  5422.3  624.62  5452.6  629.18
  5462.8  629.61  5579.3  632.42  5717.8  632.58  5776.2  634.47  5832.2  634.46
#Mann= 3 ,-1 , 0
  3988.5     .05       0    5017    .033       0    5021     .05       0
Bank Sta=5017,5021
XS Rating Curve= 0 ,0
Exp/Cntr=0.3,0.1

Type RM Length L Ch R = 1 ,13051   ,377,377,377
BEGIN DESCRIPTION:
LWE S 099 14.0
END DESCRIPTION:
XS GIS Cut Line= 4
      2338267.32      7083982.41      2338458.92      7083269.27
      2338545.78      7082732.56      2338462.75      7082213.59
#Sta/Elev= 30
  3643.9  617.66  4244.8  617.59  4533.5  616.95  4790.8  614.85    4959  617.04
  4979.3  616.59  4995.5   612.1  4995.8   611.6  4999.3   611.6  4999.5   612.1
  5002.6  614.78  5009.6  615.67    5040  616.87  5080.5  615.71  5181.8  618.19
  5188.7   618.7  5193.7  621.82  5202.1  622.25  5212.2   621.5  5222.3  623.11
  5232.4   621.8  5242.6  621.44  5250.7   621.8  5255.8  625.01  5303.3  625.78
  5323.6  627.11  5364.1  628.21  5414.7  632.26  5431.7  631.87  5451.6  632.13
#Mann= 4 ,-1 , 0
  3643.9     .05       0  4995.5    .033       0  4999.5     .05       0
  5431.7    .075       0
Bank Sta=4995.5,4999.5
XS Rating Curve= 0 ,0
Exp/Cntr=0.3,0.1

Type RM Length L Ch R = 1 ,12674   ,305,305,305
BEGIN DESCRIPTION:
LWE S 099 13.0
END DESCRIPTION:
XS GIS Cut Line= 3
      2338649.86      7083965.83      2338884.02      7082841.84
       2338764.4      7081874.43
#Sta/Elev= 30
  3769.4  615.53  3816.2  615.74  4325.4   614.5  4551.7  613.26  4765.7  613.08
  4837.7  612.45  4878.5  612.59    4899  612.07  4939.5  612.46  4959.7  614.05
  4979.8  614.59  4989.9  614.02  5000.1  610.61  5000.4  610.11  5003.9  610.11
  5004.1  610.61  5010.1  614.36  5020.1  614.73  5070.5  614.04  5181.4  614.65
  5240.2  614.05    5262  614.77    5272  614.58  5282.1  613.65  5302.3  614.78
    5393  614.81  5513.9  615.62  5785.9  619.17  5876.6  621.63  5892.3   623.3
#Mann= 3 ,-1 , 0
  3769.4     .05       0  5000.1     .04       0  5004.1     .05       0
Bank Sta=5000.1,5004.1
XS Rating Curve= 0 ,0
Exp/Cntr=0.3,0.1

Type RM Length L Ch R = 1 ,12369   ,479,479,479
BEGIN DESCRIPTION:
LWE S 099 12.7
END DESCRIPTION:
XS GIS Cut Line= 4
      2339076.56      7084012.66      2339206.65      7082867.86
      2339091.31      7082686.28      2339019.32      7081847.95
#Sta/Elev= 30
  3750.2  615.88  3817.2   615.3  4386.9  613.73  4729.1  611.34  4779.4   611.7
    4880  611.12  4880.3  610.62  4883.8  610.62    4884  611.12  4906.5  611.99
  4935.4  611.61    4943  612.55  4979.4   613.7  4985.3   613.7  4994.6   611.4
  5000.5  612.71  5006.5  612.09  5015.8  613.41  5021.7  613.64  5214.1   612.9
  5294.4  614.44  5334.6   614.1  5364.7  615.13  5414.9  614.28    5455  614.33
  5665.6  615.04  5776.2  616.01  5936.8  618.66  5955.4  620.85  5958.9  620.85
#Mann= 3 ,-1 , 0
  3750.2     .05       0    4880     .04       0    4884     .05       0
Bank Sta=4880,4884
XS Rating Curve= 0 ,0
Exp/Cntr=0.3,0.1

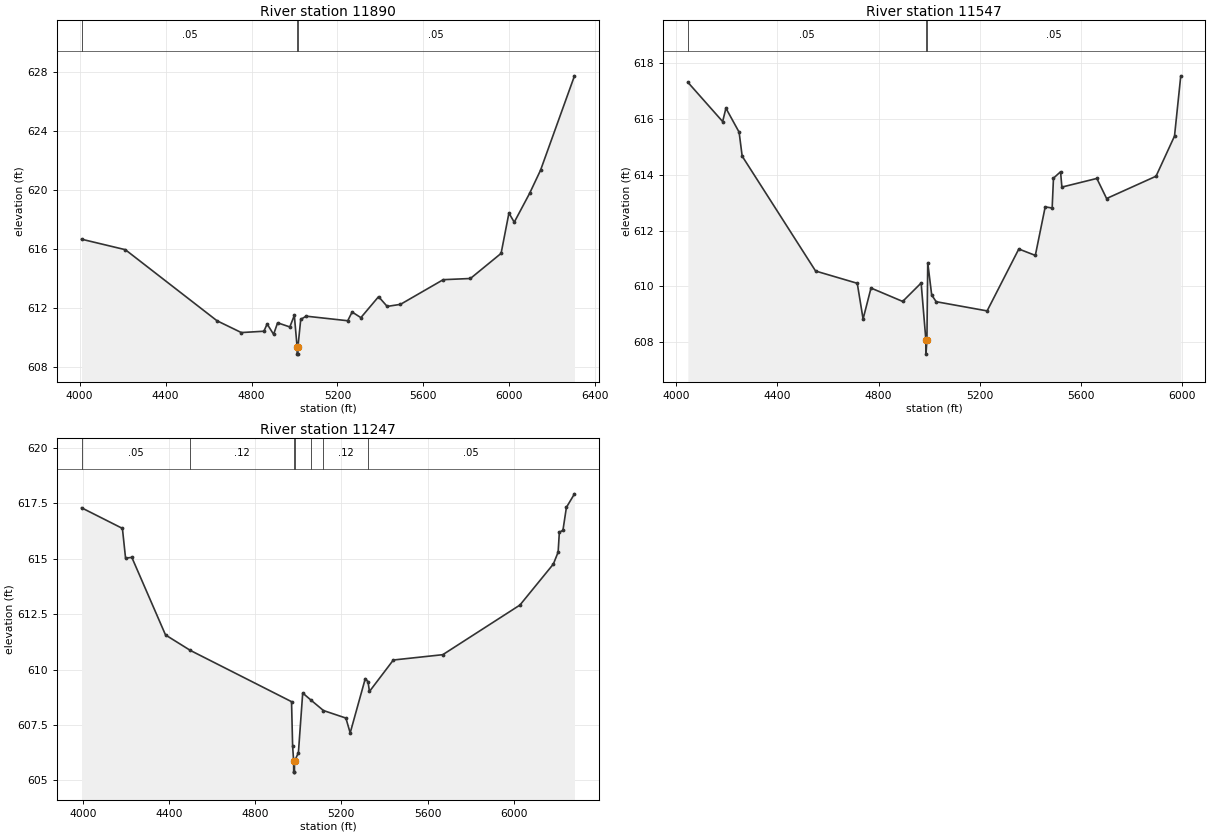
Type RM Length L Ch R = 1 ,11890   ,343,343,343
BEGIN DESCRIPTION:
LWE S 099 12.0
END DESCRIPTION:
XS GIS Cut Line= 4
      2339414.79      7083762.92      2339456.42      7082862.65
      2339524.07      7082763.78       2339274.3      7081514.95
#Sta/Elev= 30
  4008.8  616.68  4212.5  615.97  4639.2  611.16  4752.5  610.36  4857.6  610.45
  4872.6  610.94  4902.7  610.24  4921.4  611.02  4978.2  610.74  4999.2  611.52
  5012.1   609.4  5012.4   608.9  5015.9   608.9  5016.1   609.4    5029  611.25
  5054.1  611.47  5247.8  611.16  5268.2  611.75    5309  611.37  5391.4  612.79
  5431.4  612.13  5493.4  612.27  5692.3  613.94  5818.9  614.02  5961.7  615.72
  5998.2  618.45  6022.9  617.83  6094.3  619.78  6145.3  621.35  6303.4  627.74
#Mann= 3 ,-1 , 0
  4008.8     .05       0  5012.1    .033       0  5016.1     .05       0
Bank Sta=5012.1,5016.1
XS Rating Curve= 0 ,0
Exp/Cntr=0.3,0.1

Type RM Length L Ch R = 1 ,11547   ,300,300,300
BEGIN DESCRIPTION:
LWE S 099 11.0
END DESCRIPTION:
XS GIS Cut Line= 3
      2339534.48      7083674.42      2339753.03       7082930.3
      2339420.01      7081806.35
#Sta/Elev= 30
  4046.4  617.32    4184  615.91  4196.9  616.39    4249  615.53  4261.1  614.67
  4551.3  610.55  4715.9  610.11  4738.9  608.83  4770.2  609.94  4895.3  609.46
  4968.3  610.12  4987.1  608.07  4987.4  607.57  4991.1  608.07  4994.4  610.85
    5010  609.69  5027.7  609.45    5229  609.12  5354.2  611.34  5419.5  611.11
  5458.5  612.85    5486  612.81  5491.2  613.88  5519.2  614.11  5524.4  613.56
  5662.6  613.87  5701.1  613.15  5896.5  613.95  5969.5  615.39  5994.2  617.55
#Mann= 3 ,-1 , 0
  4046.4     .05       0  4987.1     .04       0  4991.1     .05       0
Bank Sta=4987.1,4991.1
XS Rating Curve= 0 ,0
Exp/Cntr=0.3,0.1

Type RM Length L Ch R = 1 ,11247   ,0,0,0
BEGIN DESCRIPTION:
LWE S 099 10.0
END DESCRIPTION:
XS GIS Cut Line= 4
      2339560.48      7083736.89      2339946.53      7083221.76
      2339981.99      7082545.23      2339539.69      7081686.65
#Sta/Elev= 30
  3994.6   617.3  4184.1  616.37  4198.7  615.03  4227.9  615.06  4384.2  611.56
  4499.9  610.86  4968.8  608.55  4973.8  606.55  4978.6  605.87  4978.8  605.37
  4982.3  605.37  4982.6  605.87  5000.6  606.24  5020.6  608.94  5059.1  608.62
  5116.8  608.15  5220.9  607.81  5240.9  607.14  5310.9  609.59  5323.6  609.45
  5330.3  609.01  5441.1  610.43  5670.4  610.67  6028.4  612.91  6183.5  614.76
  6205.7   615.3  6211.3   616.2  6227.9  616.28  6244.1  617.32  6281.6  617.93
#Mann= 7 ,-1 , 0
  3994.6     .05       0  4499.9     .12       0  4978.6     .07       0
  4982.6     .12       0  5059.1     .05       0  5116.8     .12       0
  5323.6     .05       0
Bank Sta=4978.6,4982.6
XS Rating Curve= 0 ,0
Exp/Cntr=0.3,0.1

Chan Stop Cuts=-1
Use User Specified Reach Order=0
Composite Channel Slope=5