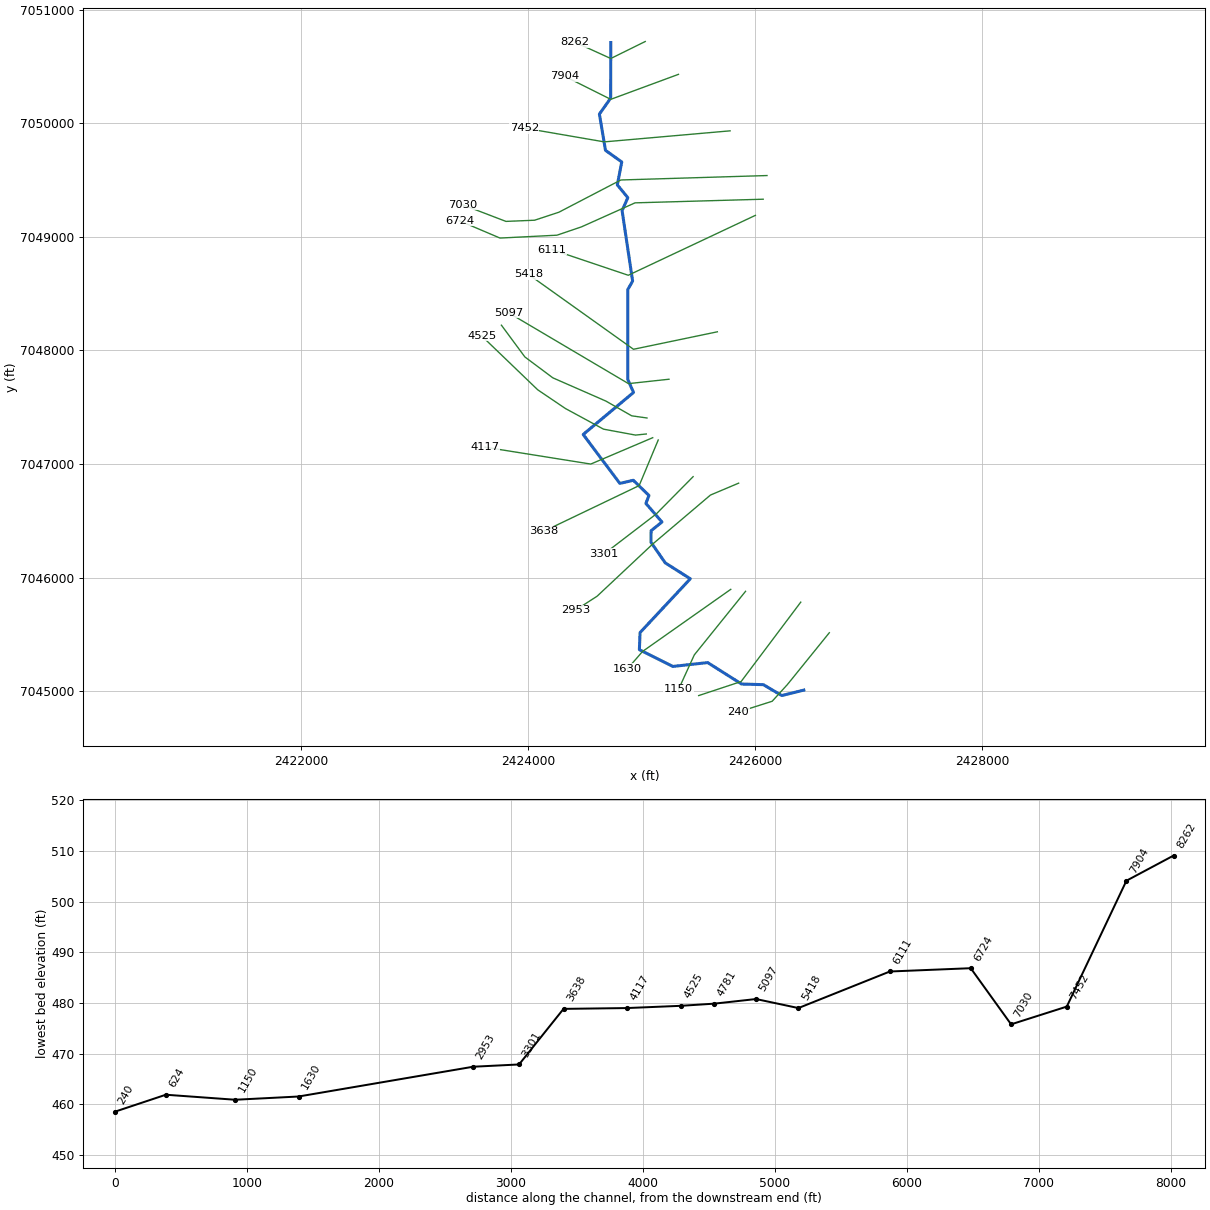
--- LWE S 103.prj (project) ---

Proj Title=LWE S 103 Base Level Engineering
Current Plan=p01
Default Exp/Contr=0.3,0.1
English Units
Geom File=g01
Flow File=f01
Plan File=p01
Y Axis Title=Elevation
X Axis Title(PF)=Main Channel Distance
X Axis Title(XS)=Station
BEGIN DESCRIPTION:
LWE S 103
END DESCRIPTION:
DSS Export Rating Curves= 0
DSS Export Rating Curve Sorted= 0
DSS Export Volume Flow Curves= 0
DXF OffsetX= 0
DXF OffsetY= 0
DXF ScaleX= 1
DXF ScaleY= 10

--- LWE S 103.p01 (plan) ---

Plan Title=Multiple Run
Short Identifier=Multiple
Geom File=g01
Flow File=f01
Subcritical Flow
K Sum by GR= 0
Std Step Tol= 0.01
Critical Tol= 0.01
Num of Std Step Trials= 20
Max Error Tol= 0.3
Flow Tol Ratio= 0.001
Split Flow NTrial= 30
Split Flow Tol= 0.02
Split Flow Ratio= 0.02
Log Output Level= 0
Friction Slope Method= 1
Unsteady Friction Slope Method= 2
Unsteady Bridges Friction Slope Method= 1
Parabolic Critical Depth
Global Vel Dist=  1 , 1 , 1
Global Log Level= 0
CheckData=True
Encroach Param= -1, 0, 0, 0
BEGIN DESCRIPTION:
Multiple Run
END DESCRIPTION:

--- LWE S 103.f01 (steady flow) ---

Flow Title=Multiple
Number of Profiles=7
Profile Names=10-year,25-year,50-year,1pct_min,100-year,1pct_plu,500-year
River Rch & RM= LWE S 103,Reach-1,8262
     361     480     576     343     685    1367     971
River Rch & RM= LWE S 103,Reach-1,5097
     586     796     966     582    1161    2316    1676
Boundary for River Rch & Prof#=LWE S 103,Reach-1,1
Up Type=0
Dn Type=3
Dn Slope=0.005
Boundary for River Rch & Prof#=LWE S 103,Reach-1,2
Up Type=0
Dn Type=3
Dn Slope=0.005
Boundary for River Rch & Prof#=LWE S 103,Reach-1,3
Up Type=0
Dn Type=3
Dn Slope=0.005
Boundary for River Rch & Prof#=LWE S 103,Reach-1,4
Up Type=0
Dn Type=3
Dn Slope=0.005
Boundary for River Rch & Prof#=LWE S 103,Reach-1,5
Up Type=0
Dn Type=3
Dn Slope=0.005
Boundary for River Rch & Prof#=LWE S 103,Reach-1,6
Up Type=0
Dn Type=3
Dn Slope=0.005
Boundary for River Rch & Prof#=LWE S 103,Reach-1,7
Up Type=0
Dn Type=3
Dn Slope=0.005

--- LWE S 103.g01 (geometry) ---

Geom Title=Existing Conditions
Program Version=4.10

River Reach=LWE S 103       ,Reach-1
Reach XY= 30
        2424729.        7050710.      2424727.94      7050220.44
      2424628.75      7050080.16      2424682.46      7049761.25
      2424825.56      7049658.75      2424786.81      7049456.59
      2424879.03      7049344.66      2424828.73      7049230.18
      2424921.44        7048610.      2424878.69      7048535.04
      2424878.58      7047744.82       2424929.4      7047630.13
      2424486.08        7047260.      2424808.97       7046829.3
      2424927.35      7046856.84      2425065.35      7046723.33
       2425038.3      7046653.33      2425179.57      7046489.58
      2425084.34      7046412.66      2425082.67      7046311.59
      2425208.87      7046129.77      2425429.52      7045989.94
      2424986.81      7045516.19      2424980.96      7045365.65
      2425275.77      7045218.24      2425582.41      7045252.19
      2425880.47      7045063.55      2426073.07      7045057.76
      2426234.96      7044962.14        2426429.        7045010.

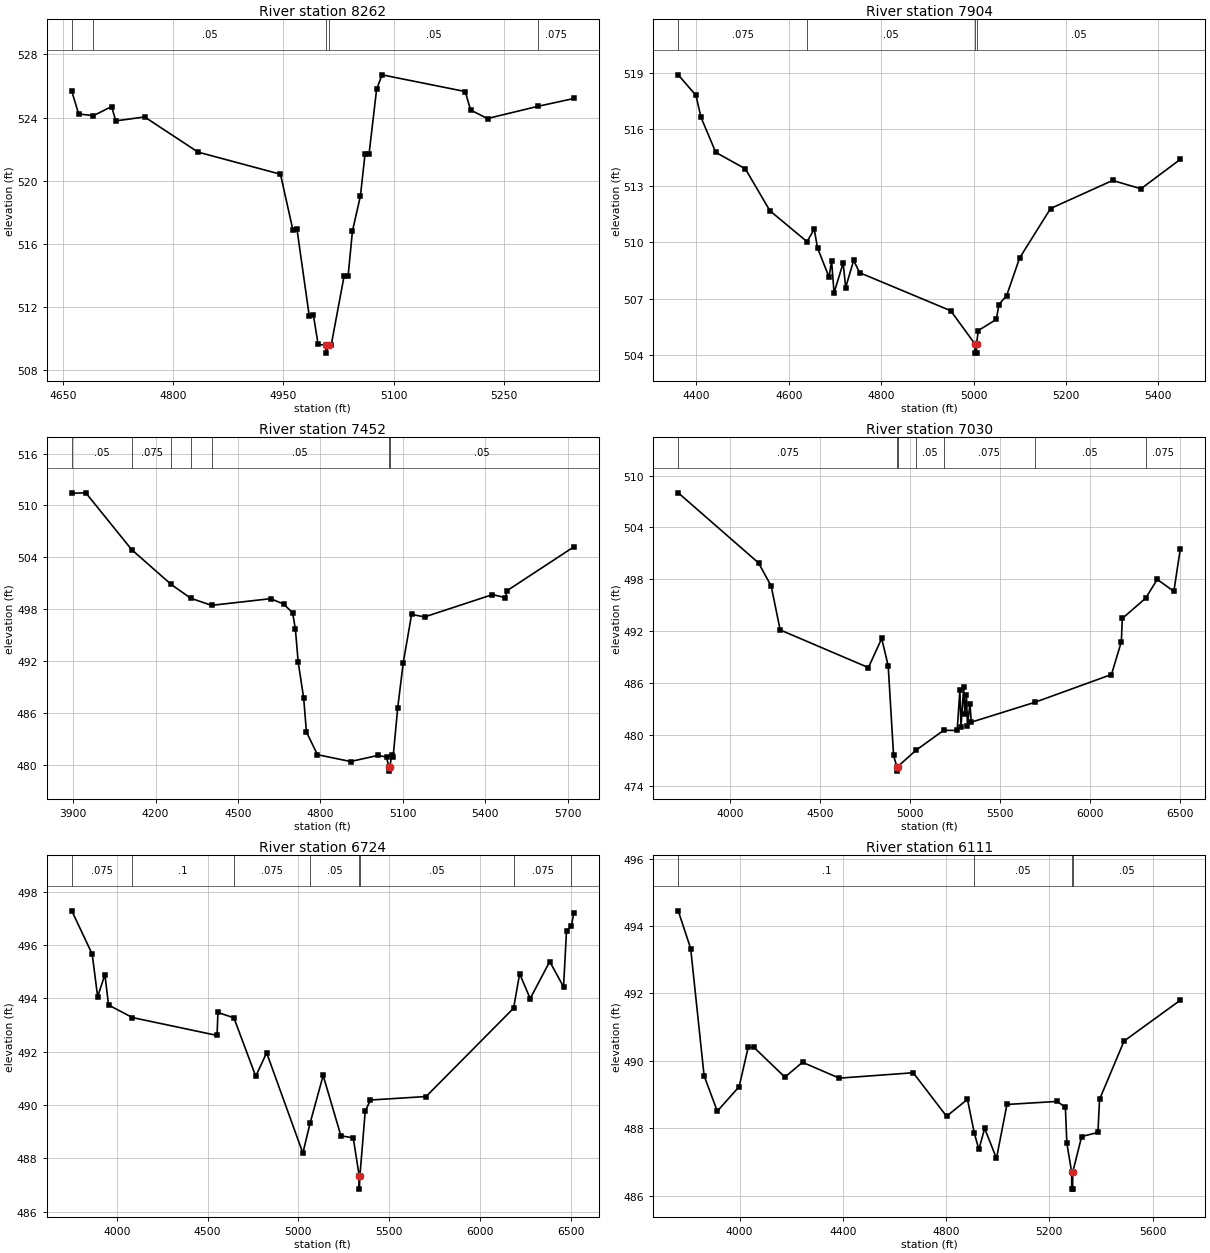
Type RM Length L Ch R = 1 ,8262    ,358,358,358
BEGIN DESCRIPTION:
LWE S 103 18.0
END DESCRIPTION:
XS GIS Cut Line= 3
      2425032.71      7050719.06      2424729.01      7050569.34
      2424414.26      7050712.57
#Sta/Elev= 30
  4661.4  525.67  4670.8  524.23  4690.8  524.12  4715.8   524.7  4721.3  523.79
  4760.7  524.04  4833.6  521.81  4945.9  520.41  4962.8  516.88  4968.4  516.92
  4985.2   511.4  4990.8  511.47  4997.2  509.63  5007.6  509.57  5007.8  509.07
  5011.6  509.57  5015.1  509.59  5032.6  513.95  5038.1  513.96    5044  516.81
  5054.9  519.04  5061.2  521.71  5066.7  521.71  5076.9  525.78  5084.3  526.71
  5197.8  525.65    5205  524.48  5228.1  523.94  5297.4  524.72  5345.8  525.21
#Mann= 5 ,-1 , 0
  4661.4    .075       0  4690.8     .05       0  5007.6    .033       0
  5011.6     .05       0  5297.4    .075       0
Bank Sta=5007.6,5011.6
XS Rating Curve= 0 ,0
Exp/Cntr=0.3,0.1

Type RM Length L Ch R = 1 ,7904    ,452,452,452
BEGIN DESCRIPTION:
LWE S 103 17.0
END DESCRIPTION:
XS GIS Cut Line= 3
      2425325.24        7050430.        2424729.        7050210.
      2424325.25       7050411.8
#Sta/Elev= 30
  4360.6  518.88  4398.9  517.79  4409.9  516.62  4441.9  514.76  4505.8  513.89
  4559.1  511.66  4639.4  510.02    4655  510.68  4662.1  509.69    4687  508.14
  4692.6  508.99  4697.9   507.3  4717.7  508.89    4723  507.58  4740.3  509.02
  4753.4  508.37  4950.5  506.35  5002.5   504.6  5002.8   504.1  5006.3   504.1
  5006.5   504.6  5010.1   505.3  5049.2  505.89  5054.8  506.68  5071.6  507.16
  5099.6  509.15  5166.6  511.78  5300.8  513.27  5362.3  512.83  5447.5  514.39
#Mann= 4 ,-1 , 0
  4360.6    .075       0  4639.4     .05       0  5002.5    .033       0
  5006.5     .05       0
Bank Sta=5002.5,5006.5
XS Rating Curve= 0 ,0
Exp/Cntr=0.3,0.1

Type RM Length L Ch R = 1 ,7452    ,422,422,422
BEGIN DESCRIPTION:
LWE S 103 15.0
END DESCRIPTION:
XS GIS Cut Line= 3
      2425779.77      7049932.72      2424672.12       7049835.5
      2423967.23      7049957.03
#Sta/Elev= 30
    3895  511.41    3946  511.46    4113  504.89  4257.1  500.86    4328  499.27
  4403.8  498.45  4618.5  499.22  4666.6  498.59  4698.8  497.58  4708.9  495.68
  4718.9  491.91    4739  487.72    4749   483.8  4789.2  481.18  4909.7  480.39
    5011  481.11  5040.5  480.89  5048.7  479.78  5048.9  479.28  5052.7  479.78
  5059.3  481.15  5064.4  480.88  5081.1  486.57  5101.4  491.84  5131.8   497.4
    5179  497.11  5426.1  499.69  5473.3  499.34  5478.4  500.13  5722.2  505.21
#Mann= 7 ,-1 , 0
    3895     .05       0    4113    .075       0  4257.1     .05       0
    4328    .075       0  4403.8     .05       0  5048.7    .033       0
  5052.7     .05       0
Bank Sta=5048.7,5052.7
XS Rating Curve= 0 ,0
Exp/Cntr=0.3,0.1

Type RM Length L Ch R = 1 ,7030    ,306,306,306
BEGIN DESCRIPTION:
LWE S 103 14.0
END DESCRIPTION:
XS GIS Cut Line= 6
      2426105.18      7049539.21      2424817.77       7049500.2
       2424271.9      7049216.29      2424058.35      7049145.98
      2423805.75      7049135.56      2423425.52       7049281.4
#Sta/Elev= 30
    3712  508.01  4158.4  499.89  4228.4  497.22  4278.4  492.13  4768.7  487.77
  4842.6  491.14  4878.7  487.98  4908.7   477.6  4926.7  476.28    4927  475.78
  4930.7  476.28  5032.2  478.18  5187.1  480.51    5262  480.49  5277.2  485.17
  5283.1  480.88  5298.3  485.54  5304.3  482.36  5313.5  484.59  5319.4  481.05
  5332.9  483.56  5340.5  481.45  5692.2  483.74  6119.6  486.97  6174.3  490.77
  6179.6  493.46    6309   495.8  6373.8  497.98  6466.1   496.6    6502  501.52
#Mann= 7 ,-1 , 0
    3712    .075       0  4926.7     .07       0  4930.7    .075       0
  5032.2     .05       0  5187.1    .075       0  5692.2     .05       0
    6309    .075       0
Bank Sta=4926.7,4930.7
XS Rating Curve= 0 ,0
Exp/Cntr=0.3,0.1

Type RM Length L Ch R = 1 ,6724    ,613,613,613
BEGIN DESCRIPTION:
LWE S 103 13.0
END DESCRIPTION:
XS GIS Cut Line= 6
      2426071.35      7049330.88      2424942.69      7049298.87
      2424471.47      7049087.61      2424255.23      7049014.21
      2423753.58       7048988.9      2423396.85      7049140.79
#Sta/Elev= 30
  3752.5  497.28  3864.9  495.66    3895  494.06    3935  494.89    3955  493.75
  4086.5  493.28  4552.4  492.61  4557.4  493.47  4645.2  493.27  4765.5  491.08
  4825.5  491.96    5025   488.2  5064.3  489.31  5136.8  491.11  5234.4  488.85
  5302.3  488.77  5335.1  487.35  5335.4  486.85  5339.1  487.35  5368.4  489.77
  5397.3  490.19  5703.4  490.32  6185.2  493.63  6218.7  494.92  6276.8  493.99
  6384.3  495.38  6460.4  494.43  6476.8  496.53  6503.3  496.71  6517.1  497.21
#Mann= 8 ,-1 , 0
  3752.5    .075       0  4086.5      .1       0  4645.2    .075       0
  5064.3     .05       0  5335.1     .07       0  5339.1     .05       0
  6185.2    .075       0  6503.3     .05       0
Bank Sta=5335.1,5339.1
XS Rating Curve= 0 ,0
Exp/Cntr=0.3,0.1

Type RM Length L Ch R = 1 ,6111    ,693,693,693
BEGIN DESCRIPTION:
LWE S 103 11.0
END DESCRIPTION:
XS GIS Cut Line= 3
      2426002.59      7049188.68      2424883.01      7048661.47
      2424212.45      7048887.08
#Sta/Elev= 30
  3762.5  494.45  3810.7  493.33  3862.7  489.56  3913.8  488.51  3998.6  489.24
  4033.3   490.4  4056.1   490.4  4175.6  489.52  4243.9  489.96  4386.2  489.49
  4672.8  489.65  4801.9  488.36  4882.9  488.86  4909.8  487.85  4927.1  487.38
  4949.7     488  4995.3  487.11  5035.9  488.71  5230.8   488.8  5262.3  488.62
    5268  487.56  5286.6   486.7  5286.8   486.2  5290.3   486.2  5290.6   486.7
  5325.4  487.76  5388.4  487.88  5394.6  488.86  5489.6  490.59  5707.5   491.8
#Mann= 4 ,-1 , 0
  3762.5      .1       0  4909.8     .05       0  5286.6     .05       0
  5290.6     .05       0
Bank Sta=5286.6,5290.6
XS Rating Curve= 0 ,0
Exp/Cntr=0.3,0.1

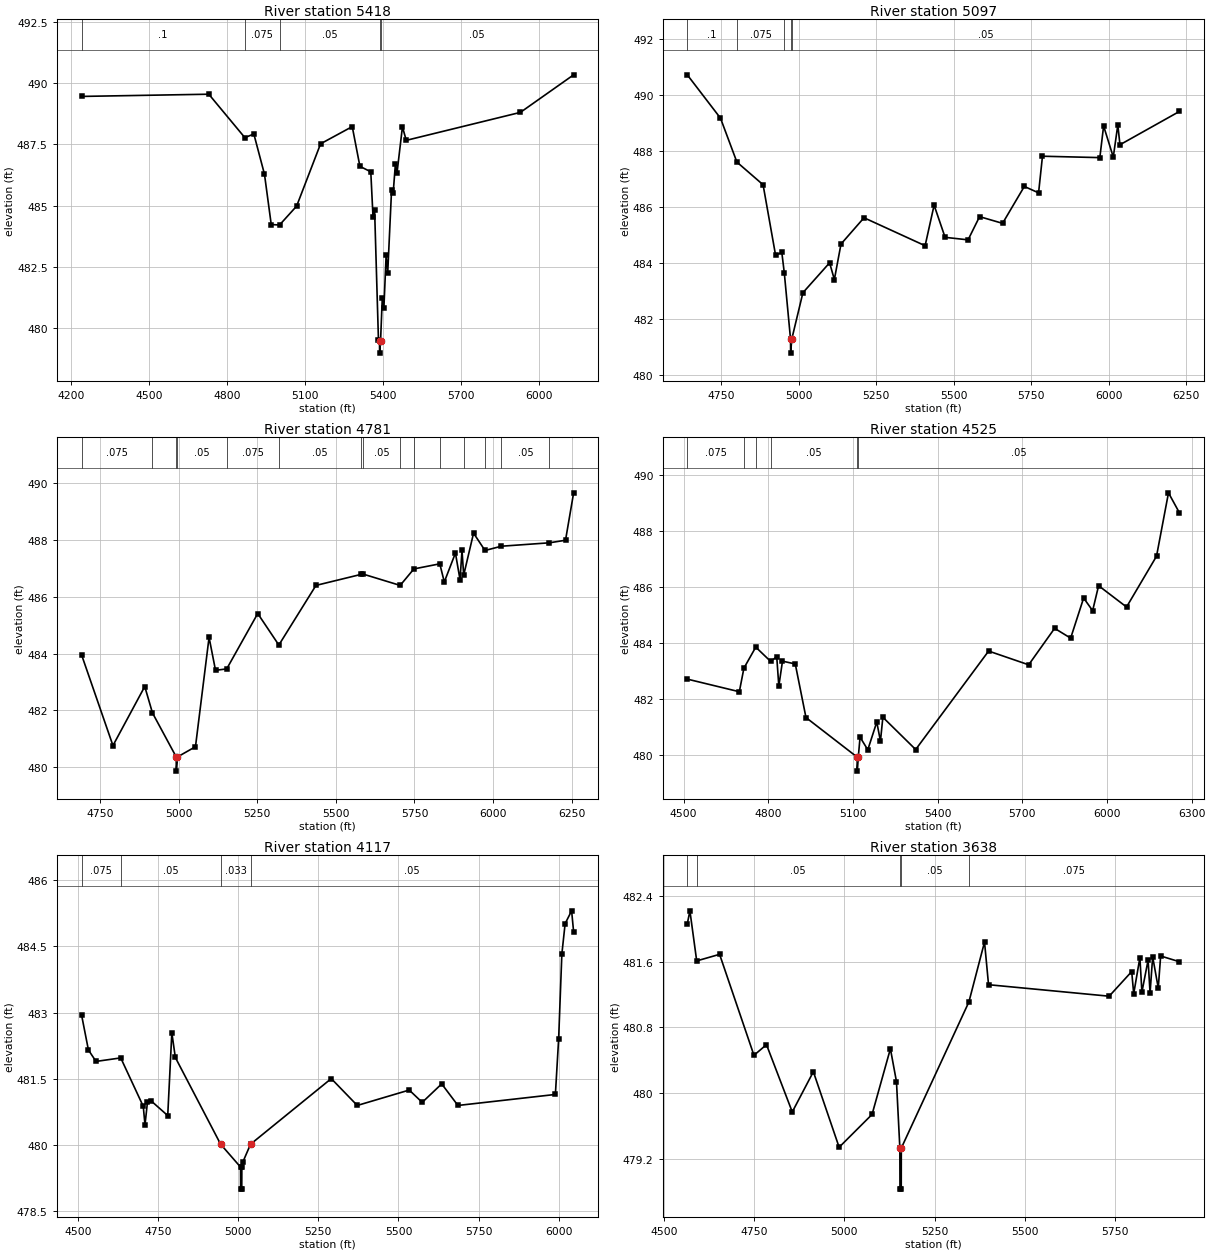
Type RM Length L Ch R = 1 ,5418    ,321,321,321
BEGIN DESCRIPTION:
LWE S 103 10.0
END DESCRIPTION:
XS GIS Cut Line= 3
       2425667.7       7048163.8        2424929.        7048010.
      2424002.59      7048670.49
#Sta/Elev= 30
  4241.2  489.45  4730.6  489.54  4869.3  487.77  4903.8  487.92  4944.7  486.28
  4970.7  484.23  5002.5  484.21  5068.3  484.98  5160.5  487.52  5282.2  488.22
  5311.7   486.6  5353.5  486.38  5362.1  484.53  5368.2  484.82    5383  479.53
  5387.1  479.49  5387.4  478.99  5391.1  479.49  5397.7  481.22  5403.9  480.83
  5412.5  482.98  5418.6  482.26  5433.4  485.64  5439.5   485.5  5448.1  486.69
  5454.3  486.33  5475.2  488.21  5489.9  487.66  5928.8   488.8  6133.5  490.33
#Mann= 5 ,-1 , 0
  4241.2      .1       0  4869.3    .075       0  5002.5     .05       0
  5387.1     .07       0  5391.1     .05       0
Bank Sta=5387.1,5391.1
XS Rating Curve= 0 ,0
Exp/Cntr=0.3,0.1

Type RM Length L Ch R = 1 ,5097    ,316,316,316
BEGIN DESCRIPTION:
LWE S 103 9.0
END DESCRIPTION:
XS GIS Cut Line= 3
      2425241.99      7047746.38      2424884.79      7047707.65
      2423828.12      7048331.93
#Sta/Elev= 30
  4640.7  490.72  4747.8  489.17  4800.7   487.6  4885.1  486.79  4925.4  484.27
  4945.5  484.37  4953.5  483.64  4973.6  481.27  4973.9  480.77  4977.6  481.27
  5013.5  482.93  5099.6     484  5114.9   483.4  5136.3  484.67  5210.5  485.61
  5407.5  484.61  5436.5  486.06  5471.9  484.91    5546  484.82  5583.1  485.65
  5657.2  485.41  5727.4  486.73  5773.3   486.5  5785.9  487.81  5970.8  487.76
    5983  488.89  6014.2  487.78  6028.8  488.93  6035.7  488.22  6227.3  489.41
#Mann= 5 ,-1 , 0
  4640.7      .1       0  4800.7    .075       0  4953.5     .05       0
  4973.6    .033       0  4977.6     .05       0
Bank Sta=4973.6,4977.6
XS Rating Curve= 0 ,0
Exp/Cntr=0.3,0.1

Type RM Length L Ch R = 1 ,4781    ,256,256,256
BEGIN DESCRIPTION:
Mapping XS 69a566db
END DESCRIPTION:
XS GIS Cut Line= 6
      2425047.92      7047405.24      2424913.48      7047424.17
       2424685.4      7047554.38      2424218.99      7047758.53
      2423972.47      7047942.55      2423765.89      7048222.04
#Sta/Elev= 30
  4691.7  483.96  4791.6  480.76  4892.7  482.84  4917.2  481.91  4992.7  480.36
    4993  479.86  4996.7  480.36  5053.9  480.72  5097.1  484.57  5117.6  483.41
  5153.2  483.46  5251.8  485.41  5318.9   484.3  5436.9   486.4  5581.1  486.79
  5586.2   486.8  5704.5   486.4  5748.1  486.98  5830.5  487.16  5844.8  486.52
  5880.2  487.54  5894.8   486.6  5901.1  487.63  5906.4  486.76  5937.8  488.24
  5974.2  487.63  6026.4  487.78  6178.8   487.9  6230.1  487.99  6255.9  489.66
#Mann= 15 ,-1 , 0
  4691.7    .075       0  4917.2     .05       0  4992.7    .033       0
  4996.7     .05       0  5153.2    .075       0  5318.9     .05       0
  5581.1    .075       0  5586.2     .05       0  5704.5    .075       0
  5748.1     .05       0  5830.5    .075       0  5906.4     .05       0
  5974.2    .075       0  6026.4     .05       0  6178.8    .075       0
Bank Sta=4992.7,4996.7
XS Rating Curve= 0 ,0
Exp/Cntr=0.3,0.1

Type RM Length L Ch R = 1 ,4525    ,408,408,408
BEGIN DESCRIPTION:
Mapping XS 183ba48d
END DESCRIPTION:
XS GIS Cut Line= 6
      2425041.94      7047264.39      2424946.43      7047254.76
      2424664.78      7047306.98      2424328.41      7047489.27
       2424085.2      7047653.67      2423591.95      7048127.62
#Sta/Elev= 30
  4513.3  482.71  4697.7  482.26  4713.9   483.1  4755.9  483.85  4808.8  483.34
  4830.2  483.51  4837.6  482.46  4850.6  483.35  4895.9  483.25  4933.8  481.34
  5115.1  479.93  5115.4  479.43  5119.1  479.93  5125.4  480.64  5152.8  480.19
  5184.6  481.18  5197.6   480.5  5206.2  481.35  5322.4   480.2  5580.8  483.71
  5722.7  483.22  5814.6  484.52  5871.4  484.17  5917.4   485.6  5949.3  485.15
  5970.4  486.04  6069.4  485.28  6175.6  487.09    6218  489.35  6256.6  488.64
#Mann= 6 ,-1 , 0
  4513.3    .075       0  4713.9     .05       0  4755.9    .075       0
  4808.8     .05       0  5115.1    .033       0  5119.1     .05       0
Bank Sta=5115.1,5119.1
XS Rating Curve= 0 ,0
Exp/Cntr=0.3,0.1

Type RM Length L Ch R = 1 ,4117    ,479,479,479
BEGIN DESCRIPTION:
LWE S 103 8.0
END DESCRIPTION:
XS GIS Cut Line= 3
      2425098.14      7047231.59      2424552.86      7046999.66
      2423622.79      7047148.08
#Sta/Elev= 30
  4511.8  482.95  4533.3  482.15    4557  481.89  4634.1  481.97  4704.3  480.87
  4709.7  480.45  4717.3  480.96  4727.9     481  4780.6  480.66  4793.4  482.54
  4804.3  481.98  4945.5  480.01  5007.7  479.49  5007.9  478.99  5011.4  478.99
  5011.7  479.49  5015.1  479.61  5038.8  480.01  5290.5   481.5  5371.6  480.89
  5533.6  481.24  5574.1  480.96  5634.8  481.38  5685.5  480.89  5989.3  481.14
  5999.4  482.39  6009.5  484.33  6019.7  485.02  6039.9  485.31  6046.2  484.83
#Mann= 4 ,-1 , 0
  4511.8    .075       0  4634.1     .05       0  4945.5    .033       0
  5038.8     .05       0
Bank Sta=4945.5,5038.8
XS Rating Curve= 0 ,0
Exp/Cntr=0.3,0.1

Type RM Length L Ch R = 1 ,3638    ,337,337,337
BEGIN DESCRIPTION:
LWE S 103 7.0
END DESCRIPTION:
XS GIS Cut Line= 3
      2425146.92      7047211.52        2424979.        7046810.
      2424142.23      7046409.24
#Sta/Elev= 30
  4565.1  482.06  4572.4  482.22  4591.2  481.61  4654.6  481.69  4749.8  480.46
  4784.5  480.59  4855.9  479.77  4914.3  480.26  4985.7  479.34  5076.9  479.74
  5127.7  480.54  5144.5  480.14  5153.9  479.33  5154.2  478.83  5157.7  478.83
  5157.9  479.33  5345.1  481.11  5388.4  481.84  5399.5  481.32  5733.6  481.18
    5796  481.48  5801.6  481.21  5818.7  481.65  5824.3  481.23  5841.4  481.62
  5846.9  481.22  5854.1  481.66  5869.6  481.28  5876.2  481.67  5928.1   481.6
#Mann= 5 ,-1 , 0
  4565.1    .075       0  4591.2     .05       0  5153.9     .05       0
  5157.9     .05       0  5345.1    .075       0
Bank Sta=5153.9,5157.9
XS Rating Curve= 0 ,0
Exp/Cntr=0.3,0.1

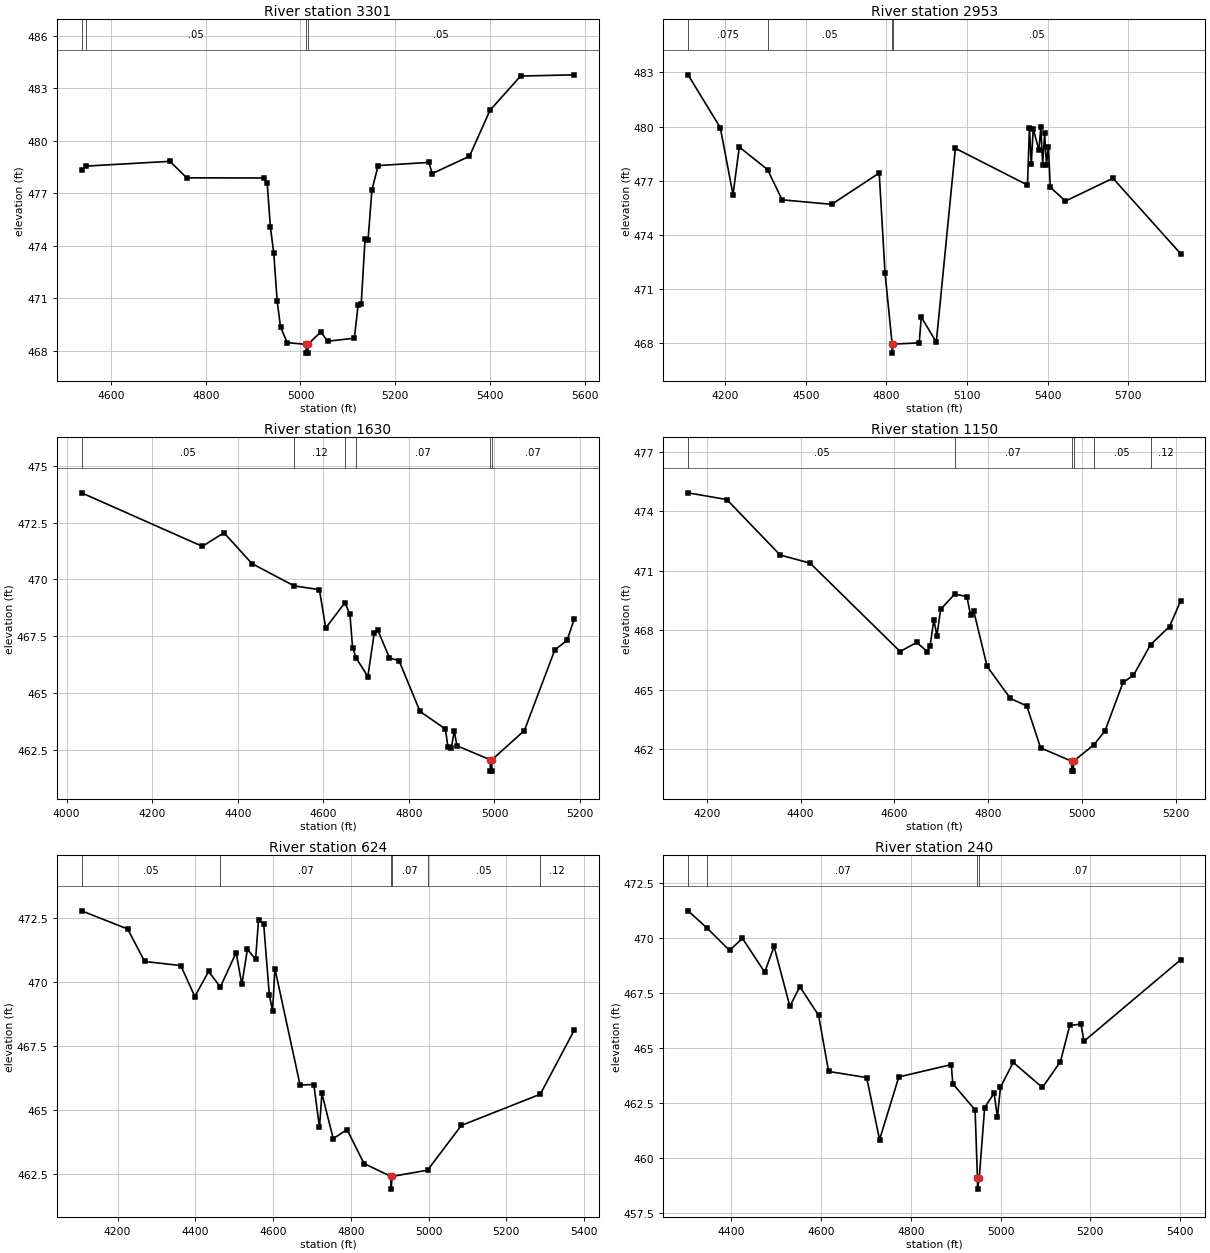
Type RM Length L Ch R = 1 ,3301    ,348,348,348
BEGIN DESCRIPTION:
LWE S 103 6.0
END DESCRIPTION:
XS GIS Cut Line= 3
      2425454.18      7046888.56        2425129.        7046560.
      2424670.34      7046208.88
#Sta/Elev= 30
    4538  478.32  4548.2  478.55  4724.5  478.82  4759.9  477.88  4922.5  477.87
  4929.6  477.61  4936.6  475.06  4943.7  473.56  4950.8  470.84  4957.9  469.36
    4972  468.47  5011.8  468.37  5012.1  467.87  5015.6  467.87  5015.8  468.37
  5042.9  469.08  5057.4  468.55  5113.6  468.72  5121.8  470.63  5128.1  470.65
  5136.3  474.36  5142.6  474.32  5150.8   477.2    5164  478.58  5271.4  478.76
  5277.7  478.12  5356.6  479.11  5400.1  481.74  5464.5  483.69  5577.9  483.76
#Mann= 4 ,-1 , 0
    4538    .075       0  4548.2     .05       0  5011.8     .05       0
  5015.8     .05       0
Bank Sta=5011.8,5015.8
XS Rating Curve= 0 ,0
Exp/Cntr=0.3,0.1

Type RM Length L Ch R = 1 ,2953    ,1323,1323,1323
BEGIN DESCRIPTION:
LWE S 103 5.0
END DESCRIPTION:
XS GIS Cut Line= 5
      2425855.04      7046831.57      2425606.94      7046726.86
      2425095.78       7046293.4      2424608.98      7045836.72
      2424416.57      7045712.33
#Sta/Elev= 30
  4060.5  482.87  4180.7  479.94  4228.1  476.22  4251.6  478.86  4356.8  477.61
  4411.1  475.93  4595.7  475.68  4772.9  477.42  4794.5  471.89  4821.1  467.92
  4821.4  467.42  4825.1  467.92  4921.9  467.99  4929.7  469.42  4985.6  468.03
  5056.7  478.79  5325.4  476.75  5332.7  479.92  5339.5  477.91  5346.8  479.87
  5367.9   478.7  5375.2  479.95    5382  477.87  5389.3  479.63  5396.2  477.86
  5403.5  478.89  5410.3  476.63    5467  475.86  5643.8  477.13  5896.6  472.93
#Mann= 4 ,-1 , 0
  4060.5    .075       0  4356.8     .05       0  4821.1     .05       0
  4825.1     .05       0
Bank Sta=4821.1,4825.1
XS Rating Curve= 0 ,0
Exp/Cntr=0.3,0.1

Type RM Length L Ch R = 1 ,1630    ,480,480,480
BEGIN DESCRIPTION:
Mapping XS ed1787c3
END DESCRIPTION:
XS GIS Cut Line= 3
      2425785.76      7045896.96      2425008.81      7045350.05
      2424876.45      7045198.03
#Sta/Elev= 30
  4034.9  473.82  4317.3  471.46  4367.8  472.06  4433.1   470.7  4531.5  469.72
  4590.8  469.55  4605.6  467.86  4650.6  468.98  4662.2  468.46  4668.3     467
  4676.9  466.53  4704.1  465.72  4718.9  467.63  4727.5  467.76  4754.6  466.54
  4776.9  466.42    4826  464.18  4885.2  463.41  4891.3  462.61  4899.2  462.58
  4906.1  463.32  4912.2  462.67    4990  462.05  4990.3  461.55  4993.8  461.55
    4994  462.05  5069.9  463.34  5141.1   466.9  5169.6  467.31  5186.6  468.27
#Mann= 6 ,-1 , 0
  4034.9     .05       0  4531.5     .12       0  4650.6     .05       0
  4676.9     .07       0    4990    .033       0    4994     .07       0
Bank Sta=4990,4994
XS Rating Curve= 0 ,0
Exp/Cntr=0.3,0.1

Type RM Length L Ch R = 1 ,1150    ,526,526,526
BEGIN DESCRIPTION:
Mapping XS d96a11a5
END DESCRIPTION:
XS GIS Cut Line= 3
      2425915.92      7045879.55      2425464.54      7045319.67
      2425326.63      7045018.19
#Sta/Elev= 30
  4159.8  474.92  4242.6  474.58  4356.2  471.79  4420.2  471.38  4612.1  466.93
  4647.3  467.39  4669.7  466.93  4676.1  467.22    4684  468.54  4690.5  467.73
  4698.4  469.05  4728.3  469.82  4754.4   469.7  4762.4  468.75  4768.8  468.99
  4797.6  466.18  4847.2  464.57  4882.2  464.19  4911.6  462.08  4977.8  461.41
    4978  460.91  4981.5  460.91  4981.8  461.41  5025.3  462.24  5048.8  462.93
  5087.5  465.38  5109.5  465.73  5146.2  467.28  5186.5  468.19  5210.5  469.49
#Mann= 6 ,-1 , 0
  4159.8     .05       0  4728.3     .07       0  4977.8    .033       0
  4981.8     .07       0  5025.3     .05       0  5146.2     .12       0
Bank Sta=4977.8,4981.8
XS Rating Curve= 0 ,0
Exp/Cntr=0.3,0.1

Type RM Length L Ch R = 1 ,624     ,384,384,384
BEGIN DESCRIPTION:
Mapping XS 7836f9ec
END DESCRIPTION:
XS GIS Cut Line= 3
      2426402.04      7045784.08      2425876.87       7045085.3
      2425503.11      7044961.66
#Sta/Elev= 30
  4107.2  472.78  4225.8  472.07  4269.5   470.8  4362.5  470.64  4398.6  469.43
  4434.1  470.41  4464.3   469.8  4504.9  471.15  4519.5   469.9    4534  471.28
  4554.9  470.88  4562.6  472.43  4575.7  472.28  4590.3  469.49  4598.6  468.88
  4604.8  470.51  4669.4  465.97  4704.8  465.99  4719.4  464.31  4725.6  465.64
  4754.8  463.87  4790.2  464.23  4833.9   462.9  4902.8   462.4    4903   461.9
  4906.8   462.4  4997.4  462.64  5084.4  464.39  5287.5  465.61    5375  468.12
#Mann= 6 ,-1 , 0
  4107.2     .05       0  4464.3     .07       0  4902.8    .033       0
  4906.8     .07       0  4997.4     .05       0  5287.5     .12       0
Bank Sta=4902.8,4906.8
XS Rating Curve= 0 ,0
Exp/Cntr=0.3,0.1

Type RM Length L Ch R = 1 ,240     ,0,0,0
BEGIN DESCRIPTION:
LWE S 103 4.0
END DESCRIPTION:
XS GIS Cut Line= 4
      2426653.75      7045514.95      2426284.85      7045059.26
       2426150.3      7044911.69      2425853.47      7044817.19
#Sta/Elev= 30
    4304  471.22  4347.3  470.42  4396.5  469.42  4425.2  469.97  4474.8  468.43
  4495.6   469.6  4530.8  466.88  4553.1  467.77  4594.8  466.47  4617.1  463.92
  4701.9  463.64  4730.6  460.82  4773.5  463.67  4890.3  464.23  4893.8  463.36
  4943.4  462.17  4948.6  459.07  4948.8  458.57  4952.6  459.07  4964.7  462.28
  4985.7  462.93  4993.1  461.84  4999.9   463.2  5028.3  464.33  5093.3  463.19
  5133.3  464.36  5154.3  466.01  5179.3  466.07  5185.8  465.29  5401.5     469
#Mann= 4 ,-1 , 0
    4304     .05       0  4347.3     .07       0  4948.6    .033       0
  4952.6     .07       0
Bank Sta=4948.6,4952.6
XS Rating Curve= 0 ,0
Exp/Cntr=0.3,0.1

Chan Stop Cuts=-1
Use User Specified Reach Order=0
Composite Channel Slope=5