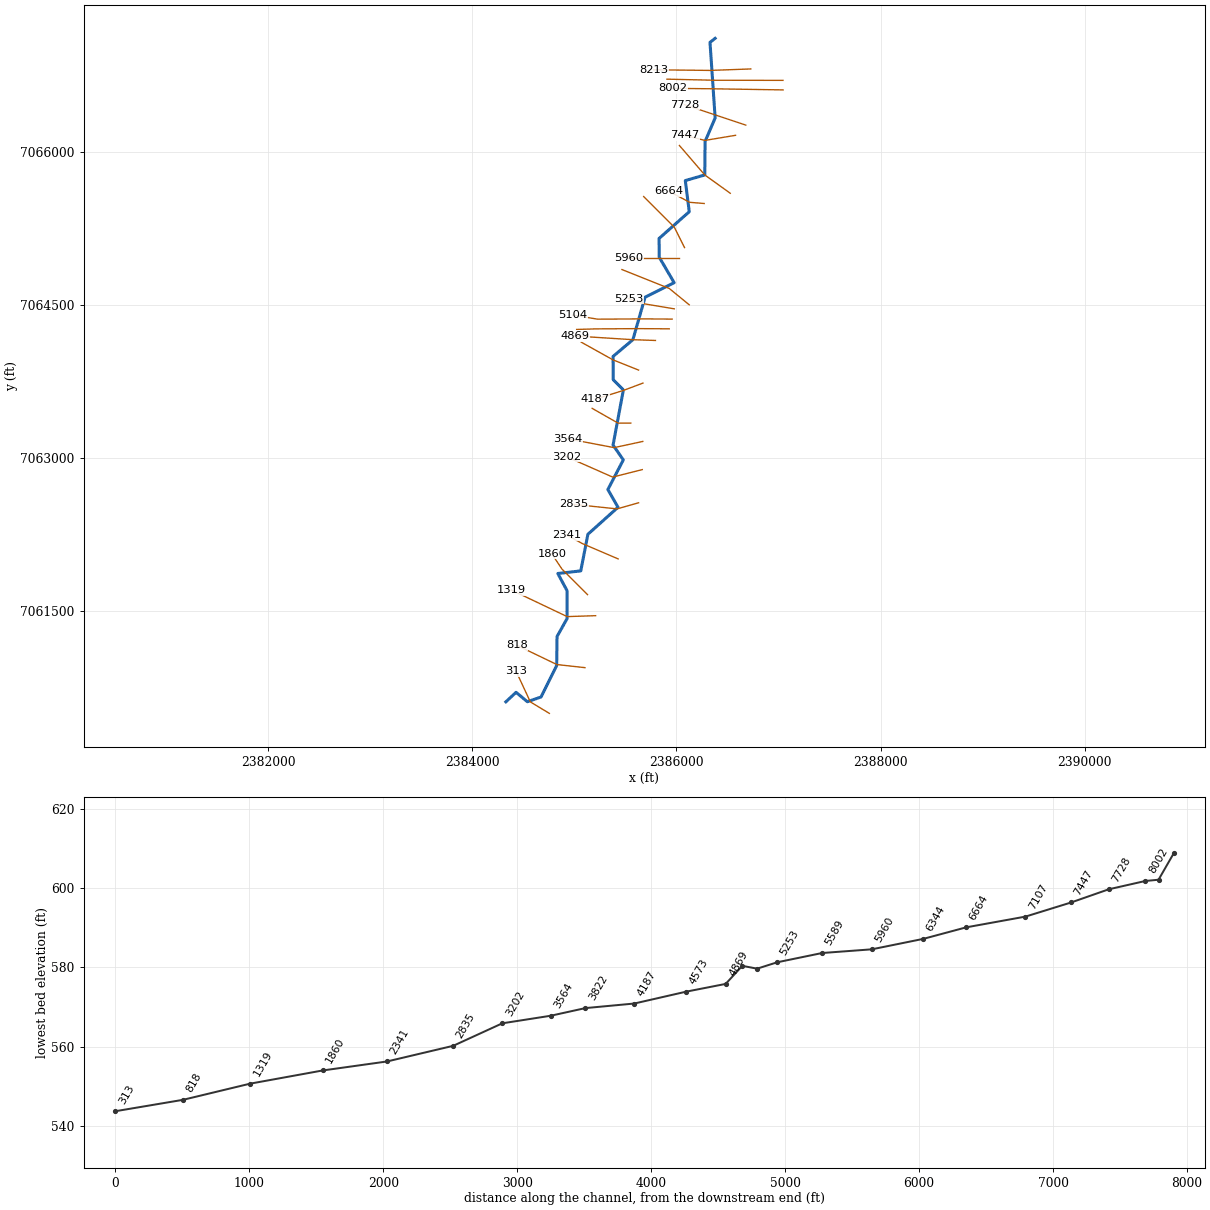
--- LWE S SB_1.prj (project) ---

Proj Title=LWE S SB_1 Base Level Engineering
Current Plan=p01
Default Exp/Contr=0.3,0.1
English Units
Geom File=g01
Flow File=f01
Plan File=p01
Y Axis Title=Elevation
X Axis Title(PF)=Main Channel Distance
X Axis Title(XS)=Station
BEGIN DESCRIPTION:
LWE S SB_1
END DESCRIPTION:
DSS Export Rating Curves= 0
DSS Export Rating Curve Sorted= 0
DSS Export Volume Flow Curves= 0
DXF OffsetX= 0
DXF OffsetY= 0
DXF ScaleX= 1
DXF ScaleY= 10

--- LWE S SB_1.p01 (plan) ---

Plan Title=Multiple Run
Short Identifier=Multiple
Geom File=g01
Flow File=f01
Subcritical Flow
K Sum by GR= 0
Std Step Tol= 0.01
Critical Tol= 0.01
Num of Std Step Trials= 20
Max Error Tol= 0.3
Flow Tol Ratio= 0.001
Split Flow NTrial= 30
Split Flow Tol= 0.02
Split Flow Ratio= 0.02
Log Output Level= 0
Friction Slope Method= 1
Unsteady Friction Slope Method= 2
Unsteady Bridges Friction Slope Method= 1
Parabolic Critical Depth
Global Vel Dist=  1 , 1 , 1
Global Log Level= 0
CheckData=True
Encroach Param= -1, 0, 0, 0
BEGIN DESCRIPTION:
Multiple Run
END DESCRIPTION:

--- LWE S SB_1.f01 (steady flow) ---

Flow Title=Multiple
Number of Profiles=7
Profile Names=10-year,25-year,50-year,1pct_min,100-year,1pct_plu,500-year
River Rch & RM= LWE S SB_1,Reach-1,8213
     569     782     960     586    1169    2332    1735
River Rch & RM= LWE S SB_1,Reach-1,7107
     753    1046    1292     792    1581    3154    2372
Boundary for River Rch & Prof#=LWE S SB_1,Reach-1,1
Up Type=0
Dn Type=3
Dn Slope=0.005
Boundary for River Rch & Prof#=LWE S SB_1,Reach-1,2
Up Type=0
Dn Type=3
Dn Slope=0.005
Boundary for River Rch & Prof#=LWE S SB_1,Reach-1,3
Up Type=0
Dn Type=3
Dn Slope=0.005
Boundary for River Rch & Prof#=LWE S SB_1,Reach-1,4
Up Type=0
Dn Type=3
Dn Slope=0.005
Boundary for River Rch & Prof#=LWE S SB_1,Reach-1,5
Up Type=0
Dn Type=3
Dn Slope=0.005
Boundary for River Rch & Prof#=LWE S SB_1,Reach-1,6
Up Type=0
Dn Type=3
Dn Slope=0.005
Boundary for River Rch & Prof#=LWE S SB_1,Reach-1,7
Up Type=0
Dn Type=3
Dn Slope=0.005

--- LWE S SB_1.g01 (geometry) ---

Geom Title=Existing Conditions

River Reach=LWE S SB_1,Reach-1
Reach XY= 30
      2386379.00      7067110.00      2386328.55      7067070.45
      2386378.93      7066330.03      2386280.22      7066099.50
      2386277.52      7065771.49      2386086.62      7065716.50
      2386125.46      7065411.47      2385829.98      7065149.72
      2385831.24      7064965.93      2385977.43      7064716.04
      2385692.20      7064573.74      2385573.17      7064157.70
      2385379.53      7063994.11      2385380.61      7063765.88
      2385480.00      7063665.43      2385378.96      7063125.34
      2385479.47      7062980.16      2385328.33      7062689.92
      2385427.42      7062516.05      2385132.51      7062251.52
      2385062.73      7061892.69      2384837.99      7061867.11
      2384928.20      7061699.30      2384928.51      7061425.22
      2384830.20      7061249.50      2384826.77      7060965.90
      2384673.59      7060657.28      2384539.49      7060610.94
      2384428.99      7060703.02      2384329.00      7060610.00

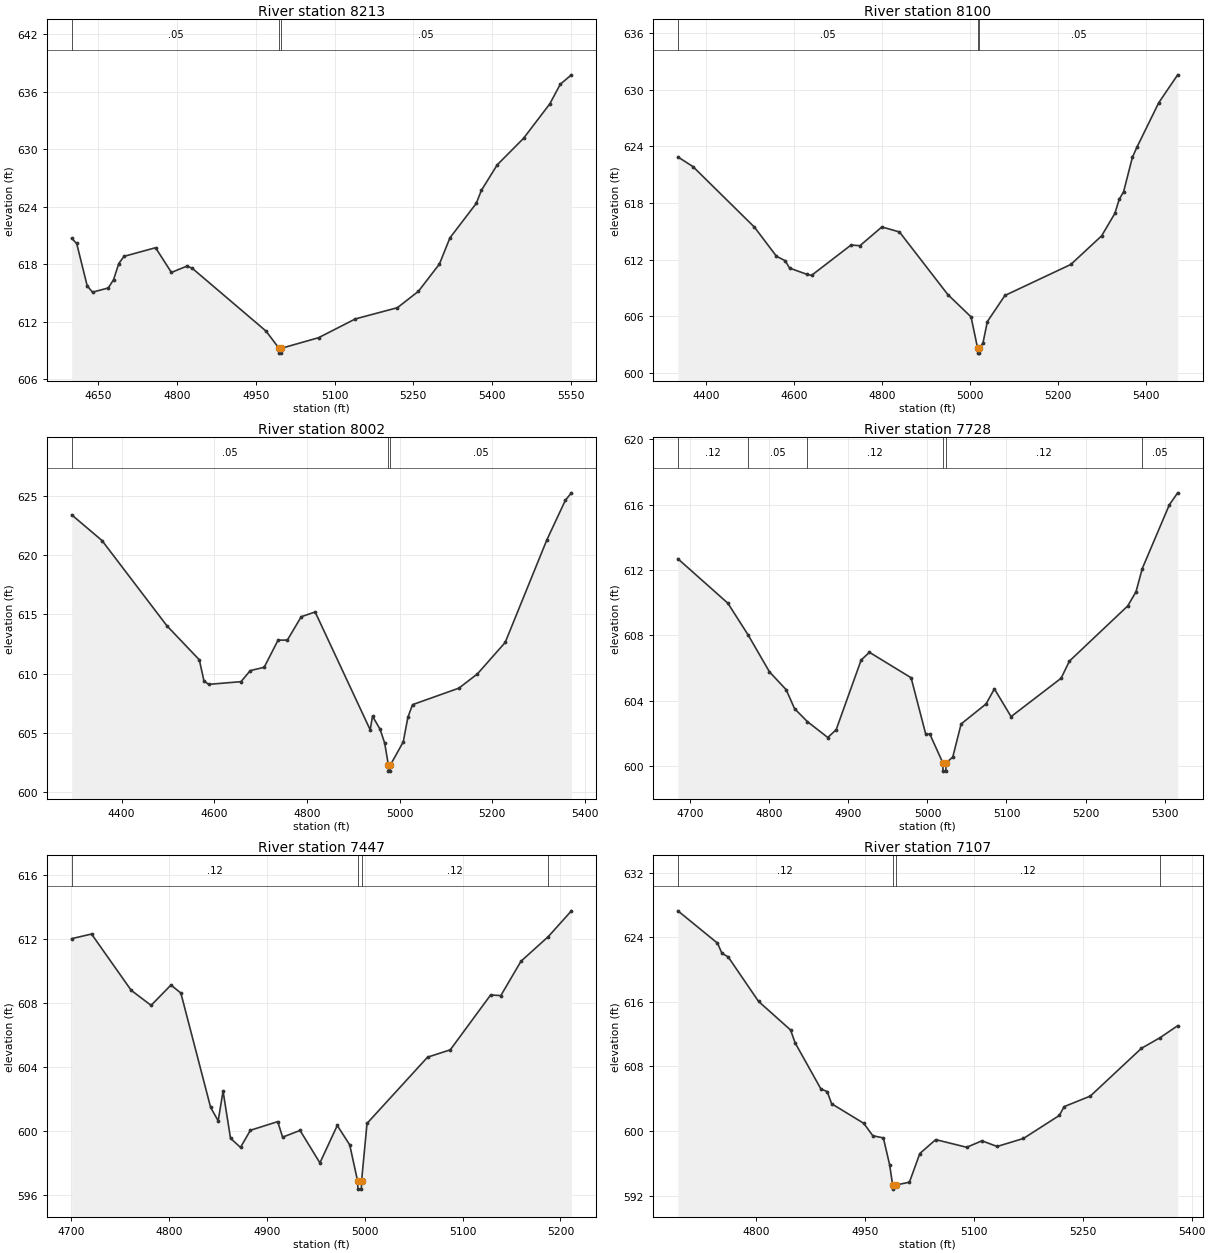
Type RM Length L Ch R = 1,8213,113,113,113
BEGIN DESCRIPTION:
LWE S SB_1 22.0
END DESCRIPTION:
XS GIS Cut Line= 3
      2386728.63      7066810.23      2386330.35      7066795.63
      2385777.83      7066801.88
#Sta/Elev= 30
  4599.7  620.70  4609.3  620.16  4629.3  615.74  4639.4  615.08  4669.4  615.52
  4679.4  616.38  4689.4  618.07  4699.4  618.82  4759.4  619.72  4789.5  617.14
  4819.5  617.81  4829.5  617.56  4969.6  611.02  4994.4  609.22  4994.7  608.72
  4998.2  608.72  4998.4  609.22  5069.6  610.33  5139.6  612.29  5219.6  613.46
  5259.6  615.17  5299.6  618.02  5319.6  620.75  5369.6  624.34  5379.6  625.72
  5409.6  628.37  5459.6  631.13  5509.6  634.73  5529.6  636.78  5550.8  637.76
#Mann=3,-1,0
  4599.7    0.05       0  4994.4   0.033       0  4998.4    0.05       0
Bank Sta=4994.4,4998.4
Exp/Cntr=0.3,0.1

Type RM Length L Ch R = 1,8100,98,98,98
BEGIN DESCRIPTION:
Mapping XS fbb8f2a8
END DESCRIPTION:
XS GIS Cut Line= 3
      2387043.23      7066698.14      2386378.23      7066699.31
      2385906.05      7066710.07
#Sta/Elev= 30
  4335.0  622.88  4369.2  621.86  4509.2  615.44  4559.2  612.36  4579.2  611.88
  4589.2  611.10  4629.2  610.43  4639.2  610.33  4729.2  613.55  4749.2  613.47
  4799.2  615.46  4839.2  614.93  4949.2  608.30  5002.1  605.93  5017.2  602.59
  5017.5  602.09  5021.0  602.09  5021.2  602.59  5029.2  603.15  5039.2  605.43
  5079.2  608.20  5229.3  611.49  5299.3  614.52  5329.3  616.89  5339.3  618.38
  5349.3  619.20  5369.3  622.84  5379.3  623.88  5429.3  628.63  5472.3  631.58
#Mann=3,-1,0
  4335.0    0.05       0  5017.2   0.033       0  5021.2    0.05       0
Bank Sta=5017.2,5021.2
Exp/Cntr=0.3,0.1

Type RM Length L Ch R = 1,8002,274,274,274
BEGIN DESCRIPTION:
LWE S SB_1 21.0
END DESCRIPTION:
XS GIS Cut Line= 3
      2387044.47      7066604.81      2386336.86      7066615.94
      2385965.98      7066620.00
#Sta/Elev= 30
  4292.3  623.38  4357.8  621.21  4497.8  614.03  4567.8  611.16  4577.8  609.39
  4587.8  609.09  4657.8  609.32  4677.8  610.25  4707.8  610.53  4737.8  612.82
  4757.8  612.82  4787.8  614.79  4817.8  615.19  4936.6  605.26  4941.6  606.41
  4957.9  605.31  4967.9  604.14  4975.9  602.28  4976.1  601.78  4979.6  601.78
  4979.9  602.28  5007.9  604.24  5017.9  606.31  5027.9  607.38  5127.9  608.77
  5167.9  609.97  5227.9  612.62  5317.9  621.27  5357.9  624.61  5370.9  625.23
#Mann=3,-1,0
  4292.3    0.05       0  4975.9   0.033       0  4979.9    0.05       0
Bank Sta=4975.9,4979.9
Exp/Cntr=0.3,0.1

Type RM Length L Ch R = 1,7728,281,281,281
BEGIN DESCRIPTION:
LWE S SB_1 20.0
END DESCRIPTION:
XS GIS Cut Line= 3
      2386678.99      7066260.00      2386379.00      7066360.00
      2386079.04      7066459.99
#Sta/Elev= 30
  4684.2  612.69  4747.4  609.97  4773.0  608.03  4800.1  605.76  4821.2  604.67
  4831.8  603.51  4847.9  602.72  4873.9  601.74  4884.5  602.22  4916.1  606.49
  4926.6  606.96  4979.3  605.40  4997.8  601.95  5003.0  601.95  5019.5  600.18
  5019.7  599.68  5023.2  599.68  5023.5  600.18  5032.0  600.54  5042.6  602.57
  5074.2  603.80  5084.7  604.72  5105.8  603.02  5169.1  605.37  5179.6  606.42
  5253.4  609.80  5263.9  610.67  5271.8  612.09  5306.1  616.00  5316.6  616.73
#Mann=6,-1,0
  4684.2    0.12       0  4773.0    0.05       0  4847.9    0.12       0
  5019.5    0.07       0  5023.5    0.12       0  5271.8    0.05       0
Bank Sta=5019.5,5023.5
Exp/Cntr=0.3,0.1

Type RM Length L Ch R = 1,7447,340,340,340
BEGIN DESCRIPTION:
LWE S SB_1 19.0
END DESCRIPTION:
XS GIS Cut Line= 3
      2386579.02      7066160.00      2386279.00      7066110.00
      2386079.01      7066160.00
#Sta/Elev= 30
  4700.9  612.02  4721.2  612.31  4761.7  608.79  4782.0  607.85  4802.3  609.12
  4812.4  608.62  4842.8  601.47  4850.5  600.63  4855.5  602.49  4863.1  599.54
  4873.3  598.97  4883.4  600.04  4911.3  600.58  4916.3  599.61  4934.1  600.03
  4954.4  598.00  4972.1  600.34  4984.8  599.13  4992.9  596.86  4993.2  596.36
  4996.7  596.36  4996.9  596.86  5002.5  600.47  5064.3  604.61  5087.5  605.07
  5128.7  608.50  5139.1  608.46  5159.7  610.61  5187.6  612.15  5211.2  613.76
#Mann=4,-1,0
  4700.9    0.12       0  4992.9    0.07       0  4996.9    0.12       0
  5187.6    0.05       0
Bank Sta=4992.9,4996.9
Exp/Cntr=0.3,0.1

Type RM Length L Ch R = 1,7107,443,443,443
BEGIN DESCRIPTION:
LWE S SB_1 18.0
END DESCRIPTION:
XS GIS Cut Line= 3
      2386526.89      7065592.25      2386277.52      7065771.49
      2386028.99      7066060.01
#Sta/Elev= 30
  4692.9  627.26  4747.4  623.26  4753.5  622.01  4762.1  621.56  4803.9  616.05
  4848.0  612.51  4854.2  610.93  4889.8  605.20  4898.4  604.89  4904.5  603.38
  4948.7  600.96  4961.2  599.42  4975.7  599.15  4984.3  595.85  4988.5  593.31
  4988.7  592.81  4992.5  593.31  5011.6  593.67  5025.9  597.22  5047.8  598.94
  5090.4  597.99  5111.4  598.79  5132.3  598.09  5168.5  599.08  5217.9  601.93
  5224.5  603.02  5260.6  604.33  5330.9  610.24  5356.8  611.57  5380.8  613.04
#Mann=4,-1,0
  4692.9    0.12       0  4988.5    0.07       0  4992.5    0.12       0
  5356.8    0.05       0
Bank Sta=4988.5,4992.5
Exp/Cntr=0.3,0.1

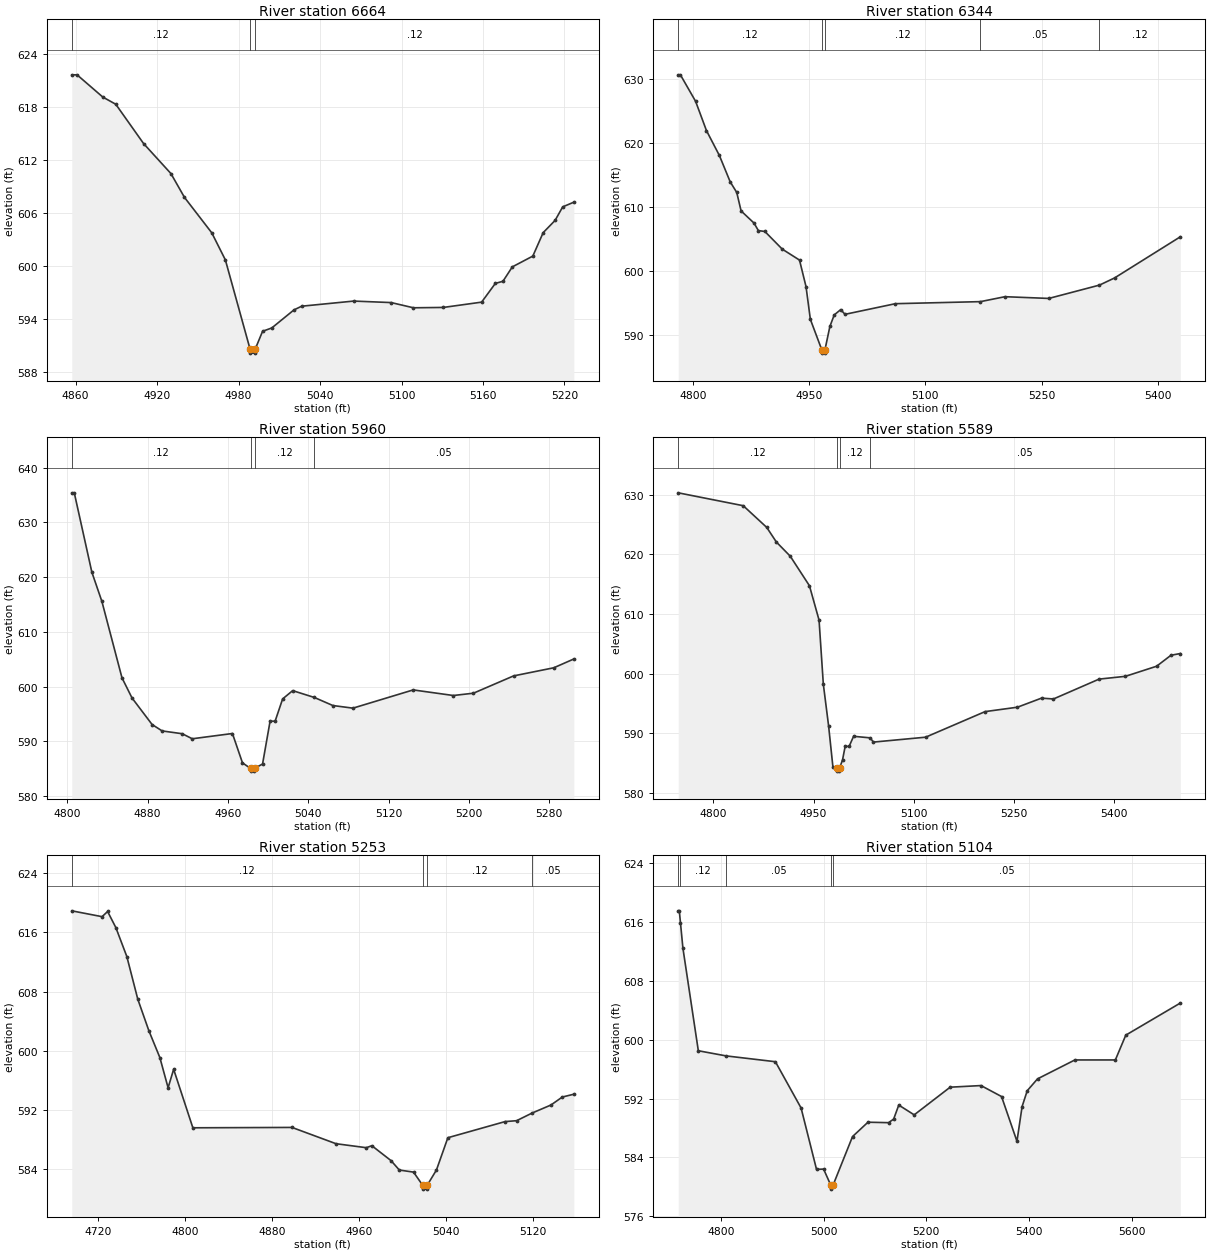
Type RM Length L Ch R = 1,6664,320,320,320
BEGIN DESCRIPTION:
LWE S SB_1 17.0
END DESCRIPTION:
XS GIS Cut Line= 3
      2386271.76      7065491.96      2386129.44      7065503.68
      2385928.99      7065610.00
#Sta/Elev= 30
  4857.2  621.59  4861.1  621.59  4880.0  619.08  4889.6  618.26  4910.1  613.81
  4930.2  610.42  4940.2  607.72  4960.3  603.71  4970.3  600.65  4988.4  590.60
  4988.7  590.10  4992.2  590.10  4992.4  590.60  4997.7  592.57  5004.5  592.95
  5020.8  594.99  5026.5  595.41  5064.8  595.99  5092.4  595.82  5108.8  595.23
  5130.8  595.27  5159.0  595.87  5169.1  597.99  5174.7  598.23  5181.6  599.86
  5196.7  601.08  5204.3  603.73  5213.1  605.12  5218.7  606.65  5226.9  607.18
#Mann=3,-1,0
  4857.2    0.12       0  4988.4    0.07       0  4992.4    0.12       0
Bank Sta=4988.4,4992.4
Exp/Cntr=0.3,0.1

Type RM Length L Ch R = 1,6344,384,384,384
BEGIN DESCRIPTION:
LWE S SB_1 16.0
END DESCRIPTION:
XS GIS Cut Line= 3
      2386079.01      7065059.98      2385979.00      7065260.00
      2385678.99      7065560.01
#Sta/Elev= 30
  4781.2  630.60  4784.0  630.60  4803.6  626.47  4817.6  621.91  4834.3  618.02
  4848.3  613.90  4856.7  612.26  4862.3  609.38  4879.0  607.48  4884.6  606.31
  4893.0  606.17  4915.4  603.42  4937.7  601.71  4946.1  597.57  4951.7  592.47
  4966.5  587.70  4966.7  587.20  4970.2  587.20  4970.5  587.70  4976.9  591.36
  4982.5  593.16  4990.9  593.99  4996.4  593.25  5061.4  594.91  5171.2  595.23
  5202.8  596.00  5259.4  595.73  5324.8  597.81  5344.2  598.92  5429.1  605.34
#Mann=5,-1,0
  4781.2    0.12       0  4966.5    0.07       0  4970.5    0.12       0
  5171.2    0.05       0  5324.8    0.12       0
Bank Sta=4966.5,4970.5
Exp/Cntr=0.3,0.1

Type RM Length L Ch R = 1,5960,371,371,371
BEGIN DESCRIPTION:
LWE S SB_1 15.0
END DESCRIPTION:
XS GIS Cut Line= 3
      2386029.03      7064960.00      2385829.00      7064960.00
      2385529.03      7064960.00
#Sta/Elev= 30
  4804.5  635.39  4807.0  635.39  4824.5  620.90  4834.5  615.56  4854.5  601.61
  4864.5  597.93  4884.5  593.08  4894.5  591.91  4914.5  591.40  4924.5  590.48
  4964.5  591.44  4974.5  586.08  4982.5  585.07  4982.8  584.57  4986.3  584.57
  4986.5  585.07  4994.5  585.87  5002.0  593.69  5007.0  593.69  5014.5  597.76
  5024.5  599.27  5046.1  598.02  5064.5  596.55  5084.5  596.07  5144.5  599.40
  5184.5  598.38  5204.5  598.80  5244.5  601.96  5284.5  603.44  5304.5  605.05
#Mann=4,-1,0
  4804.5    0.12       0  4982.5    0.07       0  4986.5    0.12       0
  5046.1    0.05       0
Bank Sta=4982.5,4986.5
Exp/Cntr=0.3,0.1

Type RM Length L Ch R = 1,5589,336,336,336
BEGIN DESCRIPTION:
LWE S SB_1 14.0
END DESCRIPTION:
XS GIS Cut Line= 3
      2386124.89      7064499.72      2385929.00      7064660.00
      2385466.02      7064844.78
#Sta/Elev= 30
  4747.4  630.31  4844.7  628.15  4879.9  624.51  4894.3  622.06  4915.1  619.68
  4943.8  614.73  4958.2  608.97  4964.6  598.22  4972.5  591.22  4979.0  584.29
  4984.9  584.14  4985.1  583.64  4988.6  583.64  4988.9  584.14  4993.3  585.50
  4997.3  587.79  5003.2  587.79  5009.9  589.48  5034.6  589.22  5039.6  588.51
  5117.7  589.33  5206.7  593.62  5255.2  594.36  5291.2  595.88  5309.1  595.74
  5377.4  599.07  5416.9  599.54  5463.5  601.23  5485.0  603.07  5499.0  603.36
#Mann=4,-1,0
  4747.4    0.12       0  4984.9    0.07       0  4988.9    0.12       0
  5034.6    0.05       0
Bank Sta=4984.9,4988.9
Exp/Cntr=0.3,0.1

Type RM Length L Ch R = 1,5253,149,149,149
BEGIN DESCRIPTION:
LWE S SB_1 13.0
END DESCRIPTION:
XS GIS Cut Line= 3
      2385979.01      7064460.00      2385679.00      7064510.00
      2385528.96      7064560.01
#Sta/Elev= 30
  4695.4  618.92  4723.3  618.13  4728.4  618.83  4736.0  616.65  4746.1  612.74
  4756.2  606.97  4766.4  602.71  4776.5  599.09  4784.1  595.00  4789.2  597.50
  4806.9  589.59  4898.2  589.64  4938.7  587.44  4966.6  586.90  4971.7  587.17
  4989.4  585.15  4997.0  583.88  5010.1  583.60  5018.6  581.80  5018.9  581.30
  5022.4  581.30  5022.6  581.80  5031.2  583.89  5041.7  588.25  5094.4  590.43
  5105.0  590.55  5119.2  591.58  5136.6  592.67  5147.1  593.75  5157.7  594.13
#Mann=4,-1,0
  4695.4    0.12       0  5018.6    0.07       0  5022.6    0.12       0
  5119.2    0.05       0
Bank Sta=5018.6,5022.6
Exp/Cntr=0.3,0.1

Type RM Length L Ch R = 1,5104,111,111,111
BEGIN DESCRIPTION:
Mapping XS 38b16fa8
END DESCRIPTION:
XS GIS Cut Line= 4
      2385958.14      7064359.46      2385675.25      7064361.55
      2385227.59      7064358.77      2384984.29      7064398.59
#Sta/Elev= 30
  4717.1  617.51  4719.2  617.51  4721.5  615.84  4726.2  612.44  4756.2  598.50
  4810.3  597.80  4906.2  597.01  4956.2  590.72  4986.2  582.39  5000.0  582.42
  5014.2  580.20  5014.5  579.70  5018.2  580.20  5056.3  586.84  5086.3  588.79
  5126.3  588.73  5136.3  589.21  5146.3  591.12  5176.3  589.79  5246.3  593.55
  5306.3  593.77  5346.3  592.28  5376.3  586.20  5386.3  590.92  5396.3  593.07
  5416.3  594.68  5489.0  597.25  5567.8  597.25  5588.1  600.62  5694.2  604.98
#Mann=5,-1,0
  4717.1    0.05       0  4721.5    0.12       0  4810.3    0.05       0
  5014.2   0.033       0  5018.2    0.05       0
Bank Sta=5014.2,5018.2
Exp/Cntr=0.3,0.1

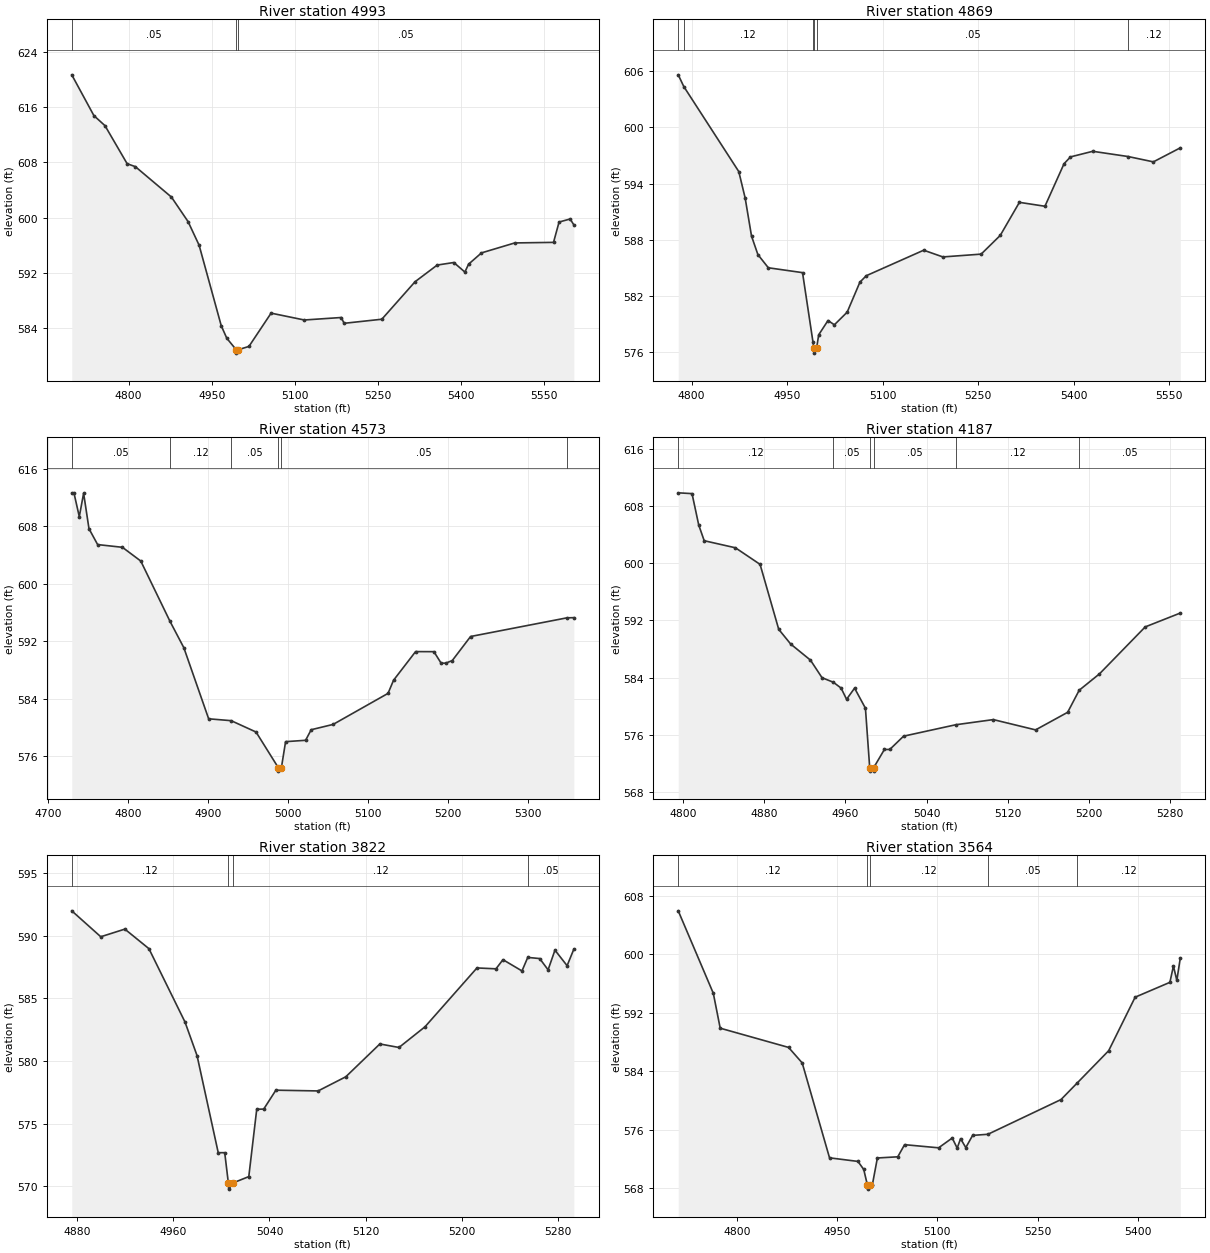
Type RM Length L Ch R = 1,4993,124,124,124
BEGIN DESCRIPTION:
Mapping XS d19336cd
END DESCRIPTION:
XS GIS Cut Line= 4
      2385929.02      7064264.33      2385626.32      7064266.11
      2385210.75      7064263.63      2385022.32      7064258.01
#Sta/Elev= 30
  4697.3  620.64  4737.3  614.74  4757.3  613.29  4797.3  607.79  4812.1  607.37
  4877.3  602.97  4907.3  599.43  4927.3  596.01  4967.3  584.36  4977.3  582.56
  4994.2  580.91  4994.4  580.41  4998.2  580.91  5017.3  581.38  5057.3  586.19
  5117.3  585.20  5184.1  585.56  5189.1  584.72  5257.3  585.31  5317.3  590.73
  5357.3  593.14  5387.3  593.51  5407.3  592.13  5414.0  593.27  5437.3  594.90
  5497.4  596.34  5567.4  596.42  5577.4  599.36  5597.4  599.80  5604.1  598.95
#Mann=3,-1,0
  4697.3    0.05       0  4994.2   0.033       0  4998.2    0.05       0
Bank Sta=4994.2,4998.2
Exp/Cntr=0.3,0.1

Type RM Length L Ch R = 1,4869,296,296,296
BEGIN DESCRIPTION:
LWE S SB_1 12.0
END DESCRIPTION:
XS GIS Cut Line= 3
      2385794.04      7064150.06      2385573.17      7064157.70
      2385006.81      7064193.73
#Sta/Elev= 30
  4779.0  605.63  4787.7  604.38  4874.1  595.28  4884.1  592.45  4894.1  588.38
  4904.1  586.40  4920.5  584.99  4974.2  584.47  4990.6  577.05  4992.2  576.36
  4992.4  575.86  4996.2  576.36  4999.6  577.82  5014.2  579.35  5024.2  578.89
  5044.3  580.24  5064.3  583.45  5074.3  584.14  5164.5  586.87  5194.6  586.15
  5254.7  586.45  5284.7  588.45  5314.8  591.99  5354.9  591.57  5384.9  596.12
  5395.0  596.85  5430.0  597.45  5485.5  596.89  5525.2  596.32  5567.5  597.82
#Mann=6,-1,0
  4779.0    0.05       0  4787.7    0.12       0  4990.6    0.05       0
  4992.2   0.033       0  4996.2    0.05       0  5485.5    0.12       0
Bank Sta=4992.2,4996.2
Exp/Cntr=0.3,0.1

Type RM Length L Ch R = 1,4573,386,386,386
BEGIN DESCRIPTION:
LWE S SB_1 11.0
END DESCRIPTION:
XS GIS Cut Line= 3
      2385629.01      7063860.00      2385378.03      7063960.36
      2385066.28      7064134.11
#Sta/Elev= 30
  4729.7  612.62  4732.4  612.62  4739.1  609.30  4744.5  612.56  4751.2  607.63
  4762.0  605.42  4793.0  605.04  4815.9  603.13  4852.5  594.72  4869.7  591.07
  4900.7  581.18  4928.8  580.92  4959.9  579.34  4987.6  574.40  4987.8  573.90
  4991.6  574.40  4996.8  578.00  5021.8  578.19  5028.8  579.66  5056.2  580.40
  5124.8  584.72  5131.7  586.55  5159.2  590.53  5182.1  590.52  5191.1  588.92
  5196.8  588.92  5205.0  589.28  5227.9  592.63  5348.4  595.23  5356.9  595.25
#Mann=6,-1,0
  4729.7    0.05       0  4852.5    0.12       0  4928.8    0.05       0
  4987.6   0.033       0  4991.6    0.05       0  5348.4    0.12       0
Bank Sta=4987.6,4991.6
Exp/Cntr=0.3,0.1

Type RM Length L Ch R = 1,4187,365,365,365
BEGIN DESCRIPTION:
LWE S SB_1 10.0
END DESCRIPTION:
XS GIS Cut Line= 3
      2385671.74      7063732.57      2385479.00      7063660.00
      2385202.91      7063574.10
#Sta/Elev= 30
  4795.1  609.86  4808.7  609.75  4815.3  605.36  4820.7  603.16  4851.5  602.17
  4875.8  599.85  4894.2  590.76  4906.0  588.70  4925.5  586.45  4936.9  583.99
  4948.0  583.36  4955.7  582.54  4961.1  580.97  4969.0  582.53  4979.7  579.72
  4983.9  571.42  4984.2  570.92  4987.7  570.92  4987.9  571.42  4998.4  573.95
  5003.7  573.95  5017.3  575.81  5068.8  577.41  5105.8  578.13  5147.5  576.69
  5179.1  579.15  5190.5  582.24  5210.5  584.53  5255.6  591.10  5290.2  593.04
#Mann=6,-1,0
  4795.1    0.12       0  4948.0    0.05       0  4983.9   0.033       0
  4987.9    0.05       0  5068.8    0.12       0  5190.5    0.05       0
Bank Sta=4983.9,4987.9
Exp/Cntr=0.3,0.1

Type RM Length L Ch R = 1,3822,258,258,258
BEGIN DESCRIPTION:
LWE S SB_1 9.0
END DESCRIPTION:
XS GIS Cut Line= 3
      2385553.13      7063340.60      2385428.84      7063340.01
      2385174.37      7063485.05
#Sta/Elev= 30
  4875.7  591.99  4899.8  589.92  4919.8  590.53  4939.8  588.97  4969.8  583.11
  4979.8  580.43  4997.4  572.68  5002.8  572.68  5005.8  570.27  5006.1  569.77
  5009.8  570.27  5022.8  570.77  5029.4  576.15  5035.2  576.16  5045.3  577.67
  5080.4  577.61  5103.4  578.74  5131.7  581.36  5147.6  581.08  5169.2  582.73
  5212.4  587.43  5228.2  587.36  5234.0  588.09  5249.8  587.19  5254.6  588.27
  5264.5  588.18  5271.5  587.28  5277.2  588.85  5287.3  587.61  5292.9  588.93
#Mann=4,-1,0
  4875.7    0.12       0  5005.8    0.07       0  5009.8    0.12       0
  5254.6    0.05       0
Bank Sta=5005.8,5009.8
Exp/Cntr=0.3,0.1

Type RM Length L Ch R = 1,3564,362,362,362
BEGIN DESCRIPTION:
LWE S SB_1 8.0
END DESCRIPTION:
XS GIS Cut Line= 3
      2385670.36      7063160.93      2385389.21      7063100.32
      2384933.67      7063186.89
#Sta/Elev= 30
  4712.4  605.91  4764.9  594.63  4775.2  589.86  4877.5  587.23  4897.9  585.11
  4938.8  572.13  4981.3  571.64  4990.0  570.54  4995.6  568.35  4995.8  567.85
  4999.6  568.35  5002.7  568.35  5010.4  572.11  5040.9  572.27  5051.1  573.93
  5102.0  573.50  5122.4  574.84  5129.8  573.46  5134.9  574.75  5142.7  573.53
  5152.9  575.20  5175.8  575.35  5285.2  580.10  5308.7  582.30  5356.5  586.78
  5396.1  594.10  5448.1  596.13  5453.4  598.36  5458.5  596.40  5463.7  599.47
#Mann=5,-1,0
  4712.4    0.12       0  4995.6    0.07       0  4999.6    0.12       0
  5175.8    0.05       0  5308.7    0.12       0
Bank Sta=4995.6,4999.6
Exp/Cntr=0.3,0.1

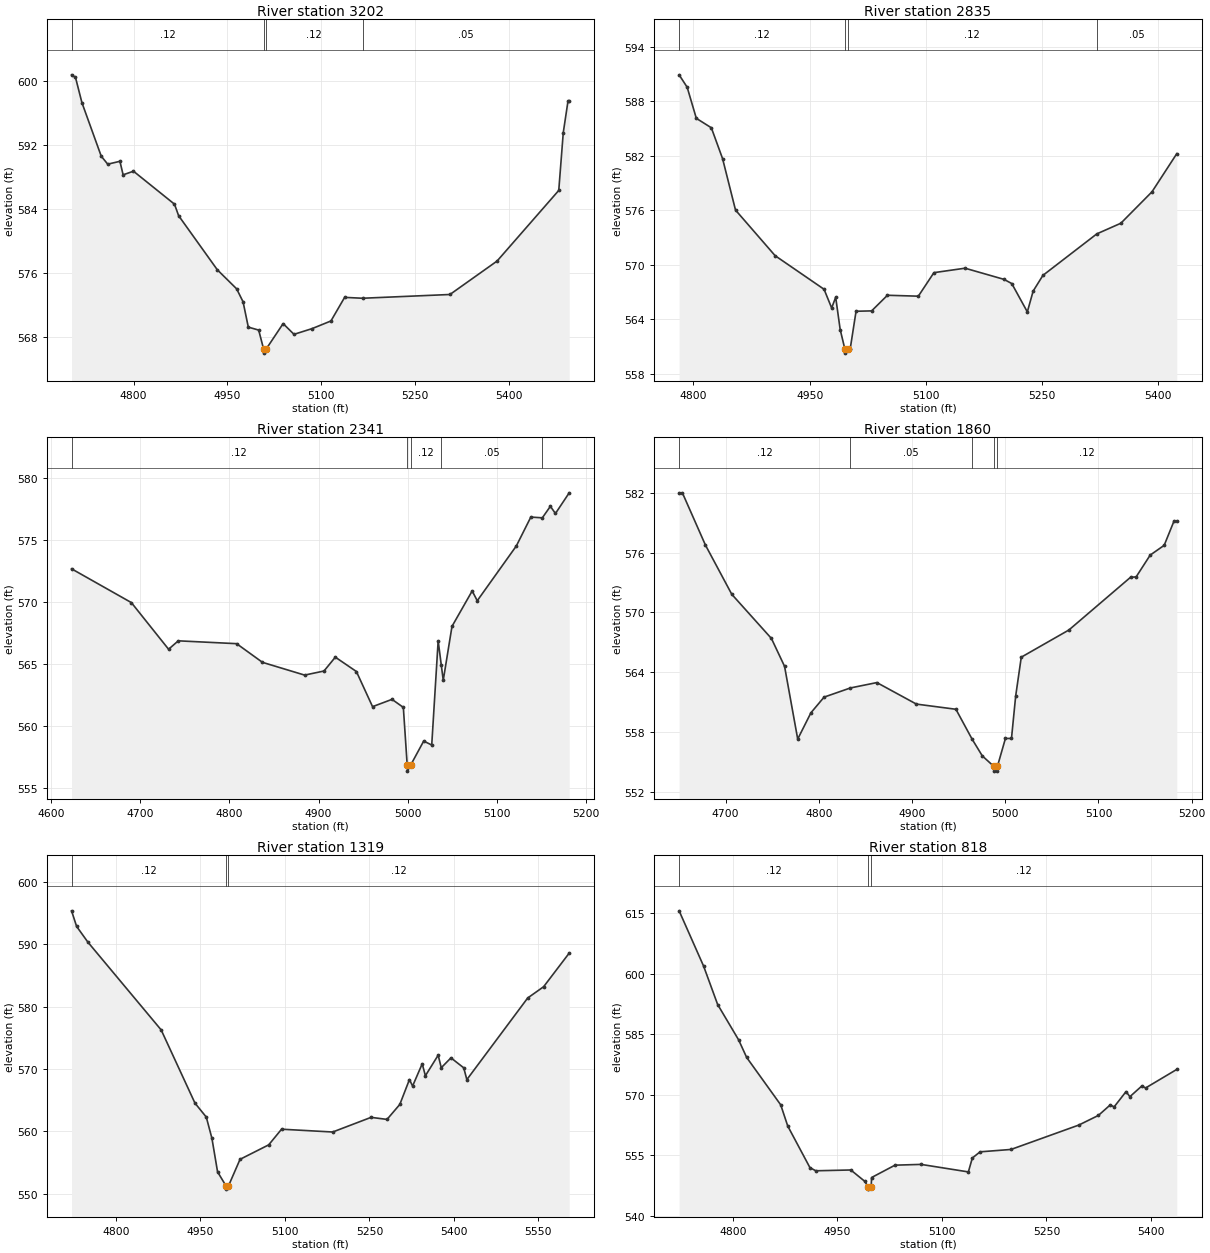
Type RM Length L Ch R = 1,3202,367,367,367
BEGIN DESCRIPTION:
LWE S SB_1 7.0
END DESCRIPTION:
XS GIS Cut Line= 3
      2385665.11      7062884.88      2385374.78      7062811.75
      2384920.33      7063012.47
#Sta/Elev= 30
  4700.6  600.73  4706.9  600.41  4717.2  597.25  4748.1  590.56  4758.5  589.56
  4778.0  589.92  4783.1  588.23  4799.7  588.68  4865.3  584.56  4871.9  583.12
  4933.8  576.36  4964.7  573.98  4975.0  572.36  4983.4  569.19  5000.0  568.82
  5007.9  566.44  5008.2  565.94  5011.9  566.44  5039.1  569.63  5056.5  568.29
  5085.3  569.00  5115.6  569.96  5137.5  572.91  5166.1  572.80  5306.0  573.27
  5381.4  577.45  5480.1  586.28  5487.3  593.50  5494.8  597.41  5496.8  597.41
#Mann=4,-1,0
  4700.6    0.12       0  5007.9    0.07       0  5011.9    0.12       0
  5166.1    0.05       0
Bank Sta=5007.9,5011.9
Exp/Cntr=0.3,0.1

Type RM Length L Ch R = 1,2835,494,494,494
BEGIN DESCRIPTION:
LWE S SB_1 6.0
END DESCRIPTION:
XS GIS Cut Line= 3
      2385629.02      7062560.01      2385418.83      7062500.32
      2384997.16      7062543.73
#Sta/Elev= 30
  4781.5  590.91  4791.9  589.54  4803.7  586.12  4823.1  585.08  4837.6  581.68
  4854.3  576.02  4905.4  571.00  4968.6  567.30  4978.4  565.24  4983.6  566.42
  4989.4  562.87  4995.3  560.77  4995.6  560.27  4999.3  560.77  5002.4  560.77
  5009.9  564.88  5030.0  564.92  5050.4  566.64  5090.3  566.54  5110.4  569.13
  5150.6  569.62  5200.9  568.39  5210.9  567.93  5231.0  564.81  5238.5  567.10
  5251.1  568.83  5320.7  573.40  5351.7  574.57  5391.9  578.03  5423.9  582.23
#Mann=4,-1,0
  4781.5    0.12       0  4995.3    0.07       0  4999.3    0.12       0
  5320.7    0.05       0
Bank Sta=4995.3,4999.3
Exp/Cntr=0.3,0.1

Type RM Length L Ch R = 1,2341,481,481,481
BEGIN DESCRIPTION:
LWE S SB_1 5.0
END DESCRIPTION:
XS GIS Cut Line= 3
      2385428.96      7062010.02      2385079.00      7062160.00
      2384923.45      7062243.96
#Sta/Elev= 30
  4623.3  572.68  4690.3  569.95  4732.0  566.18  4742.9  566.86  4808.2  566.63
  4837.2  565.12  4884.4  564.09  4906.1  564.42  4918.8  565.54  4942.4  564.38
  4960.5  561.54  4982.3  562.13  4995.0  561.48  4999.3  556.83  4999.6  556.33
  5003.3  556.83  5017.8  558.76  5026.8  558.44  5034.0  566.86  5037.5  564.90
  5039.7  563.67  5049.5  568.03  5072.1  570.89  5077.8  570.10  5121.6  574.53
  5137.8  576.86  5150.7  576.80  5159.7  577.73  5165.4  577.15  5180.8  578.82
#Mann=5,-1,0
  4623.3    0.12       0  4999.3    0.07       0  5003.3    0.12       0
  5037.5    0.05       0  5150.7    0.12       0
Bank Sta=4999.3,5003.3
Exp/Cntr=0.3,0.1

Type RM Length L Ch R = 1,1860,541,541,541
BEGIN DESCRIPTION:
LWE S SB_1 4.0
END DESCRIPTION:
XS GIS Cut Line= 3
      2385128.98      7061660.02      2384879.00      7061910.00
      2384779.00      7062060.00
#Sta/Elev= 30
  4650.2  582.00  4653.7  582.00  4678.4  576.76  4706.7  571.81  4749.2  567.38
  4763.3  564.58  4777.4  557.28  4791.6  559.92  4805.7  561.49  4833.9  562.41
  4862.3  562.95  4904.7  560.79  4947.1  560.27  4964.4  557.28  4975.4  555.59
  4987.5  554.56  4987.8  554.06  4991.4  554.06  4991.7  554.56  5000.2  557.34
  5006.7  557.34  5011.2  561.60  5017.2  565.50  5068.3  568.23  5134.4  573.52
  5140.4  573.56  5155.5  575.75  5170.5  576.73  5181.0  579.16  5184.0  579.16
#Mann=5,-1,0
  4650.2    0.12       0  4833.9    0.05       0  4964.4    0.12       0
  4987.5    0.07       0  4991.7    0.12       0
Bank Sta=4987.5,4991.7
Exp/Cntr=0.3,0.1

Type RM Length L Ch R = 1,1319,501,501,501
BEGIN DESCRIPTION:
LWE S SB_1 3.0
END DESCRIPTION:
XS GIS Cut Line= 3
      2385208.03      7061453.88      2384929.47      7061444.84
      2384383.48      7061704.74
#Sta/Elev= 30
  4721.3  595.37  4730.3  592.87  4750.3  590.35  4880.4  576.27  4940.4  564.53
  4960.5  562.29  4970.5  558.88  4980.5  553.51  4995.6  551.24  4995.9  550.74
  4999.8  551.24  5020.4  555.52  5071.3  557.84  5094.1  560.35  5184.9  559.90
  5253.0  562.25  5281.3  561.92  5304.0  564.32  5321.1  568.31  5326.7  567.27
  5343.8  570.84  5349.4  568.92  5372.1  572.22  5377.6  570.21  5394.8  571.79
  5417.5  570.19  5423.0  568.30  5531.0  581.39  5559.3  583.20  5604.7  588.59
#Mann=3,-1,0
  4721.3    0.12       0  4995.6    0.07       0  4999.8    0.12       0
Bank Sta=4995.6,4999.8
Exp/Cntr=0.3,0.1

Type RM Length L Ch R = 1,818,505,505,505
BEGIN DESCRIPTION:
LWE S SB_1 2.0
END DESCRIPTION:
XS GIS Cut Line= 3
      2385103.92      7060944.77      2384828.50      7060975.20
      2384434.67      7061164.81
#Sta/Elev= 30
  4722.9  615.55  4758.0  601.88  4778.2  592.36  4808.3  583.61  4819.8  579.27
  4868.7  567.53  4878.8  562.28  4910.6  552.00  4919.0  551.21  4969.3  551.41
  4989.4  548.59  4994.2  547.17  4994.5  546.67  4998.5  547.17  4999.1  549.54
  5032.7  552.60  5070.1  552.79  5138.0  550.93  5143.7  554.37  5154.8  555.90
  5199.2  556.49  5296.4  562.52  5324.6  564.91  5341.6  567.51  5347.2  567.03
  5364.3  570.81  5369.8  569.55  5386.9  572.19  5392.4  571.71  5437.1  576.30
#Mann=3,-1,0
  4722.9    0.12       0  4994.2    0.07       0  4998.5    0.12       0
Bank Sta=4994.2,4998.5
Exp/Cntr=0.3,0.1

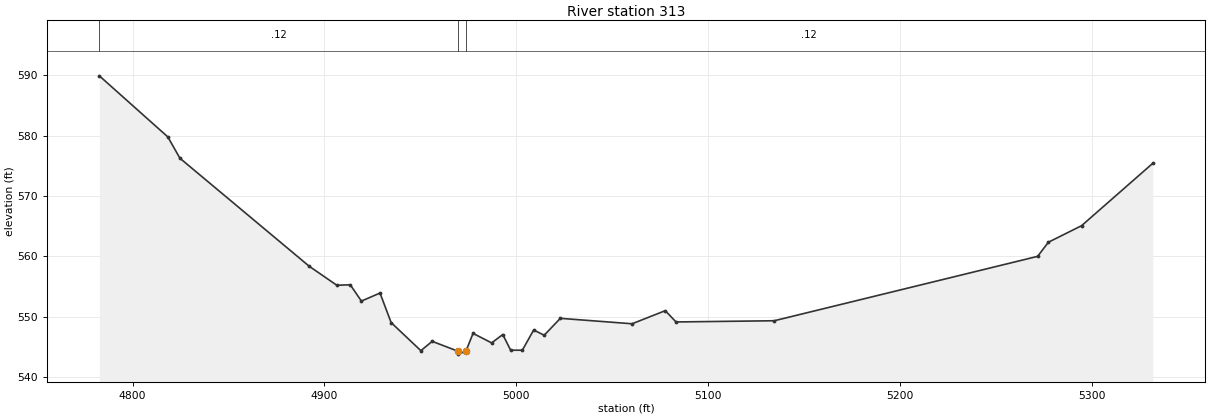
Type RM Length L Ch R = 1,313,0,0,0
BEGIN DESCRIPTION:
LWE S SB_ 1.0
END DESCRIPTION:
XS GIS Cut Line= 3
      2384754.98      7060496.83      2384568.96      7060609.15
      2384429.00      7060909.99
#Sta/Elev= 30
  4782.7  589.91  4818.4  579.79  4824.7  576.26  4892.1  558.36  4906.5  555.21
  4913.5  555.29  4919.3  552.59  4929.0  553.92  4934.8  549.03  4950.3  544.37
  4956.2  545.92  4969.5  544.30  4969.9  543.80  4973.8  544.30  4977.5  547.24
  4987.2  545.66  4993.0  547.05  4997.1  544.45  5003.2  544.45  5009.1  547.80
  5014.6  546.93  5023.0  549.73  5060.4  548.83  5077.7  551.00  5083.3  549.13
  5134.5  549.33  5271.8  560.00  5277.4  562.34  5294.7  565.08  5331.8  575.41
#Mann=3,-1,0
  4782.7    0.12       0  4969.5    0.07       0  4973.8    0.12       0
Bank Sta=4969.5,4973.8
Exp/Cntr=0.3,0.1

Chan Stop Cuts=-1