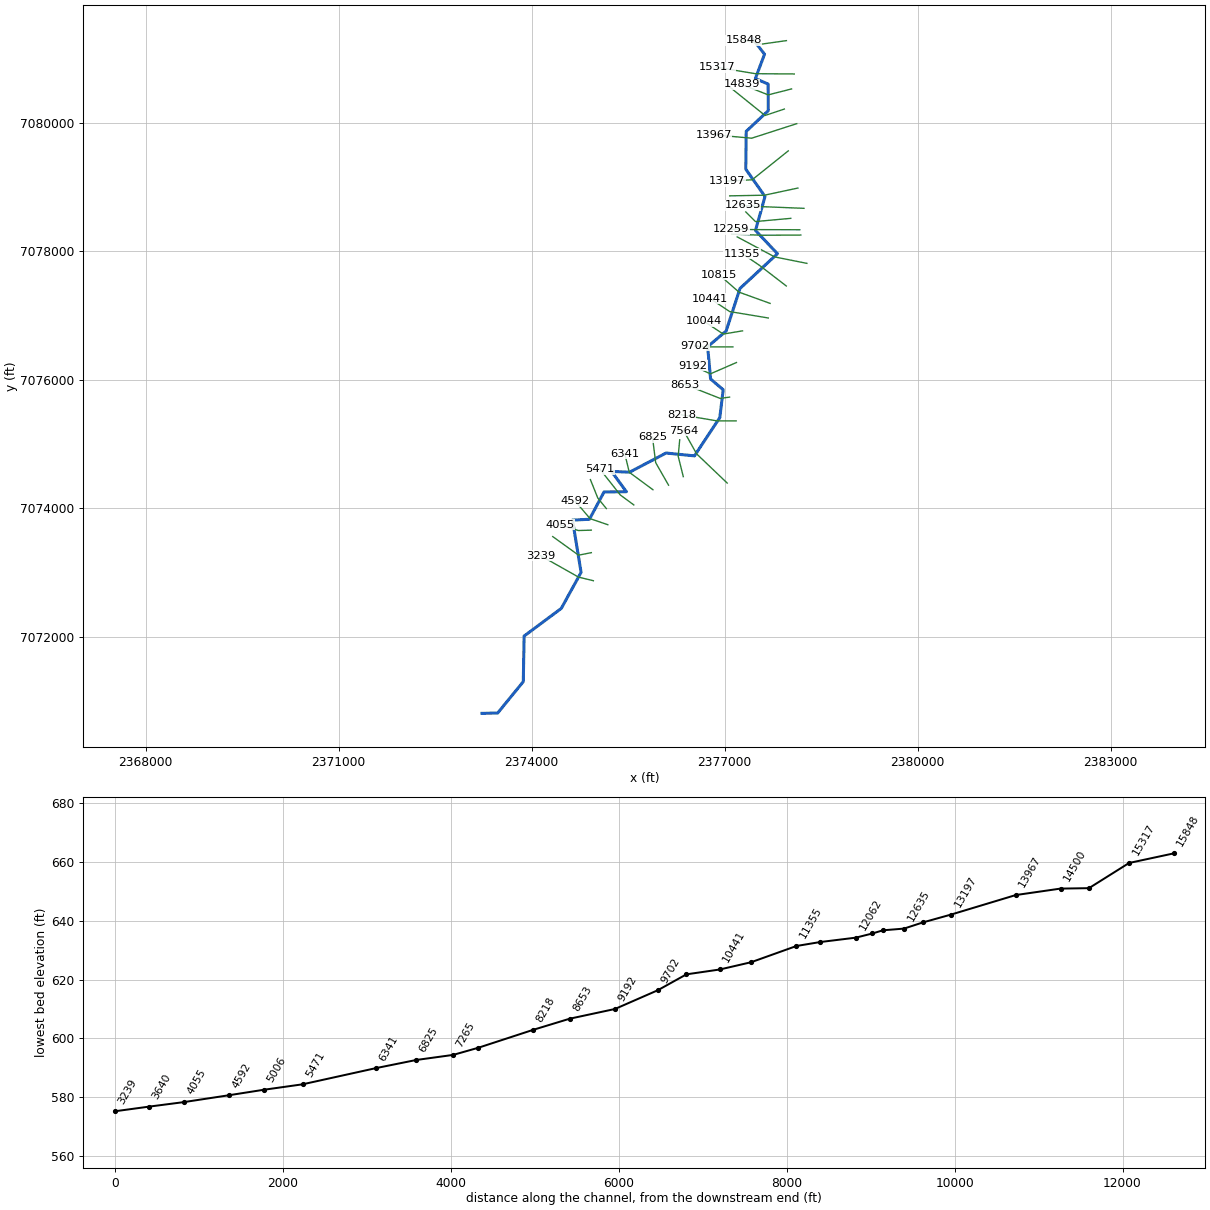
--- LWE S WB_1.prj (project) ---

Proj Title=LWE S WB_1 Base Level Engineering
Current Plan=p01
Default Exp/Contr=0.3,0.1
English Units
Geom File=g01
Flow File=f01
Plan File=p01
Y Axis Title=Elevation
X Axis Title(PF)=Main Channel Distance
X Axis Title(XS)=Station
BEGIN DESCRIPTION:
LWE S WB_1
END DESCRIPTION:
DSS Export Rating Curves= 0
DSS Export Rating Curve Sorted= 0
DSS Export Volume Flow Curves= 0
DXF OffsetX= 0
DXF OffsetY= 0
DXF ScaleX= 1
DXF ScaleY= 10

--- LWE S WB_1.p01 (plan) ---

Plan Title=Multiple Run
Short Identifier=Multiple
Geom File=g01
Flow File=f01
Subcritical Flow
K Sum by GR= 0
Std Step Tol= 0.01
Critical Tol= 0.01
Num of Std Step Trials= 20
Max Error Tol= 0.3
Flow Tol Ratio= 0.001
Split Flow NTrial= 30
Split Flow Tol= 0.02
Split Flow Ratio= 0.02
Log Output Level= 0
Friction Slope Method= 1
Unsteady Friction Slope Method= 2
Unsteady Bridges Friction Slope Method= 1
Parabolic Critical Depth
Global Vel Dist=  1 , 1 , 1
Global Log Level= 0
CheckData=True
Encroach Param= -1, 0, 0, 0
BEGIN DESCRIPTION:
Multiple Run
END DESCRIPTION:

--- LWE S WB_1.f01 (steady flow) ---

Flow Title=Multiple
Number of Profiles=7
Profile Names=10-year,25-year,50-year,1pct_min,100-year,1pct_plu,500-year
River Rch & RM= LWE S WB_1,Reach-1,15848
     248     320     376     221     440     878     602
River Rch & RM= LWE S WB_1,Reach-1,13197
     393     523     627     374     747    1491    1061
River Rch & RM= LWE S WB_1,Reach-1,10815
     519     704     854     515    1028    2051    1492
River Rch & RM= LWE S WB_1,Reach-1,8218
     726    1004    1236     755    1507    3006    2244
River Rch & RM= LWE S WB_1,Reach-1,7564
    1280    1821    2284    1419    2830    5648    4361
River Rch & RM= LWE S WB_1,Reach-1,2785
    1336    1904    2389    1485    2963    5912    4571
Boundary for River Rch & Prof#=LWE S WB_1,Reach-1,1
Up Type=0
Dn Type=3
Dn Slope=0.005
Boundary for River Rch & Prof#=LWE S WB_1,Reach-1,2
Up Type=0
Dn Type=3
Dn Slope=0.005
Boundary for River Rch & Prof#=LWE S WB_1,Reach-1,3
Up Type=0
Dn Type=3
Dn Slope=0.005
Boundary for River Rch & Prof#=LWE S WB_1,Reach-1,4
Up Type=0
Dn Type=3
Dn Slope=0.005
Boundary for River Rch & Prof#=LWE S WB_1,Reach-1,5
Up Type=0
Dn Type=3
Dn Slope=0.005
Boundary for River Rch & Prof#=LWE S WB_1,Reach-1,6
Up Type=0
Dn Type=3
Dn Slope=0.005
Boundary for River Rch & Prof#=LWE S WB_1,Reach-1,7
Up Type=0
Dn Type=3
Dn Slope=0.005

--- LWE S WB_1.g01 (geometry) ---

Geom Title=Existing Conditions
Program Version=4.10

River Reach=LWE S WB_1      ,Reach-1
Reach XY= 30
        2377429.        7081310.      2377621.13      7081063.22
      2377478.66      7080684.78       2377677.5      7080598.47
       2377679.3      7080184.88       2377336.5      7079863.58
      2377329.08      7079275.39      2377628.47      7078849.52
      2377480.62      7078321.81      2377821.69      7077959.89
      2377239.76      7077419.68      2377023.64       7076757.3
      2376736.89      7076513.58      2376782.45      7076011.23
      2376978.47      7075843.87      2376925.87      7075411.63
      2376531.69      7074815.26      2376089.66      7074859.26
      2375523.14      7074561.57      2375242.34       7074573.8
      2375474.19      7074257.85      2375126.73      7074254.94
       2374899.5      7073829.17      2374636.34      7073816.42
      2374769.59      7073003.34      2374462.36      7072443.29
      2373884.06      7072012.29      2373871.32      7071303.56
      2373473.39      7070815.59        2373229.        7070810.

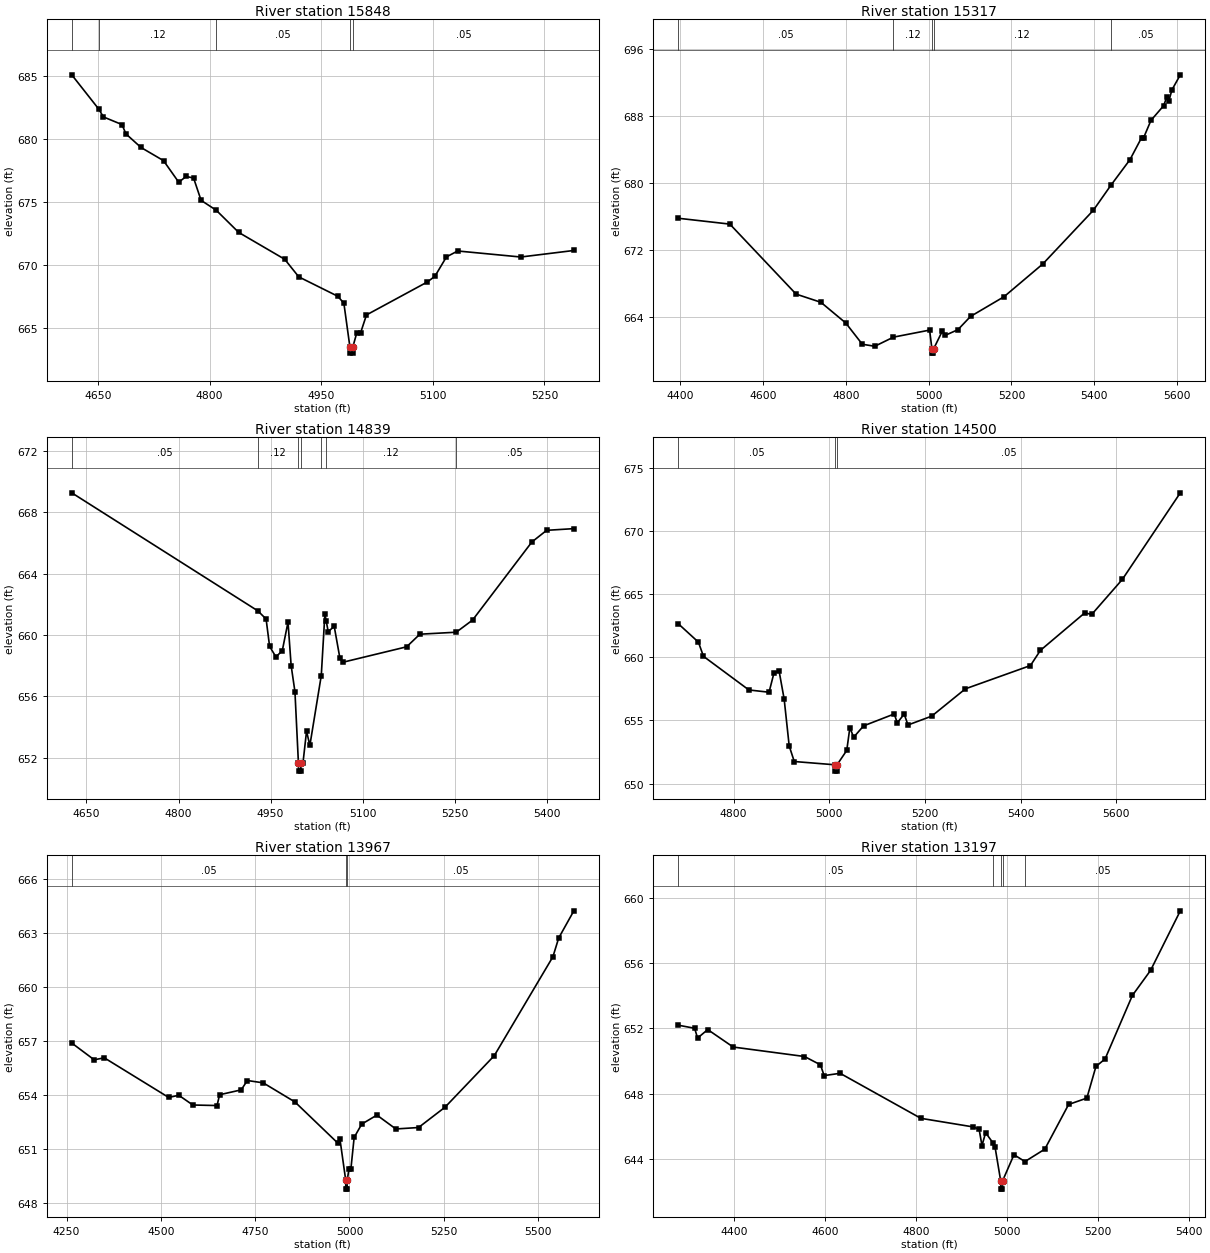
Type RM Length L Ch R = 1 ,15848   ,531,531,531
BEGIN DESCRIPTION:
LWE S WB_1 31.0
END DESCRIPTION:
XS GIS Cut Line= 3
      2377961.09      7081274.38      2377579.65      7081220.67
       2377296.2      7081280.02
#Sta/Elev= 30
  4614.8  685.13  4651.1   682.4  4657.3  681.78  4682.3  681.17  4687.6  680.43
  4707.8  679.35  4738.1   678.3  4758.6  676.58  4768.4  677.04  4778.5  676.92
  4788.6  675.14    4809  674.35  4839.1  672.59    4901  670.45  4919.9  669.05
  4972.2  667.51  4980.5  666.96  4988.6  663.48  4988.8  662.98  4992.3  662.98
  4992.6  663.48  4997.8  664.58  5002.9  664.58  5010.9  666.02  5092.6  668.64
  5102.8  669.09  5118.4  670.64  5133.5  671.11  5218.3  670.63  5289.6  671.15
#Mann= 5 ,-1 , 0
  4614.8     .05       0  4651.1     .12       0    4809     .05       0
  4988.6     .04       0  4992.6     .05       0
Bank Sta=4988.6,4992.6
XS Rating Curve= 0 ,0
Exp/Cntr=0.3,0.1

Type RM Length L Ch R = 1 ,15317   ,478,478,478
BEGIN DESCRIPTION:
LWE S WB_1 30.0
END DESCRIPTION:
XS GIS Cut Line= 3
      2378083.74      7080755.96        2377479.        7080760.
      2376879.03        7080860.
#Sta/Elev= 30
  4395.1  675.83  4519.8  675.13  4679.8  666.77  4739.8  665.79  4799.8  663.32
  4839.8  660.78  4869.9  660.54  4915.1  661.63  5002.4  662.47    5008  660.22
  5008.2  659.72  5011.7  659.72    5012  660.22  5032.8  662.32  5040.4  661.85
  5070.8  662.52  5101.2   664.1  5182.3  666.46  5276.1  670.38  5397.8  676.77
  5440.4  679.77  5486.5  682.83  5514.4  685.44  5519.4  685.44  5537.2  687.52
  5567.6  689.26  5575.2  690.26  5580.3  689.82  5587.9  691.17  5608.1  692.96
#Mann= 5 ,-1 , 0
  4395.1     .05       0  4915.1     .12       0    5008     .07       0
    5012     .12       0  5440.4     .05       0
Bank Sta=5008,5012
XS Rating Curve= 0 ,0
Exp/Cntr=0.3,0.1

Type RM Length L Ch R = 1 ,14839   ,339,339,339
BEGIN DESCRIPTION:
LWE S WB_1 29.0
END DESCRIPTION:
XS GIS Cut Line= 3
      2378041.32      7080523.14      2377679.03      7080430.68
      2377265.31      7080592.13
#Sta/Elev= 30
  4626.1  669.25  4929.2  661.57  4942.7  661.04  4948.4  659.26  4958.7  658.57
  4969.1  658.98  4978.4  660.84  4983.5  658.01  4989.7  656.31  4995.4  651.64
  4995.7  651.14  4999.2  651.14  4999.4  651.64  5002.7  651.64  5008.6  653.74
    5014  652.81  5032.6  657.36  5038.5  661.37  5040.5  660.94  5043.9  660.22
  5053.7  660.56    5063  658.48  5068.3  658.23  5171.7  659.23  5193.2  660.05
  5252.5  660.18  5279.1  660.97  5375.7  666.05  5399.8  666.81  5444.1  666.92
#Mann= 7 ,-1 , 0
  4626.1     .05       0  4929.2     .12       0  4995.4     .07       0
  4999.4     .12       0  5032.6     .05       0  5040.5     .12       0
  5252.5     .05       0
Bank Sta=4995.4,4999.4
XS Rating Curve= 0 ,0
Exp/Cntr=0.3,0.1

Type RM Length L Ch R = 1 ,14500   ,533,533,533
BEGIN DESCRIPTION:
LWE S WB_1 28.0
END DESCRIPTION:
XS GIS Cut Line= 3
      2377929.04      7080210.01        2377629.        7080110.
      2377058.26      7080569.99
#Sta/Elev= 30
  4684.3  662.65  4726.5  661.19    4737  660.07  4831.9  657.41  4874.1  657.23
  4884.6  658.79  4895.2  658.88  4905.7  656.68  4916.2  652.98  4926.8  651.75
  5012.2  651.49  5012.4  650.99  5015.9  650.99  5016.2  651.49  5036.5  652.63
    5043  654.43  5050.9  653.67  5071.7  654.57  5135.7  655.51  5142.1  654.81
  5156.5   655.5  5164.5  654.64  5214.1  655.34  5284.5   657.5  5420.4  659.34
  5441.2  660.54    5534  663.51  5548.4  663.38  5612.4  666.15  5733.6     673
#Mann= 3 ,-1 , 0
  4684.3     .05       0  5012.2    .033       0  5016.2     .05       0
Bank Sta=5012.2,5016.2
XS Rating Curve= 0 ,0
Exp/Cntr=0.3,0.1

Type RM Length L Ch R = 1 ,13967   ,770,770,770
BEGIN DESCRIPTION:
LWE S WB_1 27.0
END DESCRIPTION:
XS GIS Cut Line= 3
      2378121.99      7079982.75      2377421.36      7079756.67
      2376828.96        7079810.
#Sta/Elev= 30
  4263.8   656.9  4323.2  655.97    4350  656.08  4520.7  653.88  4547.5     654
  4584.8  653.46  4648.9  653.43  4655.7  654.03  4712.9   654.3  4729.3  654.82
  4771.3  654.69  4855.4  653.63  4969.3  651.34  4974.5   651.6    4990  649.29
  4990.2  648.79  4993.7  648.79    4994  649.29  4998.6   649.9  5003.7   649.9
  5012.4  651.66  5032.5   652.4  5072.7   652.9  5122.9  652.13  5183.1  652.21
  5253.4  653.34  5383.9   656.2  5539.3  661.69  5554.6  662.73  5594.8  664.24
#Mann= 3 ,-1 , 0
  4263.8     .05       0    4990     .04       0    4994     .05       0
Bank Sta=4990,4994
XS Rating Curve= 0 ,0
Exp/Cntr=0.3,0.1

Type RM Length L Ch R = 1 ,13197   ,336,336,336
BEGIN DESCRIPTION:
LWE S WB_1 26.0
END DESCRIPTION:
XS GIS Cut Line= 3
      2377989.63      7079559.57        2377429.        7079110.
      2377043.71      7079088.68
#Sta/Elev= 30
  4276.5   652.2  4312.6  652.01    4319  651.41  4341.4  651.93  4397.4  650.86
  4554.2  650.28  4589.4  649.77  4597.4  649.11  4632.6  649.25  4810.3  646.49
  4923.9  645.97  4938.3  645.83  4944.7  644.82  4952.7  645.61  4968.7  644.99
  4973.5  644.72  4985.9  642.65  4986.2  642.15  4989.7  642.15  4989.9  642.65
  5015.1  644.26  5039.2  643.84  5082.9   644.6  5135.3  647.34  5175.4  647.73
  5195.4  649.67  5215.5  650.13  5275.5  654.02  5315.6  655.56    5381  659.21
#Mann= 5 ,-1 , 0
  4276.5     .05       0  4968.7     .12       0  4985.9     .07       0
  4989.9     .12       0  5039.2     .05       0
Bank Sta=4985.9,4989.9
XS Rating Curve= 0 ,0
Exp/Cntr=0.3,0.1

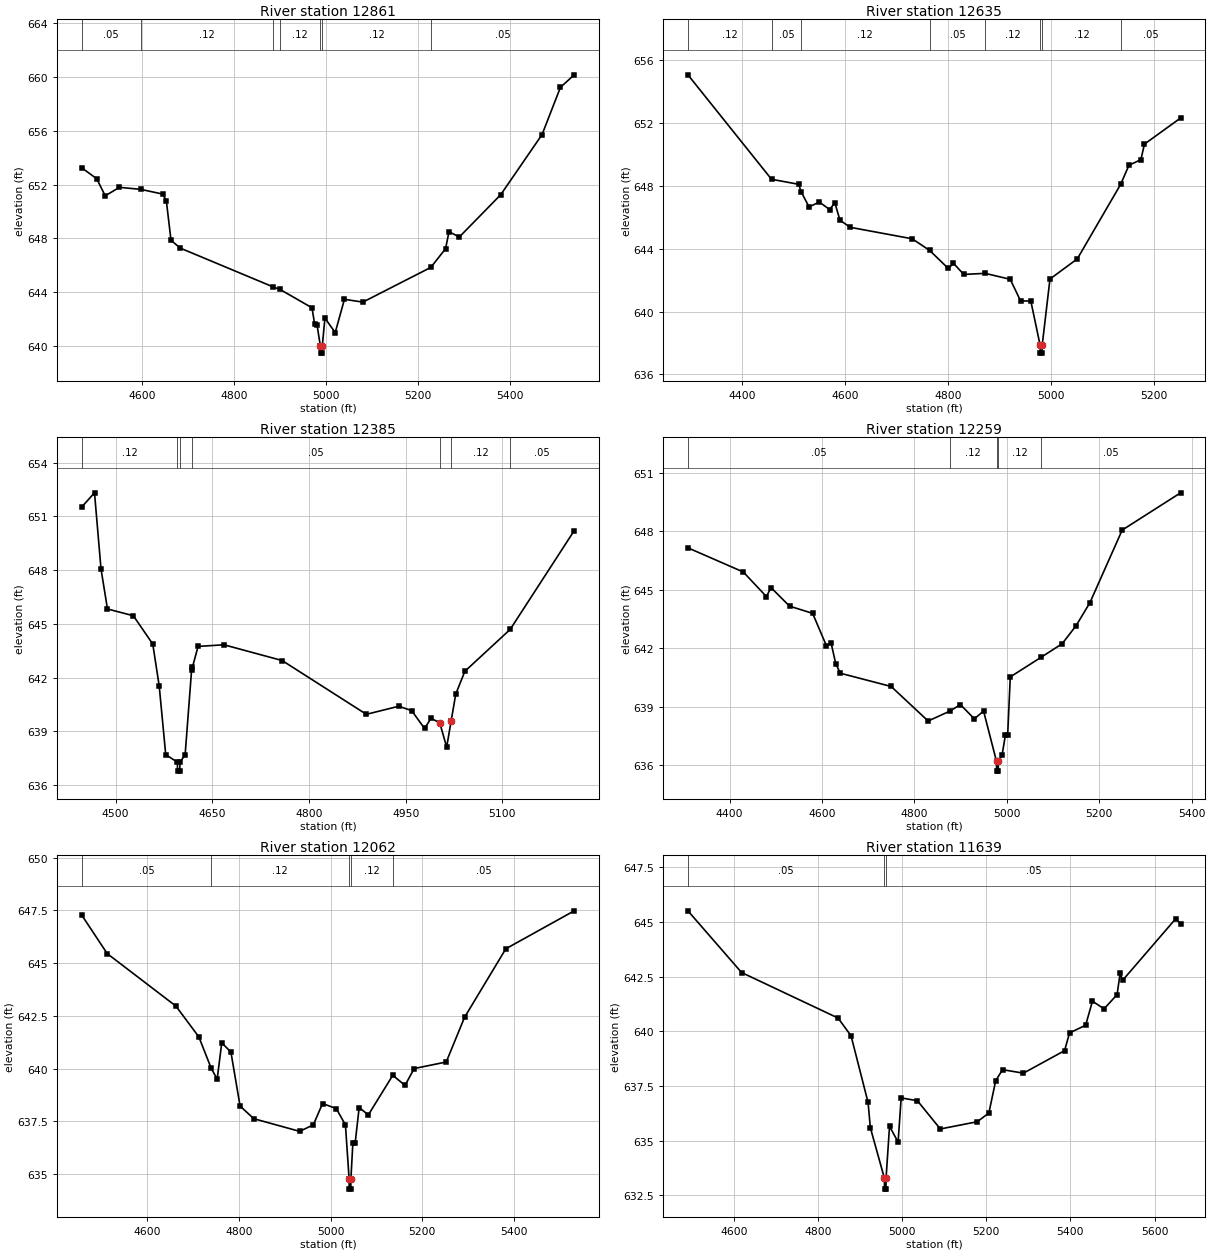
Type RM Length L Ch R = 1 ,12861   ,226,226,226
BEGIN DESCRIPTION:
LWE S WB_1 25.0
END DESCRIPTION:
XS GIS Cut Line= 3
      2378139.39      7078981.25      2377618.94        7078870.
      2377079.04        7078860.
#Sta/Elev= 30
  4467.8  653.25  4500.8  652.43  4519.3  651.16  4550.3  651.79  4596.4  651.64
  4644.2  651.29  4652.3   650.8  4662.5  647.85  4682.9  647.27  4885.5  644.38
  4899.9   644.2  4969.3  642.84  4975.2   641.6  4980.3  641.56  4987.7  639.97
    4988  639.47  4991.5  639.47  4991.7  639.97  4997.4  642.07  5019.9     641
  5039.9  643.47    5080  643.26  5227.9  645.84    5260  647.23  5267.5  648.49
    5290   648.1    5380  651.24    5470  655.71    5510  659.22    5540  660.15
#Mann= 7 ,-1 , 0
  4467.8     .05       0  4596.4     .12       0  4885.5     .05       0
  4899.9     .12       0  4987.7     .07       0  4991.7     .12       0
  5227.9     .05       0
Bank Sta=4987.7,4991.7
XS Rating Curve= 0 ,0
Exp/Cntr=0.3,0.1

Type RM Length L Ch R = 1 ,12635   ,250,250,250
BEGIN DESCRIPTION:
LWE S WB_1 24.0
END DESCRIPTION:
XS GIS Cut Line= 3
      2378233.77      7078665.82      2377529.93      7078694.05
      2377279.04        7078710.
#Sta/Elev= 30
  4295.6  655.08  4457.8  648.43  4510.5  648.11  4515.2  647.64  4530.6  646.67
  4550.6  646.98  4570.6   646.5  4580.6  646.94  4590.6  645.82  4610.6  645.37
  4730.7  644.64  4764.5   643.9  4800.8  642.75  4810.8  643.08  4830.8  642.37
  4872.2  642.44  4920.9  642.06  4940.9  640.69  4960.9  640.67  4978.9  637.86
  4979.2  637.36  4982.7  637.36  4982.9  637.86    4998  642.08    5051  643.36
    5135   648.1  5151.2  649.32  5174.4  649.68  5181.3  650.67  5251.4  652.33
#Mann= 8 ,-1 , 0
  4295.6     .12       0  4457.8     .05       0  4515.2     .12       0
  4764.5     .05       0  4872.2     .12       0  4978.9     .07       0
  4982.9     .12       0    5135     .05       0
Bank Sta=4978.9,4982.9
XS Rating Curve= 0 ,0
Exp/Cntr=0.3,0.1

Type RM Length L Ch R = 1 ,12385   ,126,126,126
BEGIN DESCRIPTION:
LWE S WB_1 23.0
END DESCRIPTION:
XS GIS Cut Line= 3
      2378029.04        7078510.        2377479.        7078460.
      2377329.03      7078609.97
#Sta/Elev= 30
  4447.1  651.51  4467.2  652.31  4477.3  648.06  4487.3  645.83  4527.5  645.45
  4557.6  643.87  4567.6  641.53  4577.7   637.7  4595.8  637.28    4596  636.78
  4599.5  636.78  4599.8  637.28  4607.8  637.69  4617.8   642.4  4619.1  642.57
  4627.9  643.74  4668.1  643.83  4758.4  642.95    4889  639.95  4939.2   640.4
  4959.2  640.16  4979.3  639.16  4989.4  639.73  5002.9  639.47  5013.6  638.12
 5020.57 639.583  5027.7  641.08  5041.8  642.35  5112.2  644.69  5211.5   650.2
#Mann= 7 ,-1 , 0
  4447.1     .12       0  4595.8    .033       0  4599.8     .12       0
  4619.1     .05       0  5002.9    .033       0 5020.57     .12       0
  5112.2     .05       0
#XS Ineff= 2 , 0
       0  4627.9  643.74               0
Permanent Ineff=
       F       F
Bank Sta=5002.9,5020.57
XS Rating Curve= 0 ,0
Exp/Cntr=0.3,0.1

Type RM Length L Ch R = 1 ,12259   ,197,197,197
BEGIN DESCRIPTION:
Mapping XS 0e9602f0
END DESCRIPTION:
XS GIS Cut Line= 3
      2378168.86      7078332.66      2377479.81      7078334.83
       2377102.6      7078340.24
#Sta/Elev= 30
  4309.8  647.15  4429.7  645.91  4479.7  644.65  4489.7  645.11  4529.7  644.16
  4579.7  643.79  4609.7  642.12  4619.7  642.27  4629.7  641.21  4639.7  640.72
  4749.7  640.04  4829.7  638.27  4876.1  638.77  4899.7  639.11  4929.7  638.38
  4949.7  638.78  4977.7   636.2  4977.9   635.7  4981.4   635.7  4981.7   636.2
  4989.7  636.52  4996.8  637.53  5001.8  637.53  5007.5  640.53  5074.3  641.54
  5119.7  642.23  5149.7  643.15  5179.7  644.33  5249.7  648.06  5376.1  649.97
#Mann= 5 ,-1 , 0
  4309.8     .05       0  4876.1     .12       0  4977.7     .07       0
  4981.7     .12       0  5074.3     .05       0
Bank Sta=4977.7,4981.7
XS Rating Curve= 0 ,0
Exp/Cntr=0.3,0.1

Type RM Length L Ch R = 1 ,12062   ,423,423,423
BEGIN DESCRIPTION:
Mapping XS dee496e7
END DESCRIPTION:
XS GIS Cut Line= 3
      2378185.07       7078250.2      2377591.58      7078246.94
      2377109.79      7078264.31
#Sta/Elev= 30
  4456.1  647.29  4512.2  645.45  4662.2  642.96  4712.2   641.5  4739.2  640.01
  4752.2   639.5  4762.2  641.22  4782.2  640.78  4802.2  638.22  4832.2  637.62
  4932.2  637.02  4962.2  637.33  4982.2  638.34  5012.2   638.1  5032.2  637.33
  5040.2  634.78  5040.4  634.28  5043.9  634.28  5044.2  634.78  5048.4  636.46
  5053.4  636.46  5062.2  638.15  5082.2   637.8  5135.6  639.68  5162.3   639.2
  5182.3     640  5252.3  640.31  5292.3  642.43  5382.4  645.68  5531.7  647.48
#Mann= 5 ,-1 , 0
  4456.1     .05       0  4739.2     .12       0  5040.2     .07       0
  5044.2     .12       0  5135.6     .05       0
Bank Sta=5040.2,5044.2
XS Rating Curve= 0 ,0
Exp/Cntr=0.3,0.1

Type RM Length L Ch R = 1 ,11639   ,284,284,284
BEGIN DESCRIPTION:
LWE S WB_1 22.0
END DESCRIPTION:
XS GIS Cut Line= 3
      2378279.01        7077810.      2377779.58      7077909.75
      2377195.81      7078221.93
#Sta/Elev= 30
  4490.7  645.51  4618.3  642.69  4847.6  640.61  4878.5   639.8    4919  636.75
  4924.4   635.6  4957.8  633.29  4958.1  632.79  4961.6  632.79  4961.8  633.29
    4970  635.66  4990.4  634.94  4997.7  636.96  5036.3  636.83  5090.8  635.54
  5178.6  635.87  5206.2  636.27  5222.5  637.75  5238.8  638.25  5288.3  638.09
  5386.2  639.12    5398  639.93  5436.2  640.28  5452.5  641.38  5480.1  641.03
    5511  641.68  5518.4  642.67    5524  642.33    5650  645.14    5662  644.93
#Mann= 3 ,-1 , 0
  4490.7     .05       0  4957.8    .033       0  4961.8     .05       0
Bank Sta=4957.8,4961.8
XS Rating Curve= 0 ,0
Exp/Cntr=0.3,0.1

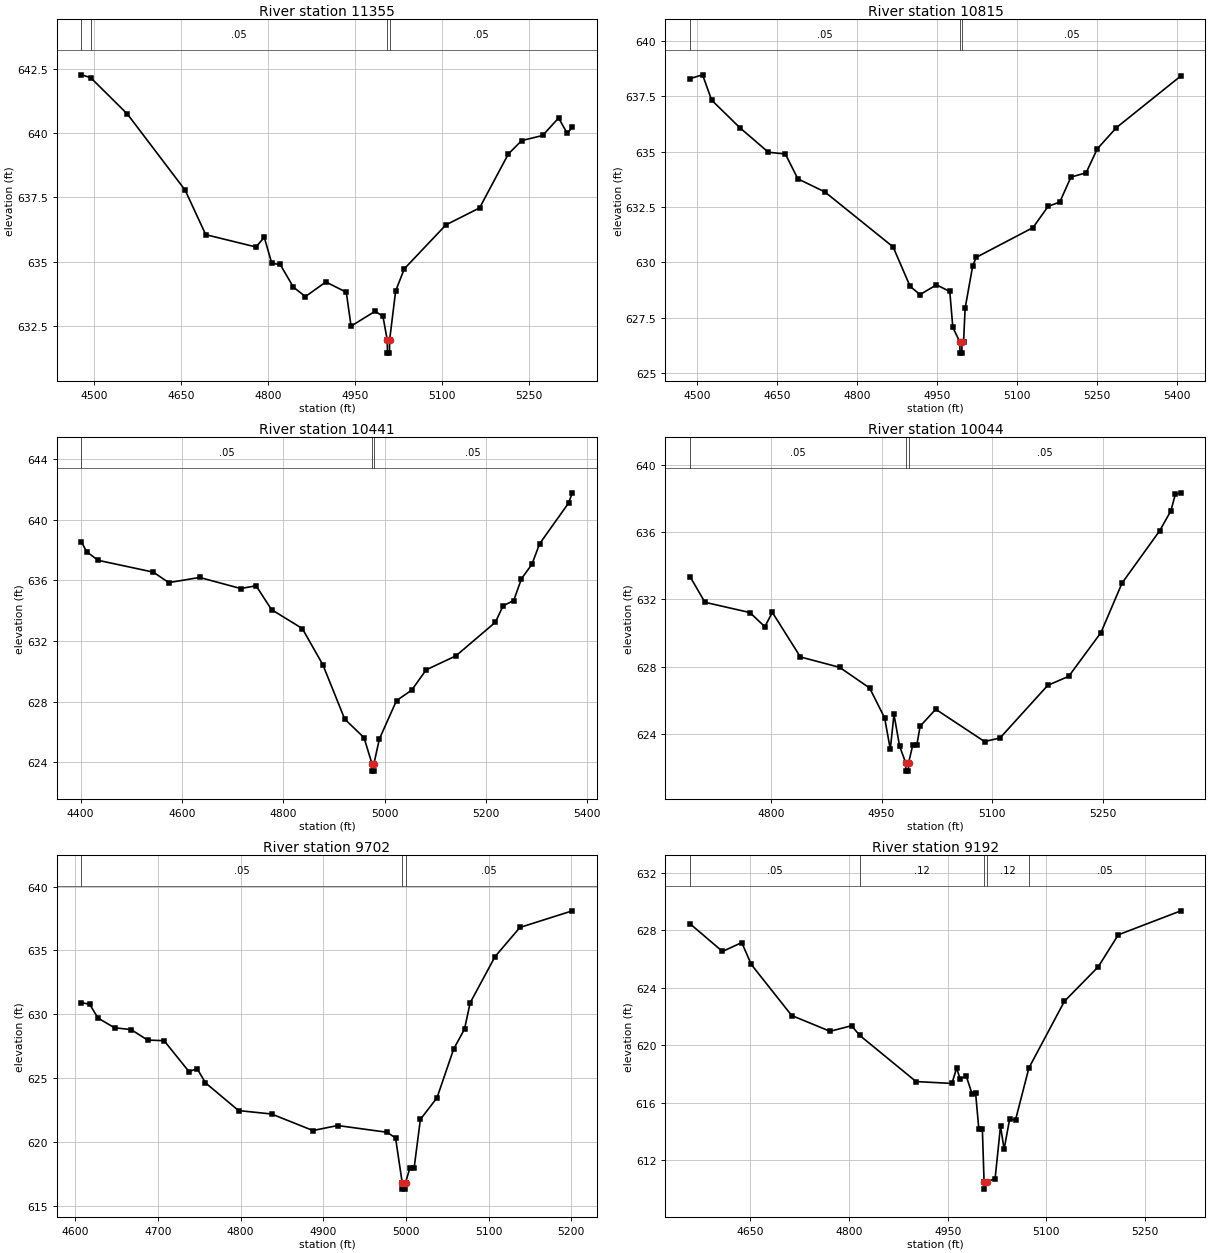
Type RM Length L Ch R = 1 ,11355   ,540,540,540
BEGIN DESCRIPTION:
LWE S WB_1 21.0
END DESCRIPTION:
XS GIS Cut Line= 3
      2377958.88      7077458.12      2377545.64      7077776.71
      2377276.64      7077959.82
#Sta/Elev= 30
  4478.2  642.27  4494.1  642.16  4557.6  640.74  4657.2  637.78  4692.7  636.05
  4779.5  635.57  4793.7  635.95  4806.7  634.93  4821.2  634.89  4843.9  634.01
  4864.7  633.64    4900  634.21  4935.3  633.81  4943.5  632.49  4985.1  633.07
  4998.6  632.87    5006  631.94  5006.3  631.44  5009.8  631.44    5010  631.94
  5020.5  633.86  5035.4  634.72  5107.2  636.43  5165.3  637.09    5215  639.19
  5237.9  639.71  5274.2  639.91  5301.7  640.59  5316.7  639.99  5325.4  640.24
#Mann= 4 ,-1 , 0
  4478.2     .12       0  4494.1     .05       0    5006     .04       0
    5010     .05       0
Bank Sta=5006,5010
XS Rating Curve= 0 ,0
Exp/Cntr=0.3,0.1

Type RM Length L Ch R = 1 ,10815   ,374,374,374
BEGIN DESCRIPTION:
LWE S WB_1 20.0
END DESCRIPTION:
XS GIS Cut Line= 3
      2377707.11      7077187.34      2377224.78      7077361.75
      2376918.06      7077630.04
#Sta/Elev= 30
  4487.1  638.29  4510.7  638.46  4527.6  637.32  4580.8  636.07    4634  634.97
  4665.9  634.89  4689.3  633.77  4739.9  633.18  4867.9   630.7  4899.8  628.92
  4918.5  628.55  4949.2  628.99  4974.2  628.69  4979.9  627.07  4993.1  626.41
  4993.3  625.91  4996.8  625.91  4997.1  626.41    5000  626.41    5003  627.94
  5017.2  629.85  5023.9  630.23  5130.2  631.57  5158.6  632.53  5180.4  632.72
  5201.4  633.85  5229.8  634.04  5250.7  635.12  5286.7  636.08  5407.5  638.41
#Mann= 3 ,-1 , 0
  4487.1     .05       0  4993.1     .04       0  4997.1     .05       0
Bank Sta=4993.1,4997.1
XS Rating Curve= 0 ,0
Exp/Cntr=0.3,0.1

Type RM Length L Ch R = 1 ,10441   ,397,397,397
BEGIN DESCRIPTION:
LWE S WB_1 19.0
END DESCRIPTION:
XS GIS Cut Line= 3
        2377679.        7076960.        2377079.        7077060.
      2376779.03      7077259.98
#Sta/Elev= 30
  4401.7  638.55  4411.8   637.9  4434.6  637.33  4543.6  636.55    4574  635.86
  4634.9   636.2    4716  635.47  4746.4  635.65  4776.8  634.08  4837.6  632.83
  4878.2  630.44  4921.3  626.86  4959.3  625.64    4975  623.93  4975.3  623.43
  4978.8  623.43    4979  623.93  4989.7  625.55  5023.5  628.08  5053.5  628.77
  5082.1  630.11  5140.7  631.03  5218.8  633.25  5233.8  634.33  5254.9  634.68
  5269.9   636.1  5290.9  637.08  5305.9  638.42    5363   641.1  5370.5  641.78
#Mann= 3 ,-1 , 0
  4401.7     .05       0    4975     .04       0    4979     .05       0
Bank Sta=4975,4979
XS Rating Curve= 0 ,0
Exp/Cntr=0.3,0.1

Type RM Length L Ch R = 1 ,10044   ,342,342,342
BEGIN DESCRIPTION:
LWE S WB_1 18.0
END DESCRIPTION:
XS GIS Cut Line= 3
      2377278.97      7076759.99        2376979.        7076710.
      2376678.97      7076910.02
#Sta/Elev= 30
  4690.6  633.35  4710.8  631.82  4771.7  631.21  4791.9  630.37  4802.1  631.22
  4840.1  628.57  4893.3  627.95  4933.9  626.72  4954.2  624.94  4961.8  623.08
  4966.8  625.15  4974.4  623.27  4982.6  622.28  4982.8  621.78  4986.3  621.78
  4986.6  622.28  4992.2  623.32  4997.7  623.32  5002.2  624.45  5023.3  625.46
  5089.4  623.54  5110.4  623.75    5175  626.88  5203.5  627.42  5247.1  630.02
  5275.6  632.96  5326.7  636.08  5341.7  637.25  5347.8  638.24  5355.3  638.33
#Mann= 3 ,-1 , 0
  4690.6     .05       0  4982.6     .04       0  4986.6     .05       0
Bank Sta=4982.6,4986.6
XS Rating Curve= 0 ,0
Exp/Cntr=0.3,0.1

Type RM Length L Ch R = 1 ,9702    ,510,510,510
BEGIN DESCRIPTION:
LWE S WB_1 17.0
END DESCRIPTION:
XS GIS Cut Line= 3
        2377129.        7076510.        2376729.        7076510.
      2376535.84      7076525.72
#Sta/Elev= 30
  4607.5  630.93  4617.5  630.79  4627.5  629.72  4647.5  628.96  4667.5  628.82
  4687.5     628  4707.5  627.95  4737.5  625.54  4747.5  625.76  4757.5  624.66
  4797.5  622.49  4837.5  622.22  4887.5  620.93  4917.5  621.32  4977.5  620.79
  4987.5  620.34  4995.5  616.85  4995.8  616.35  4999.3  616.35  4999.5  616.85
    5005  618.04    5010  618.04  5017.5   621.8  5037.6  623.49  5057.7  627.29
  5070.9  628.86  5077.7  630.91  5107.8  634.52  5137.9   636.8  5201.3   638.1
#Mann= 3 ,-1 , 0
  4607.5     .05       0  4995.5     .04       0  4999.5     .05       0
Bank Sta=4995.5,4999.5
XS Rating Curve= 0 ,0
Exp/Cntr=0.3,0.1

Type RM Length L Ch R = 1 ,9192    ,539,539,539
BEGIN DESCRIPTION:
LWE S WB_1 16.0
END DESCRIPTION:
XS GIS Cut Line= 3
      2377184.35       7076267.2      2376779.14      7076091.14
      2376502.56      7076218.98
#Sta/Elev= 30
  4558.2  628.45  4607.6  626.52  4636.9  627.14  4651.3  625.62  4712.8  622.06
  4771.2  620.96  4803.9  621.35  4816.2  620.68    4902  617.46  4956.5  617.33
  4963.6  618.39  4969.1  617.64  4978.3  617.84  4987.1  616.61  4992.5  616.68
  4997.4  614.17  5002.8  614.17  5005.4  610.47  5005.7  609.97  5009.4  610.47
  5022.2  610.71  5030.4  614.35  5035.9  612.75  5044.2  614.83  5053.3   614.8
  5073.6  618.41  5127.6  623.05    5179  625.45  5209.5  627.68  5304.7  629.35
#Mann= 5 ,-1 , 0
  4558.2     .05       0  4816.2     .12       0  5005.4     .07       0
  5009.4     .12       0  5073.6     .05       0
Bank Sta=5005.4,5009.4
XS Rating Curve= 0 ,0
Exp/Cntr=0.3,0.1

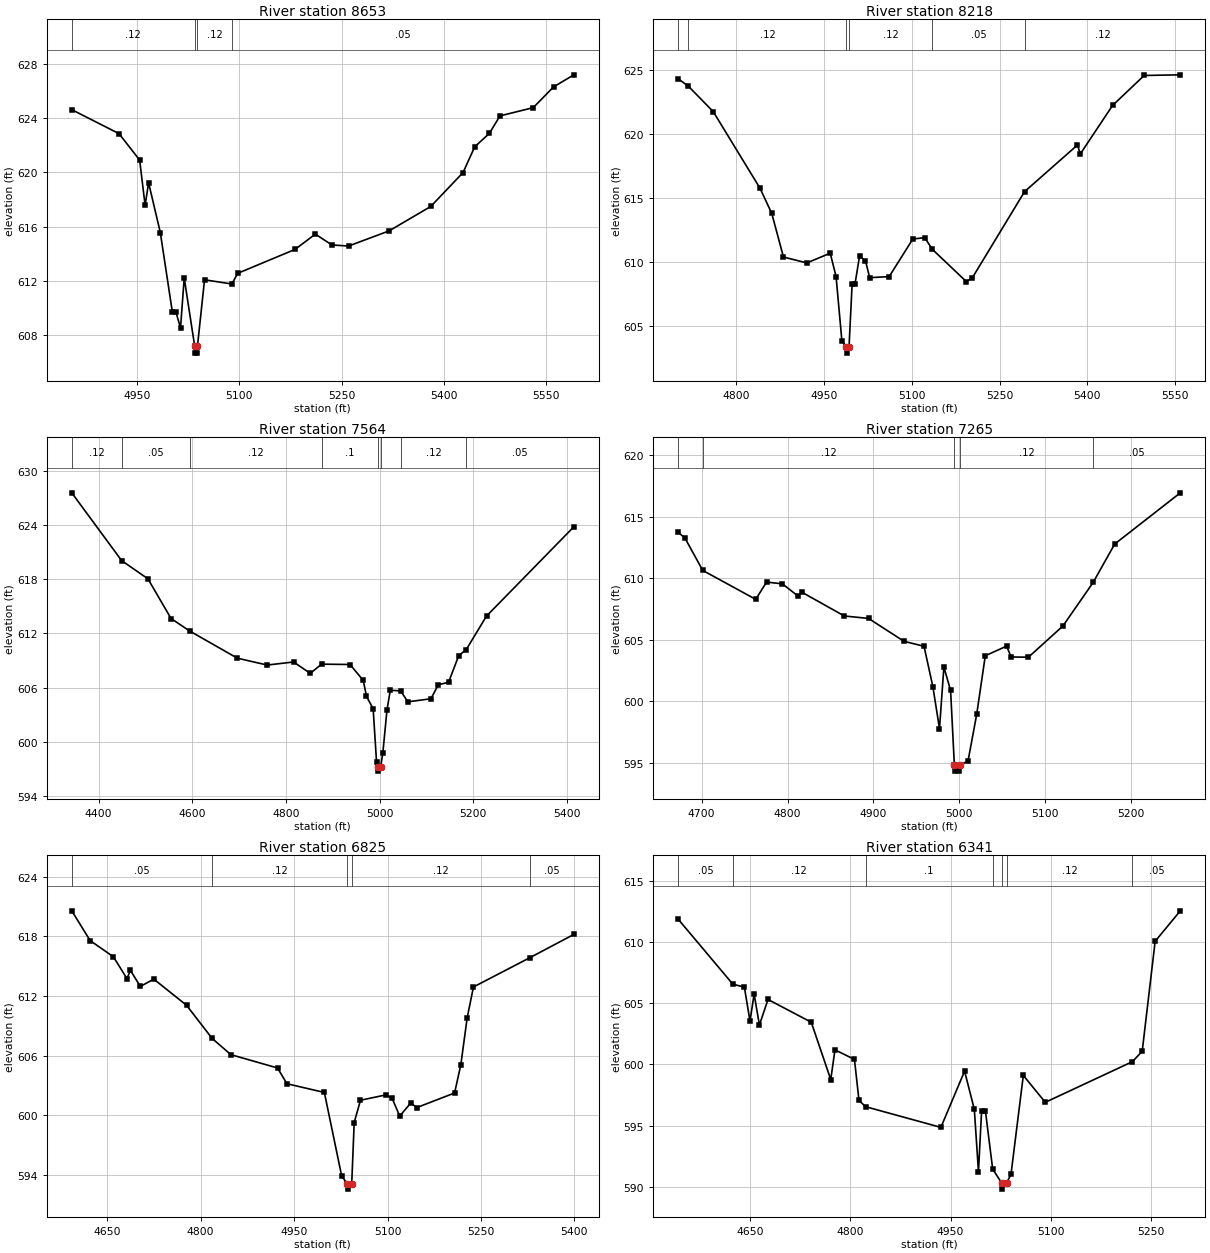
Type RM Length L Ch R = 1 ,8653    ,435,435,435
BEGIN DESCRIPTION:
LWE S WB_1 15.0
END DESCRIPTION:
XS GIS Cut Line= 3
      2377077.72      7075729.01        2376929.        7075710.
      2376383.87      7075924.94
#Sta/Elev= 30
  4854.3  624.62  4923.6  622.85  4953.8   620.9  4961.8  617.56  4966.9  619.23
  4984.1  615.55  5001.7   609.7  5006.9   609.7  5013.7  608.52  5019.1  612.21
  5034.5  607.16  5034.7  606.66  5038.2  606.66  5038.5  607.16  5048.9  612.07
  5088.9  611.76  5097.6  612.55  5181.5  614.31  5211.3  615.44  5235.6  614.64
    5260  614.56  5319.5  615.68  5380.5  617.48  5427.8  619.98  5444.9  621.88
  5466.4  622.87  5481.9  624.16  5530.7  624.77  5560.5   626.3  5590.2  627.19
#Mann= 4 ,-1 , 0
  4854.3     .12       0  5034.5     .07       0  5038.5     .12       0
  5088.9     .05       0
Bank Sta=5034.5,5038.5
XS Rating Curve= 0 ,0
Exp/Cntr=0.3,0.1

Type RM Length L Ch R = 1 ,8218    ,654,654,654
BEGIN DESCRIPTION:
LWE S WB_1 14.0
END DESCRIPTION:
XS GIS Cut Line= 3
      2377178.96        7075360.        2376879.        7075360.
      2376328.07      7075454.27
#Sta/Elev= 30
  4700.4  624.27  4717.6  623.71  4760.4  621.71  4840.4  615.73  4860.4  613.77
  4880.4  610.37  4920.4  609.91  4960.4  610.67  4970.4  608.85  4980.4  603.81
  4988.2  603.37  4988.6  602.87  4992.6  603.37  4997.9   608.3  5002.9   608.3
  5010.5  610.42  5020.7  610.08  5027.9  608.76  5061.2  608.84  5101.8  611.78
  5122.1  611.88  5135.1  610.97  5193.1  608.46    5203  608.71  5292.8  615.47
  5383.3  619.11  5388.3  618.42  5443.4   622.2  5497.5  624.54  5559.3  624.59
#Mann= 6 ,-1 , 0
  4700.4     .05       0  4717.6     .12       0  4988.2     .07       0
  4992.6     .12       0  5135.1     .05       0  5292.8     .12       0
Bank Sta=4988.2,4992.6
XS Rating Curve= 0 ,0
Exp/Cntr=0.3,0.1

Type RM Length L Ch R = 1 ,7564    ,299,299,299
BEGIN DESCRIPTION:
LWE S WB_1 13.0
END DESCRIPTION:
XS GIS Cut Line= 3
      2377041.03      7074392.06      2376565.77      7074846.12
      2376363.12      7075208.17
#Sta/Elev= 30
  4342.7  627.56  4449.2  620.06  4505.4  618.04  4554.7  613.65  4594.7  612.26
  4696.3  609.26  4760.1   608.5  4816.4  608.84    4852  607.58  4876.3   608.6
  4936.9  608.56  4965.2   606.8  4972.1  605.03  4986.3  603.67  4993.5  597.82
  4995.9  597.26    4997  596.76  5002.4  597.26  5006.9  598.74  5015.9  603.55
  5022.9  605.71  5044.9  605.64  5060.5  604.43  5109.7  604.77  5125.6  606.33
  5147.3  606.58    5169  609.54  5185.2  610.22  5228.4  613.92  5414.9   623.8
#Mann= 8 ,-1 , 0
  4342.7     .12       0  4449.2     .05       0  4594.7     .12       0
  4876.3      .1       0  4995.9     .07       0  5002.4      .1       0
  5044.9     .12       0  5185.2     .05       0
Bank Sta=4995.9,5002.4
XS Rating Curve= 0 ,0
Exp/Cntr=0.3,0.1

Type RM Length L Ch R = 1 ,7265    ,440,440,440
BEGIN DESCRIPTION:
LWE S WB_1 12.0
END DESCRIPTION:
XS GIS Cut Line= 3
      2376358.19      7074492.45        2376279.        7074810.
      2376302.53      7075066.04
#Sta/Elev= 30
  4672.8  613.72  4680.6  613.26  4701.3  610.63    4763  608.28  4775.6  609.68
    4794  609.54  4811.8  608.57  4816.9  608.85  4866.1  606.93  4894.3  606.73
  4935.6  604.87  4958.9  604.47  4969.2  601.18  4976.9  597.78    4982  602.78
  4989.8  600.89  4994.2  594.83  4995.2  594.33  4999.8  594.33  5000.9  594.83
  5010.1  595.15  5020.2  598.94  5030.2   603.7    5055  604.48  5060.3   603.6
  5080.4  603.58  5120.6  606.12  5155.8  609.66  5180.8  612.77  5257.2  616.93
#Mann= 5 ,-1 , 0
  4672.8     .05       0  4701.3     .12       0  4994.2     .07       0
  5000.9     .12       0  5155.8     .05       0
Bank Sta=4994.2,5000.9
XS Rating Curve= 0 ,0
Exp/Cntr=0.3,0.1

Type RM Length L Ch R = 1 ,6825    ,484,484,484
BEGIN DESCRIPTION:
LWE S WB_1 11.0
END DESCRIPTION:
XS GIS Cut Line= 3
        2376129.        7074360.        2375929.        7074710.
        2375879.      7075109.97
#Sta/Elev= 30
    4593  620.56  4622.5  617.57  4659.9  615.94  4681.5  613.76  4687.3  614.57
  4703.1  612.96  4724.7   613.7  4777.3  611.07  4818.4  607.74  4848.5  606.11
  4923.4  604.77  4938.5  603.19  4998.6  602.31  5026.3  593.95  5035.4   593.1
  5036.5   592.6  5042.5   593.1  5046.5  599.29  5056.6  601.53  5096.9  602.06
    5107  601.78  5119.6  599.94  5137.2  601.24  5147.3   600.8  5207.7  602.26
  5217.8  605.12  5227.9  609.81    5238  612.91  5328.2  615.84  5399.2  618.19
#Mann= 5 ,-1 , 0
    4593     .05       0  4818.4     .12       0  5035.4     .07       0
  5042.5     .12       0  5328.2     .05       0
Bank Sta=5035.4,5042.5
XS Rating Curve= 0 ,0
Exp/Cntr=0.3,0.1

Type RM Length L Ch R = 1 ,6341    ,870,870,870
BEGIN DESCRIPTION:
LWE S WB_1 10.0
END DESCRIPTION:
XS GIS Cut Line= 3
      2375886.82      7074288.48      2375518.52      7074560.55
      2375449.73       7074846.7
#Sta/Elev= 30
  4542.1  611.87  4623.9  606.56  4641.2  606.32  4649.6  603.54  4655.8  605.75
  4663.7  603.22  4676.6  605.31  4741.4  603.45  4770.6  598.76  4776.9  601.19
  4806.1  600.41  4812.9  597.05  4822.9  596.54  4935.6  594.85  4971.1  599.45
  4985.7  596.32  4991.9  591.22  4996.6   596.2  5002.3   596.2  5013.2  591.44
  5026.7   590.3  5027.8   589.8  5033.9   590.3  5040.6     591  5059.1   599.1
    5092   596.9  5222.4  600.22  5237.2  601.07  5256.6  610.07  5294.3  612.56
#Mann= 7 ,-1 , 0
  4542.1     .05       0  4623.9     .12       0  4822.9      .1       0
  5013.2     .12       0  5026.7     .07       0  5033.9     .12       0
  5222.4     .05       0
Bank Sta=5026.7,5033.9
XS Rating Curve= 0 ,0
Exp/Cntr=0.3,0.1

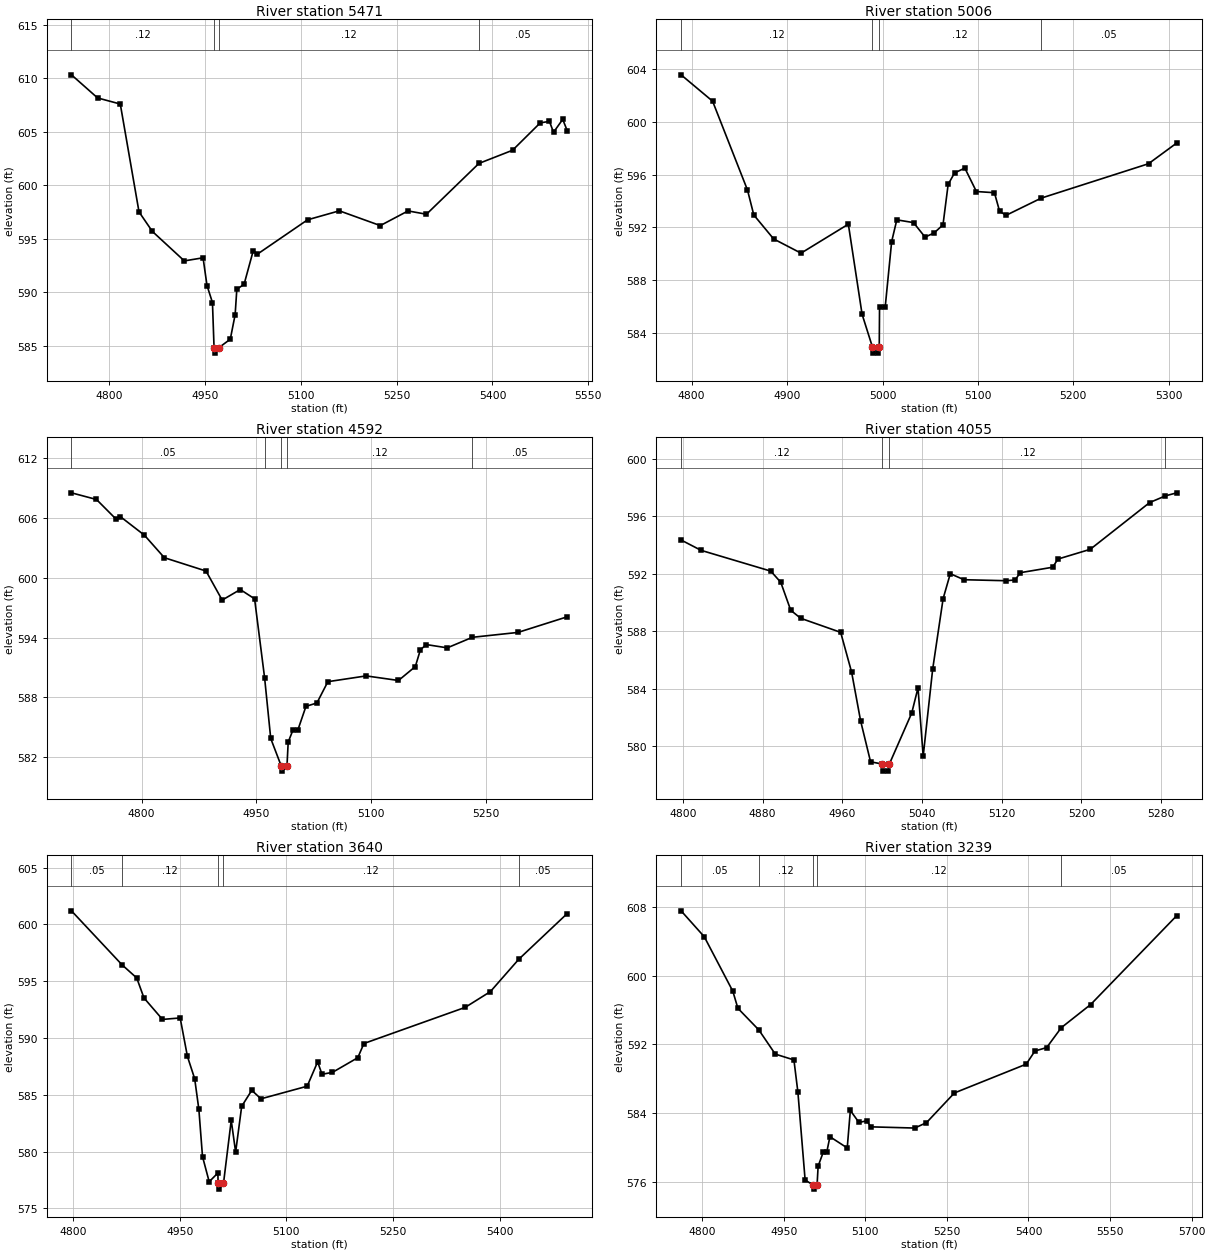
Type RM Length L Ch R = 1 ,5471    ,465,465,465
BEGIN DESCRIPTION:
LWE S WB_1 9.0
END DESCRIPTION:
XS GIS Cut Line= 3
      2375589.09      7074052.36      2375380.78      7074205.77
      2375060.42      7074611.42
#Sta/Elev= 30
  4741.3  610.32  4782.2  608.16  4817.7  607.59    4847  597.51  4867.8  595.69
  4917.9  592.93  4947.2  593.22  4953.4  590.62  4961.9  589.04  4964.4  584.81
  4965.5  584.31  4971.7  584.81  4989.8  585.61  4997.4  587.91    5000  590.27
  5011.4  590.75  5025.8   593.9  5032.2  593.56  5110.7  596.77  5160.4  597.61
  5224.5  596.23  5267.9   597.6  5296.7  597.29  5378.8  602.04  5431.4  603.27
  5474.7  605.83  5489.1  605.97  5495.5  604.95  5509.9  606.16  5516.9   605.1
#Mann= 4 ,-1 , 0
  4741.3     .12       0  4964.4     .07       0  4971.7     .12       0
  5378.8     .05       0
Bank Sta=4964.4,4971.7
XS Rating Curve= 0 ,0
Exp/Cntr=0.3,0.1

Type RM Length L Ch R = 1 ,5006    ,414,414,414
BEGIN DESCRIPTION:
LWE S WB_1 8.0
END DESCRIPTION:
XS GIS Cut Line= 3
      2375162.03       7073995.9        2375029.        7074160.
       2374914.5       7074446.3
#Sta/Elev= 30
  4788.9  603.57  4821.9  601.57  4858.5  594.82  4865.1  592.93  4885.9  591.11
  4914.6  590.03  4964.2  592.23  4978.6  585.39  4989.3  582.94  4990.4  582.44
  4995.5  582.44  4996.6  582.94  4996.9  585.92  5002.8  585.92  5009.6  590.91
    5015  592.56  5032.5  592.35  5044.6  591.25    5054  591.56  5063.4  592.18
  5068.8  595.25  5075.5  596.12  5086.3  596.49  5098.4  594.71  5117.3  594.62
  5122.7  593.22  5129.4   592.9  5166.4  594.21  5278.8  596.82  5308.5   598.4
#Mann= 4 ,-1 , 0
  4788.9     .12       0  4989.3     .07       0  4996.6     .12       0
  5166.4     .05       0
Bank Sta=4989.3,4996.6
XS Rating Curve= 0 ,0
Exp/Cntr=0.3,0.1

Type RM Length L Ch R = 1 ,4592    ,537,537,537
BEGIN DESCRIPTION:
LWE S WB_1 7.0
END DESCRIPTION:
XS GIS Cut Line= 3
      2375185.18      7073744.46      2374909.42      7073838.95
      2374678.97      7074110.03
#Sta/Elev= 30
  4708.5  608.55  4741.2  607.88  4767.2  605.87  4772.5  606.15  4803.8  604.29
  4829.8  602.03  4884.2  600.69  4905.3  597.77  4928.9  598.83  4947.6   597.9
  4960.7  589.96  4968.7  583.86  4982.5  581.08  4983.7  580.58  4989.9  581.08
  4991.5   583.5  4997.6  584.69    5004  584.69  5014.7  587.09    5029  587.43
  5043.3  589.57  5093.3  590.15  5135.5  589.69  5157.5  591.09  5164.1  592.77
  5171.8   593.3  5199.2  592.97    5232  594.03  5291.5  594.52  5355.8  596.09
#Mann= 5 ,-1 , 0
  4708.5     .05       0  4960.7     .12       0  4982.5     .07       0
  4989.9     .12       0    5232     .05       0
Bank Sta=4982.5,4989.9
XS Rating Curve= 0 ,0
Exp/Cntr=0.3,0.1

Type RM Length L Ch R = 1 ,4055    ,415,415,415
BEGIN DESCRIPTION:
LWE S WB_1 6.0
END DESCRIPTION:
XS GIS Cut Line= 3
      2374928.98        7073660.      2374727.37      7073653.96
      2374445.16      7073742.26
#Sta/Elev= 30
  4798.3  594.36  4818.3  593.64  4888.3  592.19  4898.3  591.41  4908.3  589.46
  4918.3   588.9  4958.4  587.92  4969.4  585.14  4978.4  581.75  4988.4  578.89
  4999.8  578.74  5000.9  578.24  5006.1  578.24  5007.3  578.74  5029.7  582.29
    5036  584.05  5041.2  579.28  5050.7  585.34  5061.2  590.27  5068.4  592.01
  5082.1  591.59    5124  591.52  5133.4  591.57  5138.6  592.08  5171.1  592.46
  5176.4  593.03  5208.8  593.71  5268.4  596.97  5284.3  597.44  5295.7  597.65
#Mann= 4 ,-1 , 0
  4798.3     .12       0  4999.8     .07       0  5007.3     .12       0
  5284.3     .05       0
Bank Sta=4999.8,5007.3
XS Rating Curve= 0 ,0
Exp/Cntr=0.3,0.1

Type RM Length L Ch R = 1 ,3640    ,401,401,401
BEGIN DESCRIPTION:
LWE S WB_1 5.0
END DESCRIPTION:
XS GIS Cut Line= 3
      2374929.03      7073310.01      2374730.69      7073270.68
      2374329.03      7073559.98
#Sta/Elev= 30
  4797.8   601.2  4868.9  596.45  4889.6  595.29  4899.8  593.53  4925.8  591.64
  4950.7  591.77  4960.9  588.38  4971.1  586.42    4977  583.71  4982.1  579.57
  4991.5  577.35  5003.7  578.12  5004.1   577.2  5005.2   576.7  5011.6   577.2
  5022.5  582.75  5028.7  579.96  5037.2  583.99  5051.4   585.4  5064.3  584.65
  5129.3  585.76    5144   587.9  5150.2  586.81  5164.9  586.98  5200.5  588.27
  5209.1  589.52  5351.5   592.7    5387  594.09  5426.8  596.93    5495  600.96
#Mann= 5 ,-1 , 0
  4797.8     .05       0  4868.9     .12       0  5004.1     .07       0
  5011.6     .12       0  5426.8     .05       0
Bank Sta=5004.1,5011.6
XS Rating Curve= 0 ,0
Exp/Cntr=0.3,0.1

Type RM Length L Ch R = 1 ,3239    ,454,454,454
BEGIN DESCRIPTION:
LWE S WB_1 4.0
END DESCRIPTION:
XS GIS Cut Line= 3
      2374960.39      7072873.32      2374728.76      7072930.15
       2374143.1       7073261.3
#Sta/Elev= 30
  4761.5  607.58  4804.1  604.56  4856.6  598.21  4865.9  596.22  4904.5  593.69
  4934.6  590.88  4968.9   590.2  4976.2  586.45  4989.5   576.2  5003.8  575.64
    5005  575.14  5011.5  575.64  5013.4  577.82  5022.7  579.42  5029.3  579.46
  5035.1  581.25  5066.9  579.94  5072.6  584.31  5088.5  582.91  5103.1  583.11
  5110.1   582.4    5191  582.26  5212.6  582.89  5263.9  586.35    5396  589.71
  5411.9  591.24  5433.5  591.64  5460.4  593.96  5514.4  596.66  5672.8  607.03
#Mann= 5 ,-1 , 0
  4761.5     .05       0  4904.5     .12       0  5003.8     .07       0
  5011.5     .12       0  5460.4     .05       0
Bank Sta=5003.8,5011.5
XS Rating Curve= 0 ,0
Exp/Cntr=0.3,0.1