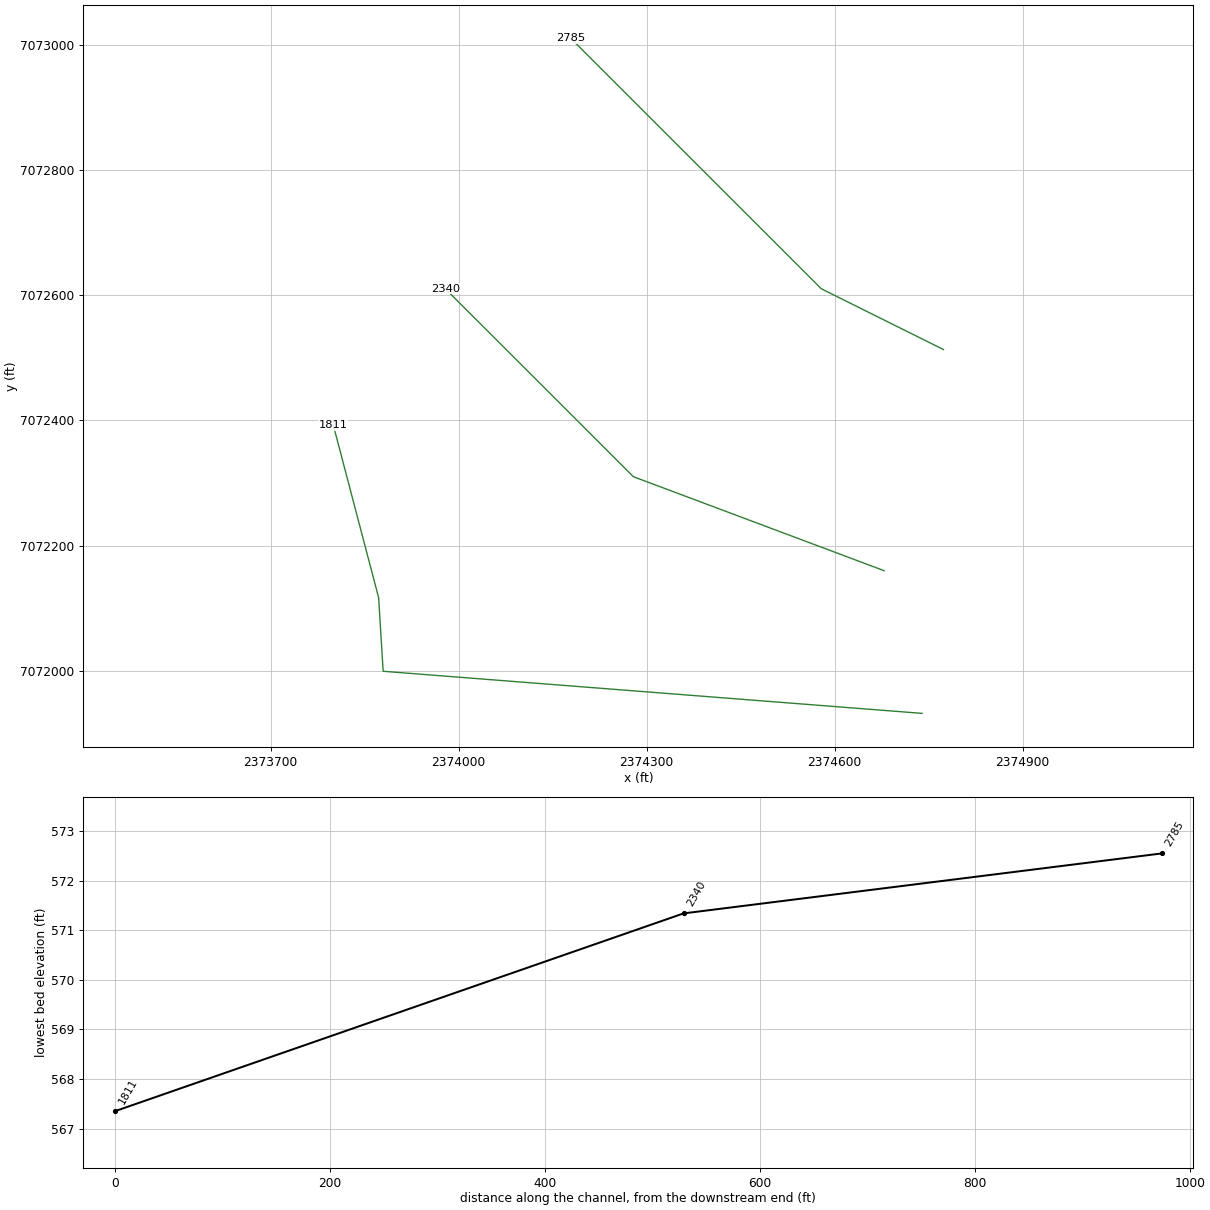
HEC-RAS study LWE S WB_1.prj: LWE S WB_1 Base Level Engineering

--- LWE S WB_1.g01 (geometry) --- (continued)

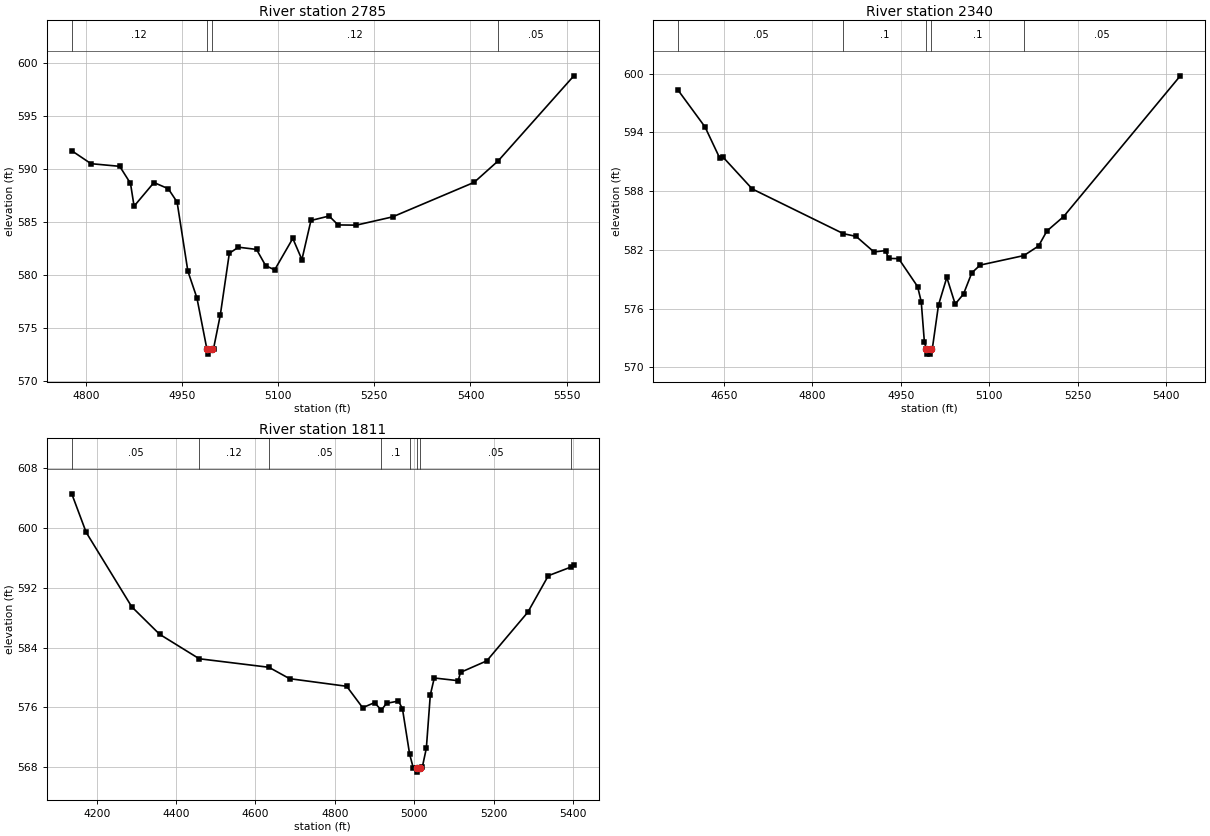
Type RM Length L Ch R = 1 ,2785    ,445,445,445
BEGIN DESCRIPTION:
LWE S WB_1 3.0
END DESCRIPTION:
XS GIS Cut Line= 3
      2374773.75      7072513.09        2374579.        7072610.
      2374179.01      7073009.99
#Sta/Elev= 30
  4778.1  591.74  4808.1  590.52  4852.9  590.27  4869.7  588.66  4875.3  586.51
  4906.3  588.74  4928.6  588.16  4942.4   586.9  4959.2  580.38  4973.3  577.86
  4988.8  573.05    4990  572.55  4996.8  573.05  4999.2  573.05  5009.8  576.24
  5023.9  582.07  5038.1  582.64  5066.3  582.43  5080.5   580.9  5094.6   580.5
  5122.9  583.47  5137.1  581.47  5151.2  585.16  5179.5  585.58  5193.6  584.74
  5221.9  584.72  5278.5   585.5  5405.8  588.76  5443.5   590.8  5561.3  598.81
#Mann= 4 ,-1 , 0
  4778.1     .12       0  4988.8     .07       0  4996.8     .12       0
  5443.5     .05       0
Bank Sta=4988.8,4996.8
XS Rating Curve= 0 ,0
Exp/Cntr=0.3,0.1

Type RM Length L Ch R = 1 ,2340    ,529,529,529
BEGIN DESCRIPTION:
LWE S WB_1 2.0
END DESCRIPTION:
XS GIS Cut Line= 3
      2374679.03      7072159.99        2374279.        7072310.
      2373978.99      7072610.01
#Sta/Elev= 30
  4572.8  598.29  4618.2  594.56  4643.1  591.38  4648.5  591.49  4698.3  588.22
  4852.9  583.65  4874.5  583.37  4904.8  581.78  4924.4  581.92  4929.7  581.12
  4946.6   581.1  4978.7  578.25  4984.9  576.71  4990.2  572.62  4993.4  571.84
  4994.6  571.34  5000.2  571.34  5001.4  571.84  5003.6  571.84  5014.2  576.36
  5028.3  579.18  5042.5  576.45  5056.6  577.48  5070.7  579.65  5084.9  580.44
  5158.9  581.41  5183.9  582.39    5198  583.92  5226.3  585.39  5424.3  599.78
#Mann= 5 ,-1 , 0
  4572.8     .05       0  4852.9      .1       0  4993.4     .05       0
  5001.4      .1       0  5158.9     .05       0
Bank Sta=4993.4,5001.4
XS Rating Curve= 0 ,0
Exp/Cntr=0.3,0.1

Type RM Length L Ch R = 1 ,1811    ,0,0,0
BEGIN DESCRIPTION:
LWE S WB_1 1.0
END DESCRIPTION:
XS GIS Cut Line= 4
      2374739.73      7071932.14      2373879.55      7071999.36
      2373872.34      7072116.85      2373800.06      7072392.21
#Sta/Elev= 30
  4137.2  604.54  4173.5  599.39  4288.4  589.44  4358.6  585.77  4458.4   582.5
    4634  581.36    4686  579.84    4830  578.82  4870.2  575.96  4900.2  576.64
  4917.2  575.63  4930.3  576.54  4960.4  576.85  4970.5  575.82  4988.4  569.81
  4997.8  567.89  5006.6  567.85  5007.8  567.35  5014.7  567.85  5020.7  568.05
  5030.7  570.54  5040.7  577.67  5050.7  579.93  5110.8  579.57  5116.8  580.68
    5183  582.22  5286.4  588.72  5338.1   593.6  5394.3  594.74  5402.4  594.97
#Mann= 8 ,-1 , 0
  4137.2     .05       0  4458.4     .12       0    4634     .05       0
  4917.2      .1       0  4988.4     .05       0  5006.6    .033       0
  5014.7     .05       0  5394.3      .1       0
Bank Sta=5006.6,5014.7
XS Rating Curve= 0 ,0
Exp/Cntr=0.3,0.1

Chan Stop Cuts=-1
Use User Specified Reach Order=0
Composite Channel Slope=5