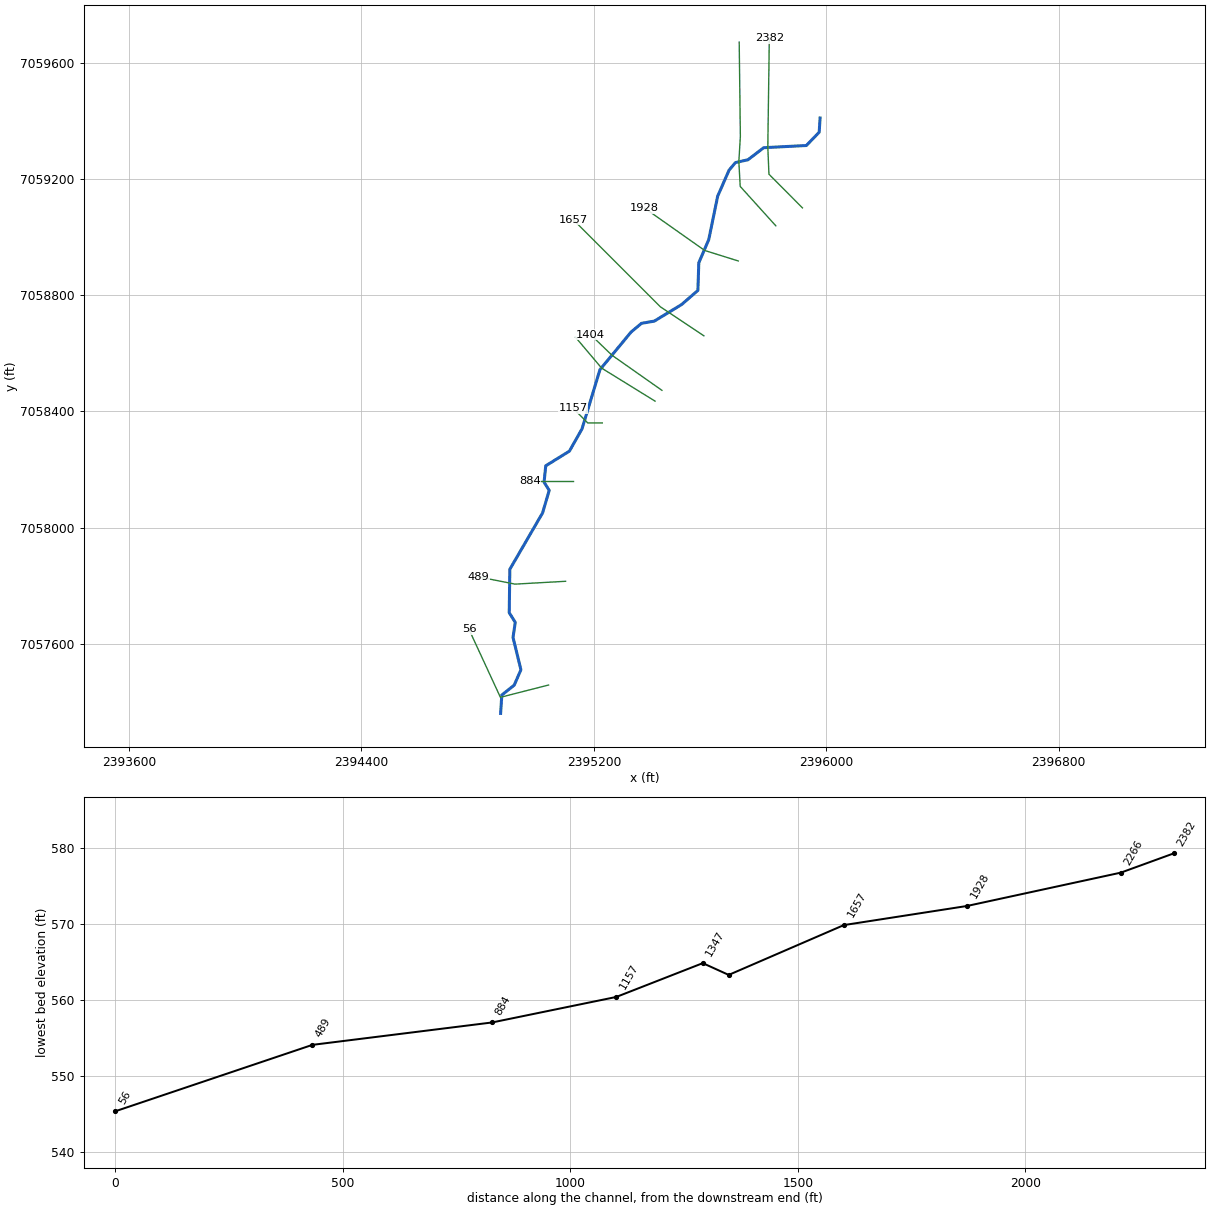
--- LWE S WC_2.prj (project) ---

Proj Title=LWE S WC_2 Base Level Engineering
Current Plan=p01
Default Exp/Contr=0.3,0.1
English Units
Geom File=g01
Flow File=f01
Plan File=p01
Y Axis Title=Elevation
X Axis Title(PF)=Main Channel Distance
X Axis Title(XS)=Station
BEGIN DESCRIPTION:
LWE S WC_2
END DESCRIPTION:
DSS Export Rating Curves= 0
DSS Export Rating Curve Sorted= 0
DSS Export Volume Flow Curves= 0
DXF OffsetX= 0
DXF OffsetY= 0
DXF ScaleX= 1
DXF ScaleY= 10

--- LWE S WC_2.p01 (plan) ---

Plan Title=Multiple Run
Short Identifier=Multiple
Geom File=g01
Flow File=f01
Subcritical Flow
K Sum by GR= 0
Std Step Tol= 0.01
Critical Tol= 0.01
Num of Std Step Trials= 20
Max Error Tol= 0.3
Flow Tol Ratio= 0.001
Split Flow NTrial= 30
Split Flow Tol= 0.02
Split Flow Ratio= 0.02
Log Output Level= 0
Friction Slope Method= 1
Unsteady Friction Slope Method= 2
Unsteady Bridges Friction Slope Method= 1
Parabolic Critical Depth
Global Vel Dist=  1 , 1 , 1
Global Log Level= 0
CheckData=True
Encroach Param= -1, 0, 0, 0
BEGIN DESCRIPTION:
Multiple Run
END DESCRIPTION:

--- LWE S WC_2.f01 (steady flow) ---

Flow Title=Multiple
Program Version=4.10
Number of Profiles= 7
Profile Names=10-year,25-year,50-year,1pct_min,100-year,1pct_plu,500-year
River Rch & RM=LWE S WC_2,Reach-1         ,2382
     287     376     446     264     527    1051     734
Boundary for River Rch & Prof#=LWE S WC_2,Reach-1         , 1
Up Type= 0
Dn Type= 3
Dn Slope=0.005
Boundary for River Rch & Prof#=LWE S WC_2,Reach-1         , 2
Up Type= 0
Dn Type= 3
Dn Slope=0.005
Boundary for River Rch & Prof#=LWE S WC_2,Reach-1         , 3
Up Type= 0
Dn Type= 3
Dn Slope=0.005
Boundary for River Rch & Prof#=LWE S WC_2,Reach-1         , 4
Up Type= 0
Dn Type= 3
Dn Slope=0.005
Boundary for River Rch & Prof#=LWE S WC_2,Reach-1         , 5
Up Type= 0
Dn Type= 3
Dn Slope=0.005
Boundary for River Rch & Prof#=LWE S WC_2,Reach-1         , 6
Up Type= 0
Dn Type= 3
Dn Slope=0.005
Boundary for River Rch & Prof#=LWE S WC_2,Reach-1         , 7
Up Type= 0
Dn Type= 3
Dn Slope=0.005
DSS Import GetInterval= 0
DSS Import GetPeak= 0
DSS Import FillOption= 0

--- LWE S WC_2.g01 (geometry) ---

Geom Title=Existing Conditions

River Reach=LWE S WC_2,Reach-1
Reach XY= 30
      2395979.00      7059410.00      2395975.88      7059360.98
      2395931.69      7059315.27      2395784.91      7059307.76
      2395730.84      7059266.28      2395687.46      7059256.50
      2395665.50      7059230.26      2395626.43      7059140.85
      2395595.62      7058991.11      2395561.42      7058911.68
      2395558.29      7058816.37      2395502.56      7058767.93
      2395408.29      7058710.64      2395364.03      7058702.99
      2395328.13      7058672.86      2395221.01      7058543.43
      2395159.37      7058339.85      2395116.00      7058262.99
      2395034.46      7058212.45      2395028.61      7058156.02
      2395046.34      7058127.90      2395023.57      7058050.33
      2394910.79      7057856.18      2394908.66      7057706.80
      2394929.50      7057673.21      2394921.68      7057621.64
      2394948.92      7057510.18      2394925.92      7057457.23
      2394883.16      7057423.16      2394879.00      7057360.00

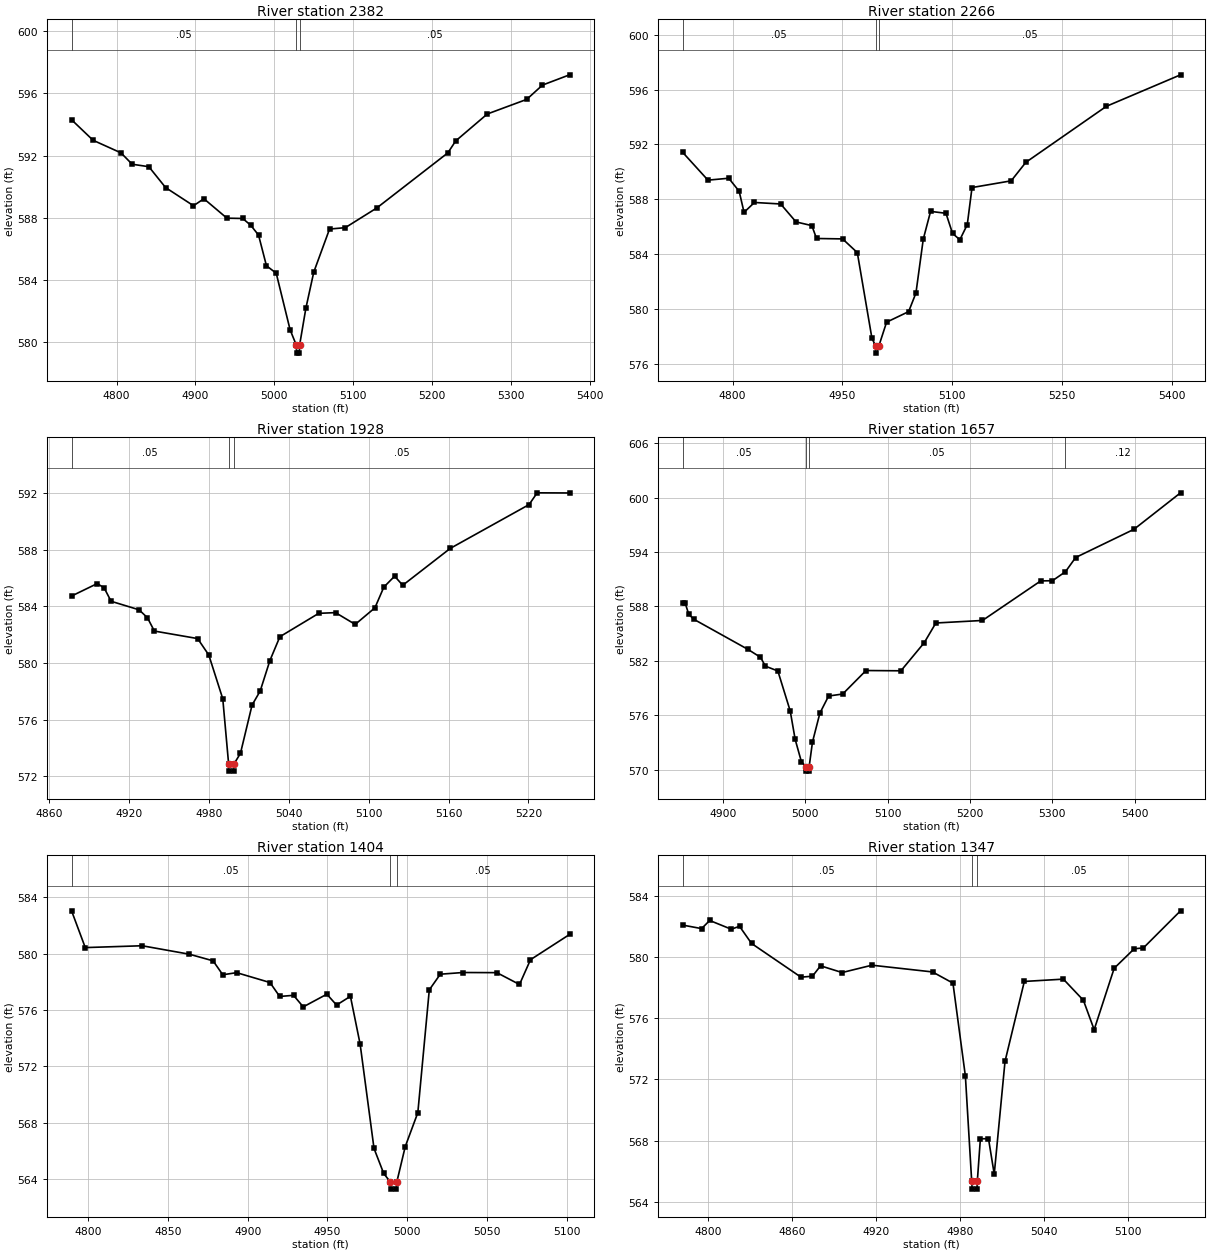
Type RM Length L Ch R = 1,2382,116,116,116
BEGIN DESCRIPTION:
LWE S WC_2 9.0
END DESCRIPTION:
XS GIS Cut Line= 4
      2395918.20      7059100.57      2395802.89      7059216.57
      2395799.02      7059309.92      2395804.18      7059684.29
#Sta/Elev= 30
  4743.0  594.30  4770.3  592.98  4805.7  592.17  4819.8  591.44  4841.0  591.28
  4862.2  589.94  4897.6  588.77  4910.8  589.22  4940.0  587.97  4960.0  587.95
  4970.1  587.52  4980.1  586.88  4990.1  584.91  5002.5  584.43  5020.1  580.79
  5028.1  579.79  5028.3  579.29  5031.8  579.29  5032.1  579.79  5040.1  582.18
  5050.1  584.50  5070.1  587.27  5090.1  587.36  5130.1  588.63  5220.1  592.17
  5230.1  592.94  5270.1  594.67  5320.1  595.61  5340.1  596.53  5374.4  597.19
#Mann=3,-1,0
  4743.0    0.05       0  5028.1   0.033       0  5032.1    0.05       0
Bank Sta=5028.1,5032.1
Exp/Cntr=0.3,0.1

Type RM Length L Ch R = 1,2266,338,338,338
BEGIN DESCRIPTION:
LWE S WC_2 8.0
END DESCRIPTION:
XS GIS Cut Line= 5
      2395826.67      7059038.65      2395703.98      7059174.44
      2395699.33      7059259.61      2395704.51      7059346.84
      2395700.53      7059671.33
#Sta/Elev= 30
  4731.7  591.43  4766.4  589.39  4794.8  589.53  4809.0  588.58  4815.7  587.04
  4829.9  587.76  4865.7  587.65  4886.7  586.34  4908.3  586.07  4914.7  585.13
  4950.3  585.10  4970.4  584.10  4990.4  577.84  4995.7  577.26  4995.9  576.76
  4999.7  577.26  5010.4  579.02  5040.5  579.79  5050.5  581.15  5060.5  585.08
  5070.5  587.11  5091.5  586.97  5100.5  585.50  5110.5  585.04  5120.6  586.14
  5127.1  588.85  5180.6  589.34  5200.6  590.69  5310.6  594.78  5411.9  597.08
#Mann=3,-1,0
  4731.7    0.05       0  4995.7   0.033       0  4999.7    0.05       0
Bank Sta=4995.7,4999.7
Exp/Cntr=0.3,0.1

Type RM Length L Ch R = 1,1928,271,271,271
BEGIN DESCRIPTION:
LWE S WC_2 7.0
END DESCRIPTION:
XS GIS Cut Line= 3
      2395697.37      7058917.68      2395581.74      7058953.86
      2395375.00      7059099.59
#Sta/Elev= 30
  4876.8  584.72  4896.1  585.60  4901.3  585.29  4906.5  584.35  4927.5  583.75
  4933.8  583.19  4939.0  582.25  4971.5  581.72  4979.9  580.56  4990.4  577.47
  4994.8  572.87  4995.0  572.37  4998.5  572.37  4998.8  572.87  5003.7  573.63
  5012.4  577.03  5018.5  578.02  5025.8  580.17  5033.3  581.85  5062.5  583.50
  5075.1  583.55  5089.9  582.72  5104.7  583.89  5111.4  585.35  5119.5  586.12
  5125.6  585.48  5161.3  588.08  5220.5  591.17  5226.6  592.00  5250.9  591.99
#Mann=3,-1,0
  4876.8    0.05       0  4994.8   0.033       0  4998.8    0.05       0
Bank Sta=4994.8,4998.8
Exp/Cntr=0.3,0.1

Type RM Length L Ch R = 1,1657,253,253,253
BEGIN DESCRIPTION:
LWE S WC_2 6.0
END DESCRIPTION:
XS GIS Cut Line= 3
      2395578.99      7058660.01      2395429.00      7058760.00
      2395129.02      7059059.98
#Sta/Elev= 30
  4851.0  588.42  4854.0  588.42  4858.5  587.15  4864.5  586.60  4930.6  583.26
  4945.6  582.40  4951.6  581.42  4966.7  580.89  4981.7  576.48  4987.7  573.35
  4995.2  570.91  5000.7  570.35  5001.0  569.85  5004.5  569.85  5004.7  570.35
  5008.7  573.05  5017.7  576.24  5028.3  578.13  5045.4  578.35  5073.7  580.94
  5116.1  580.91  5144.4  584.01  5158.5  586.18  5215.1  586.46  5285.8  590.82
  5300.0  590.84  5315.8  591.83  5328.2  593.40  5399.0  596.51  5455.5  600.53
#Mann=4,-1,0
  4851.0    0.05       0  5000.7   0.033       0  5004.7    0.05       0
  5315.8    0.12       0
Bank Sta=5000.7,5004.7
Exp/Cntr=0.3,0.1

Type RM Length L Ch R = 1,1404,57,57,57
BEGIN DESCRIPTION:
LWE S WC_2 5.0
END DESCRIPTION:
XS GIS Cut Line= 3
      2395434.35      7058472.37      2395262.04      7058593.46
      2395188.70      7058664.21
#Sta/Elev= 30
  4789.4  583.05  4798.0  580.44  4833.7  580.57  4863.3  579.97  4878.2  579.50
  4884.3  578.51  4893.0  578.66  4913.9  577.96  4920.0  576.97  4928.7  577.05
  4934.8  576.23  4949.6  577.13  4955.7  576.36  4964.4  576.98  4970.5  573.58
  4979.2  566.18  4985.3  564.40  4989.5  563.79  4989.7  563.29  4993.2  563.29
  4993.5  563.79  4998.8  566.31  5006.7  568.72  5013.9  577.44  5020.8  578.55
  5035.0  578.67  5056.3  578.66  5070.5  577.82  5077.4  579.58  5101.9  581.37
#Mann=3,-1,0
  4789.4    0.05       0  4989.5    0.05       0  4993.5    0.05       0
Bank Sta=4989.5,4993.5
Exp/Cntr=0.3,0.1

Type RM Length L Ch R = 1,1347,190,190,190
BEGIN DESCRIPTION:
Mapping XS e206da04
END DESCRIPTION:
XS GIS Cut Line= 3
      2395410.94      7058435.03      2395226.90      7058548.75
      2395136.86      7058655.24
#Sta/Elev= 30
  4781.9  582.08  4795.5  581.85  4801.3  582.38  4816.7  581.81  4822.6  582.00
  4831.2  580.88  4866.5  578.68  4874.7  578.74  4880.5  579.42  4895.9  578.98
  4917.2  579.46  4960.5  579.02  4975.1  578.29  4984.0  572.21  4988.5  565.34
  4988.8  564.84  4992.3  564.84  4992.5  565.34  4994.7  568.13  5000.5  568.13
  5004.6  565.82  5012.3  573.18  5026.1  578.40  5054.0  578.55  5068.3  577.17
  5076.0  575.25  5090.3  579.26  5104.6  580.53  5111.2  580.59  5137.7  583.01
#Mann=3,-1,0
  4781.9    0.05       0  4988.5    0.05       0  4992.5    0.05       0
Bank Sta=4988.5,4992.5
Exp/Cntr=0.3,0.1

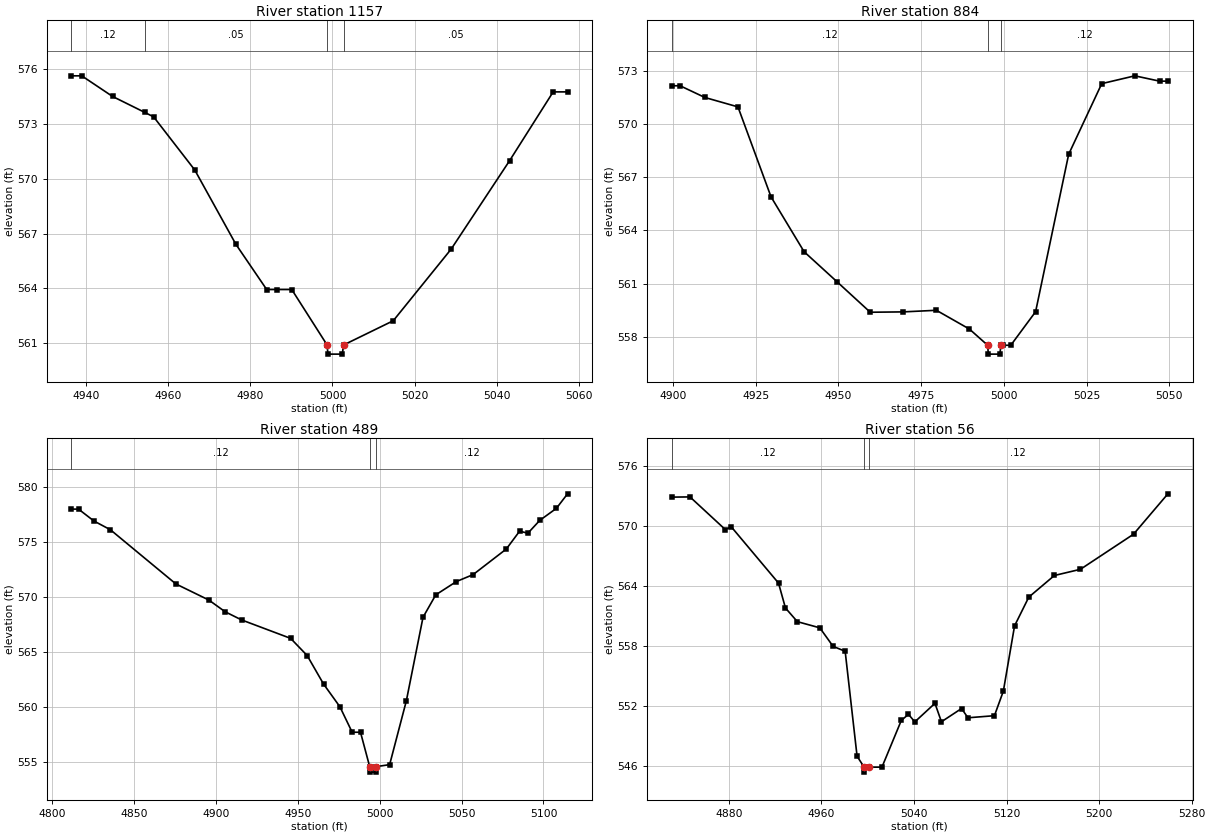
Type RM Length L Ch R = 1,1157,273,273,273
BEGIN DESCRIPTION:
LWE S WC_2 4.0
END DESCRIPTION:
XS GIS Cut Line= 3
      2395229.02      7058360.00      2395179.00      7058360.00
      2395129.02      7058409.98
#Sta/Elev= 19
  4936.5  575.64  4939.0  575.64  4946.5  574.51  4954.3  573.64  4956.5  573.39
  4966.5  570.48  4976.5  566.41  4984.0  563.93  4986.5  563.93  4990.1  563.93
  4998.7  560.89  4998.9  560.39  5002.4  560.39  5002.7  560.89  5014.8  562.22
  5028.9  566.15  5043.1  570.99  5053.7  574.76  5057.2  574.76
#Mann=4,-1,0
  4936.5    0.12       0  4954.3    0.05       0  4998.7   0.033       0
  5002.7    0.05       0
Bank Sta=4998.7,5002.7
Exp/Cntr=0.3,0.1

Type RM Length L Ch R = 1,884,395,395,395
BEGIN DESCRIPTION:
LWE S WC_2 3.0
END DESCRIPTION:
XS GIS Cut Line= 3
      2395128.97      7058160.00      2395029.00      7058160.00
      2394978.97      7058160.00
#Sta/Elev= 23
  4899.6  572.15  4902.1  572.15  4909.6  571.49  4919.6  570.96  4929.6  565.89
  4939.6  562.80  4949.6  561.10  4959.6  559.39  4969.6  559.41  4979.6  559.50
  4989.6  558.44  4995.1  557.53  4995.3  557.03  4998.8  557.03  4999.1  557.53
  4999.6  557.53  5002.1  557.53  5009.6  559.42  5019.6  568.29  5029.6  572.27
  5039.6  572.71  5047.1  572.41  5049.6  572.41
#Mann=3,-1,0
  4899.6    0.12       0  4995.1    0.07       0  4999.1    0.12       0
Bank Sta=4995.1,4999.1
Exp/Cntr=0.3,0.1

Type RM Length L Ch R = 1,489,433,433,433
BEGIN DESCRIPTION:
LWE S WC_2 2.0
END DESCRIPTION:
XS GIS Cut Line= 3
      2395102.72      7057814.80      2394928.94      7057805.03
      2394802.36      7057830.10
#Sta/Elev= 30
  4811.6  578.01  4815.9  578.01  4825.3  576.93  4835.4  576.13  4875.4  571.20
  4895.5  569.74  4905.5  568.67  4915.5  567.93  4945.5  566.25  4955.6  564.69
  4965.6  562.10  4975.6  560.03  4983.1  557.71  4988.2  557.71  4993.8  554.58
  4994.0  554.08  4997.5  554.08  4997.8  554.58  5006.0  554.76  5016.2  560.56
  5026.4  568.17  5034.2  570.21  5046.8  571.42  5057.0  572.05  5077.3  574.38
  5085.4  576.00  5090.5  575.82  5097.7  576.98  5107.9  578.08  5114.7  579.40
#Mann=3,-1,0
  4811.6    0.12       0  4993.8    0.07       0  4997.8    0.12       0
Bank Sta=4993.8,4997.8
Exp/Cntr=0.3,0.1

Type RM Length L Ch R = 1,56,0,0,0
BEGIN DESCRIPTION:
LWE S WC_2 1.0
END DESCRIPTION:
XS GIS Cut Line= 3
      2395044.10      7057457.64      2394878.30      7057415.29
      2394770.16      7057649.07
#Sta/Elev= 30
  4830.7  572.92  4846.4  572.94  4876.9  569.67  4882.1  569.94  4922.9  564.30
  4928.9  561.80  4939.2  560.43  4958.6  559.81  4970.1  557.95  4980.5  557.46
  4990.8  546.93  4996.9  545.84  4997.1  545.34  5000.9  545.84  5012.3  545.84
  5029.0  550.52  5035.2  551.14  5040.7  550.38  5058.1  552.24  5063.7  550.39
  5081.1  551.72  5086.6  550.79  5109.5  551.00  5117.2  553.46  5126.9  560.01
  5139.2  562.89  5161.3  565.06  5183.8  565.68  5229.7  569.20  5259.4  573.25
#Mann=3,-1,0
  4830.7    0.12       0  4996.9    0.07       0  5000.9    0.12       0
Bank Sta=4996.9,5000.9
Exp/Cntr=0.3,0.1

Chan Stop Cuts=-1