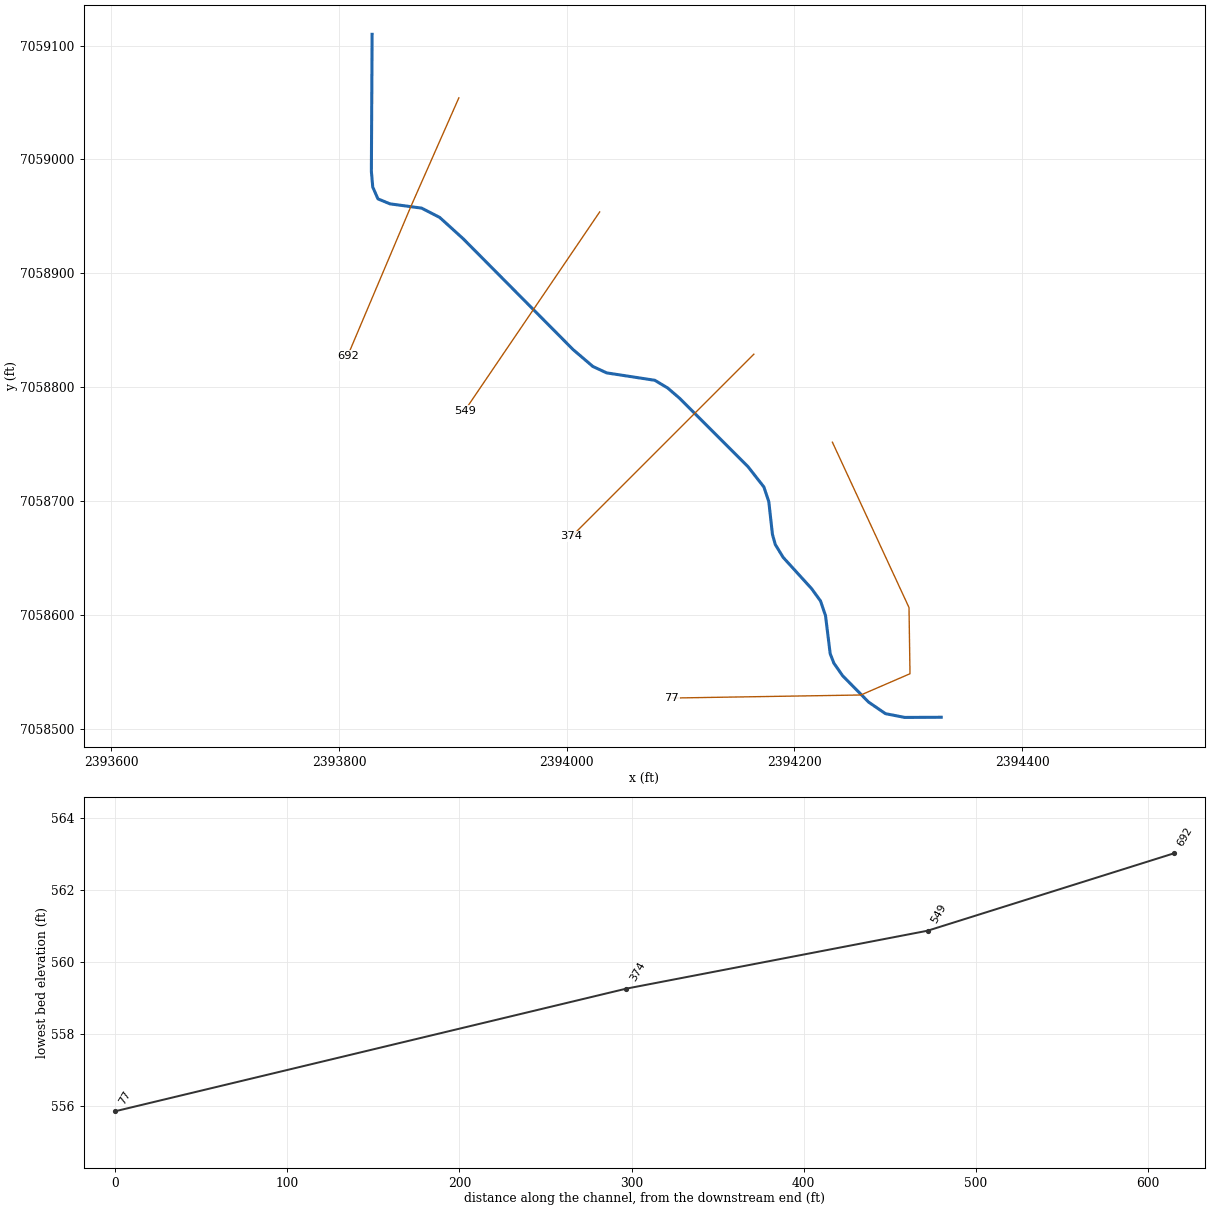
--- LWE S WC_3.prj (project) ---

Proj Title=LWE S WC_3 Base Level Engineering
Current Plan=p01
Default Exp/Contr=0.3,0.1
English Units
Geom File=g01
Flow File=f01
Plan File=p01
BEGIN DESCRIPTION:
LWE S WC_3
END DESCRIPTION:

--- LWE S WC_3.p01 (plan) ---

Plan Title=Multiple Run
Short Identifier=Multiple
Geom File=g01
Flow File=f01
Subcritical Flow
K Sum by GR= 0
Std Step Tol= 0.01
Critical Tol= 0.01
Num of Std Step Trials= 20
Max Error Tol= 0.3
Flow Tol Ratio= 0.001
Split Flow NTrial= 30
Split Flow Tol= 0.02
Split Flow Ratio= 0.02
Log Output Level= 0
Friction Slope Method= 1
Unsteady Friction Slope Method= 2
Unsteady Bridges Friction Slope Method= 1
Parabolic Critical Depth
Global Vel Dist=  1 , 1 , 1
Global Log Level= 0
CheckData=True
Encroach Param= -1, 0, 0, 0
BEGIN DESCRIPTION:
Multiple Run
END DESCRIPTION:

--- LWE S WC_3.f01 (steady flow) ---

Flow Title=Multiple
Number of Profiles=7
Profile Names=10-year,25-year,50-year,1pct_min,100-year,1pct_plu,500-year
River Rch & RM= LWE S WC_3,Reach-1,692
     192     245     287     168     335     668     454
Boundary for River Rch & Prof#=LWE S WC_3,Reach-1,1
Up Type=0
Dn Type=3
Dn Slope=0.005
Boundary for River Rch & Prof#=LWE S WC_3,Reach-1,2
Up Type=0
Dn Type=3
Dn Slope=0.005
Boundary for River Rch & Prof#=LWE S WC_3,Reach-1,3
Up Type=0
Dn Type=3
Dn Slope=0.005
Boundary for River Rch & Prof#=LWE S WC_3,Reach-1,4
Up Type=0
Dn Type=3
Dn Slope=0.005
Boundary for River Rch & Prof#=LWE S WC_3,Reach-1,5
Up Type=0
Dn Type=3
Dn Slope=0.005
Boundary for River Rch & Prof#=LWE S WC_3,Reach-1,6
Up Type=0
Dn Type=3
Dn Slope=0.005
Boundary for River Rch & Prof#=LWE S WC_3,Reach-1,7
Up Type=0
Dn Type=3
Dn Slope=0.005

--- LWE S WC_3.g01 (geometry) ---

Geom Title=Existing Conditions

River Reach=LWE S WC_3,Reach-1
Reach XY= 30
      2393829.00      7059110.00      2393828.35      7058989.46
      2393829.57      7058975.76      2393834.13      7058965.40
      2393844.73      7058961.03      2393872.48      7058957.28
      2393888.38      7058949.10      2393909.05      7058930.34
      2394005.54      7058833.02      2394022.95      7058818.16
      2394035.05      7058812.54      2394077.36      7058806.03
      2394088.70      7058799.23      2394099.13      7058790.23
      2394159.23      7058730.13      2394173.17      7058712.31
      2394177.50      7058699.38      2394180.70      7058670.70
      2394183.19      7058661.74      2394190.10      7058650.45
      2394215.02      7058623.06      2394222.91      7058612.18
      2394227.32      7058599.28      2394231.42      7058565.89
      2394234.68      7058557.48      2394242.37      7058546.45
      2394265.22      7058523.27      2394280.03      7058513.14
      2394296.95      7058509.85      2394329.00      7058510.00

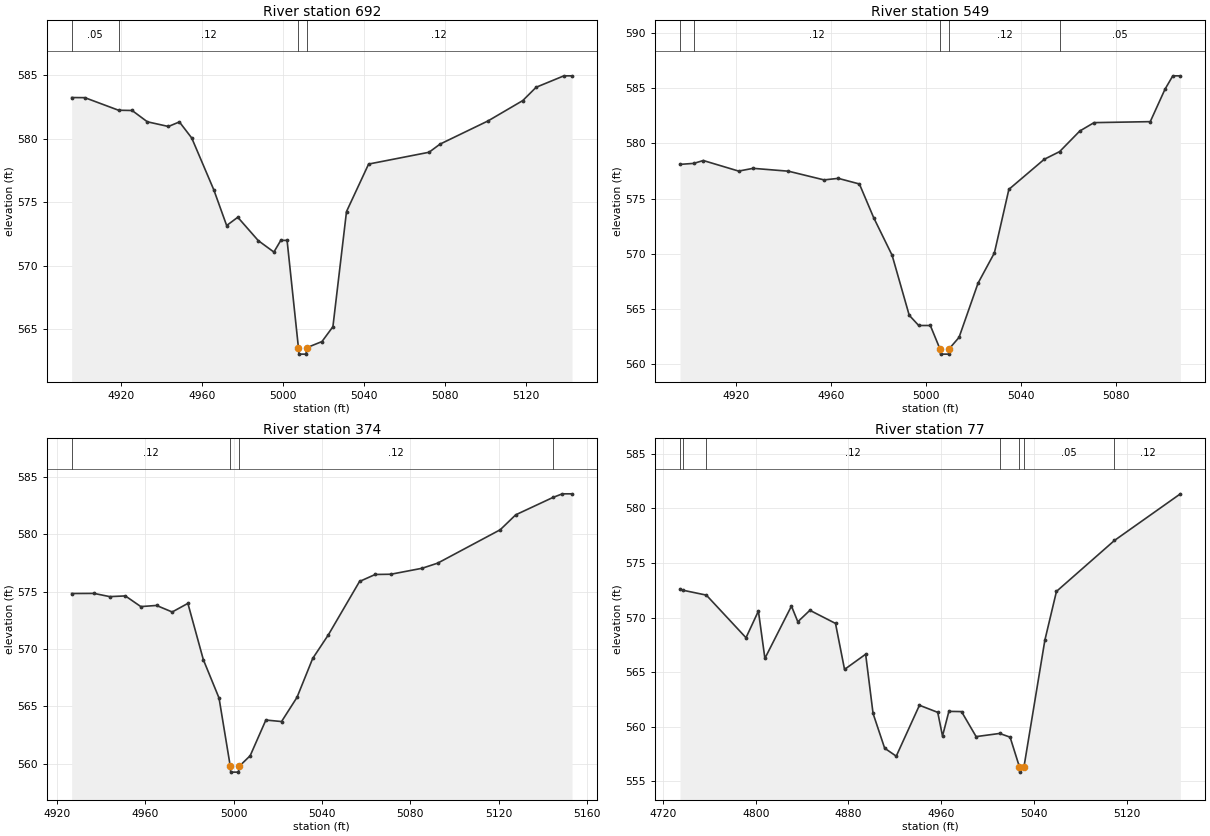
Type RM Length L Ch R = 1,692,143,143,143
BEGIN DESCRIPTION:
LWE S WC_3 2.0
END DESCRIPTION:
XS GIS Cut Line= 3
      2393905.21      7059054.16      2393863.15      7058958.94
      2393807.56      7058827.62
#Sta/Elev= 30
  4895.9  583.23  4902.4  583.22  4919.0  582.23  4925.7  582.21  4933.2  581.32
  4943.6  580.95  4949.0  581.31  4955.1  580.04  4966.0  575.95  4972.3  573.15
  4977.8  573.80  4987.9  571.96  4995.6  571.06  4999.0  571.98  5002.1  571.98
  5007.7  563.52  5008.0  563.02  5011.5  563.02  5011.7  563.52  5019.3  564.01
  5024.7  565.18  5031.4  574.25  5042.3  577.99  5072.1  578.92  5077.5  579.56
  5101.2  581.39  5118.3  582.99  5124.9  584.04  5138.6  584.94  5142.6  584.94
#Mann=4,-1,0
  4895.9    0.05       0  4919.0    0.12       0  5007.7    0.07       0
  5011.7    0.12       0
Bank Sta=5007.7,5011.7
Exp/Cntr=0.3,0.1

Type RM Length L Ch R = 1,549,175,175,175
BEGIN DESCRIPTION:
Mapping XS 525c5658
END DESCRIPTION:
XS GIS Cut Line= 3
      2394028.92      7058953.93      2393970.83      7058868.38
      2393910.44      7058779.46
#Sta/Elev= 30
  4896.3  578.10  4902.1  578.19  4906.1  578.45  4921.0  577.49  4927.1  577.74
  4942.0  577.48  4957.0  576.69  4963.0  576.83  4971.9  576.32  4977.9  573.27
  4985.7  569.84  4992.9  564.40  4996.9  563.47  5001.8  563.47  5005.8  561.37
  5006.1  560.87  5009.6  560.87  5009.8  561.37  5013.9  562.39  5021.9  567.31
  5028.8  570.06  5034.9  575.83  5049.8  578.56  5056.3  579.26  5064.8  581.13
  5070.8  581.89  5094.5  581.98  5100.7  584.92  5104.0  586.14  5107.2  586.14
#Mann=5,-1,0
  4896.3    0.05       0  4902.1    0.12       0  5005.8    0.07       0
  5009.8    0.12       0  5056.3    0.05       0
Bank Sta=5005.8,5009.8
Exp/Cntr=0.3,0.1

Type RM Length L Ch R = 1,374,297,297,297
BEGIN DESCRIPTION:
Mapping XS ddae030c
END DESCRIPTION:
XS GIS Cut Line= 2
      2394164.36      7058828.96      2394004.20      7058668.80
#Sta/Elev= 30
  4926.7  574.83  4936.8  574.84  4943.9  574.56  4951.0  574.62  4958.0  573.69
  4965.1  573.79  4972.2  573.22  4979.3  573.97  4986.3  569.06  4993.4  565.72
  4998.5  559.76  4998.7  559.26  5002.2  559.26  5002.5  559.76  5007.5  560.69
  5014.6  563.80  5021.7  563.67  5028.7  565.78  5035.8  569.17  5042.9  571.23
  5057.0  575.88  5064.1  576.49  5071.2  576.51  5085.3  577.03  5092.4  577.48
  5120.7  580.39  5127.7  581.69  5144.5  583.20  5148.8  583.52  5153.2  583.52
#Mann=4,-1,0
  4926.7    0.12       0  4998.5    0.07       0  5002.5    0.12       0
  5144.5    0.05       0
Bank Sta=4998.5,5002.5
Exp/Cntr=0.3,0.1

Type RM Length L Ch R = 1,77,0,0,0
BEGIN DESCRIPTION:
LWE S WC_3 1.0
END DESCRIPTION:
XS GIS Cut Line= 5
      2394233.37      7058751.64      2394300.67      7058606.39
      2394301.54      7058548.23      2394258.36      7058529.55
      2394092.08      7058526.88
#Sta/Elev= 30
  4734.7  572.58  4737.1  572.50  4757.4  572.05  4791.6  568.15  4802.3  570.59
  4807.9  566.26  4830.8  571.05  4836.3  569.61  4846.7  570.66  4868.8  569.46
  4876.6  565.25  4894.8  566.64  4901.2  561.22  4911.2  558.04  4921.2  557.31
  4941.2  561.97  4957.0  561.32  4961.1  559.15  4966.6  561.41  4977.5  561.39
  4990.1  559.10  5010.4  559.39  5019.4  559.05  5027.4  556.35  5027.6  555.85
  5031.4  556.35  5049.4  567.93  5059.4  572.39  5109.4  577.05  5166.3  581.32
#Mann=7,-1,0
  4734.7    0.12       0  4737.1    0.05       0  4757.4    0.12       0
  5010.4    0.05       0  5027.4    0.07       0  5031.4    0.05       0
  5109.4    0.12       0
Bank Sta=5027.4,5031.4
Exp/Cntr=0.3,0.1

Chan Stop Cuts=-1