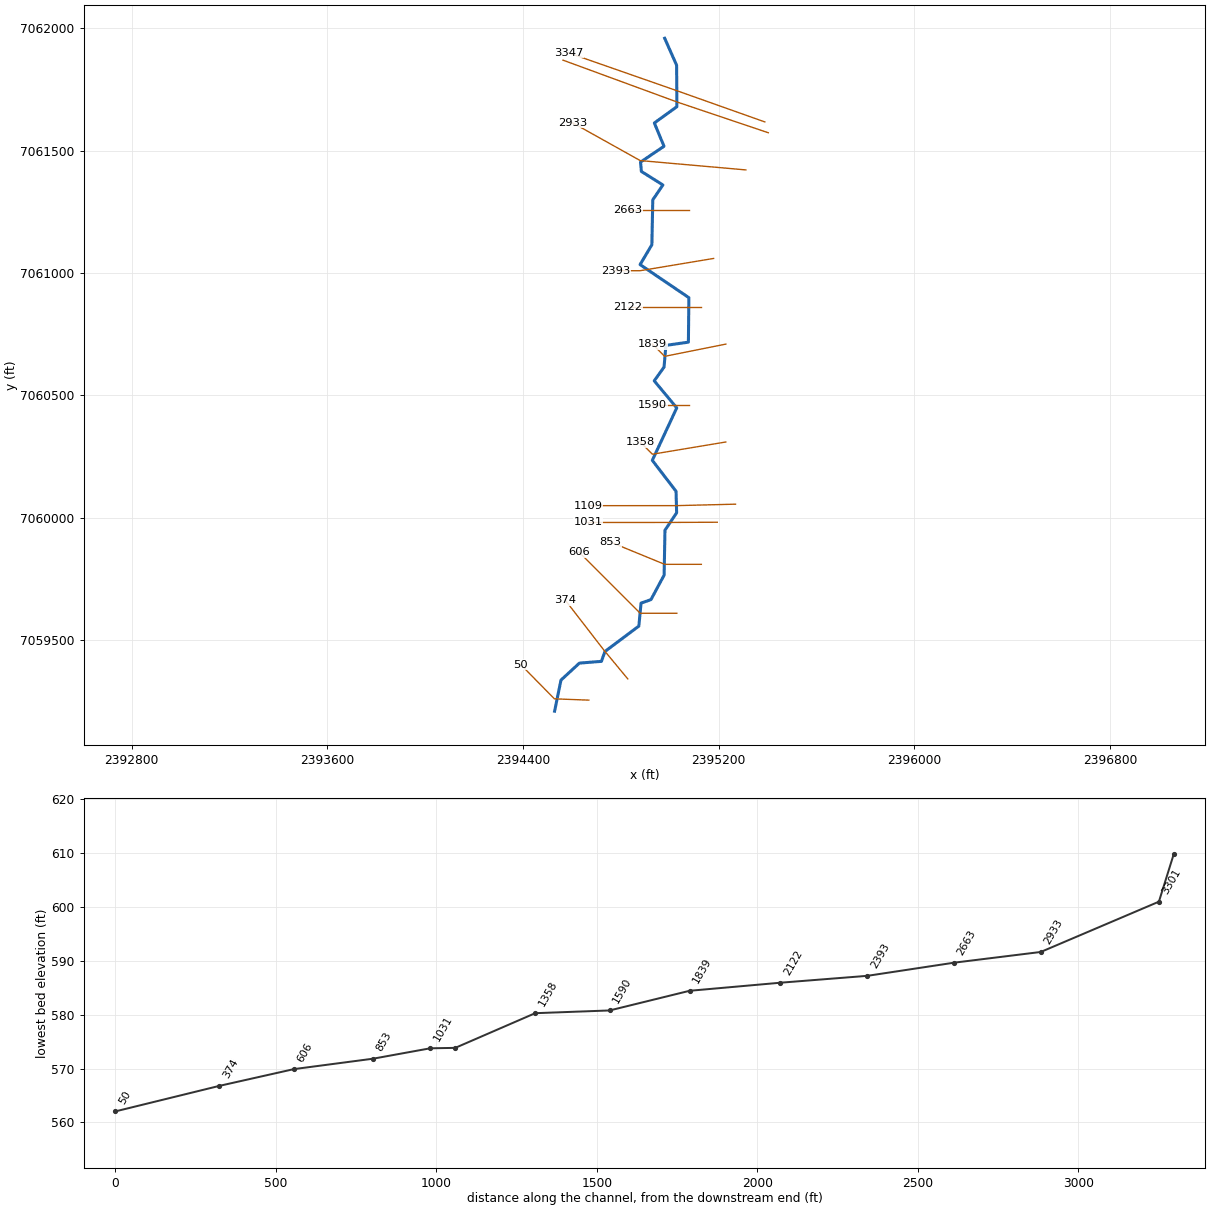
--- LWE S WC_4.prj (project) ---

Proj Title=LWE S WC_4 Base Level Engineering
Current Plan=p01
Default Exp/Contr=0.3,0.1
English Units
Geom File=g01
Flow File=f01
Plan File=p01
Y Axis Title=Elevation
X Axis Title(PF)=Main Channel Distance
X Axis Title(XS)=Station
BEGIN DESCRIPTION:
LWE S WC_4
END DESCRIPTION:
DSS Export Rating Curves= 0
DSS Export Rating Curve Sorted= 0
DSS Export Volume Flow Curves= 0
DXF OffsetX= 0
DXF OffsetY= 0
DXF ScaleX= 1
DXF ScaleY= 10

--- LWE S WC_4.p01 (plan) ---

Plan Title=Multiple Run
Short Identifier=Multiple
Geom File=g01
Flow File=f01
Subcritical Flow
K Sum by GR= 0
Std Step Tol= 0.01
Critical Tol= 0.01
Num of Std Step Trials= 20
Max Error Tol= 0.3
Flow Tol Ratio= 0.001
Split Flow NTrial= 30
Split Flow Tol= 0.02
Split Flow Ratio= 0.02
Log Output Level= 0
Friction Slope Method= 1
Unsteady Friction Slope Method= 2
Unsteady Bridges Friction Slope Method= 1
Parabolic Critical Depth
Global Vel Dist=  1 , 1 , 1
Global Log Level= 0
CheckData=True
Encroach Param= -1, 0, 0, 0
BEGIN DESCRIPTION:
Multiple Run
END DESCRIPTION:

--- LWE S WC_4.f01 (steady flow) ---

Flow Title=Multiple
Program Version=4.10
Number of Profiles= 7
Profile Names=10-year,25-year,50-year,1pct_min,100-year,1pct_plu,500-year
River Rch & RM=LWE S WC_4,Reach-1         ,3347
     316     415     493     292     582    1162     812
Boundary for River Rch & Prof#=LWE S WC_4,Reach-1         , 1
Up Type= 0
Dn Type= 3
Dn Slope=0.005
Boundary for River Rch & Prof#=LWE S WC_4,Reach-1         , 2
Up Type= 0
Dn Type= 3
Dn Slope=0.005
Boundary for River Rch & Prof#=LWE S WC_4,Reach-1         , 3
Up Type= 0
Dn Type= 3
Dn Slope=0.005
Boundary for River Rch & Prof#=LWE S WC_4,Reach-1         , 4
Up Type= 0
Dn Type= 3
Dn Slope=0.005
Boundary for River Rch & Prof#=LWE S WC_4,Reach-1         , 5
Up Type= 0
Dn Type= 3
Dn Slope=0.005
Boundary for River Rch & Prof#=LWE S WC_4,Reach-1         , 6
Up Type= 0
Dn Type= 3
Dn Slope=0.005
Boundary for River Rch & Prof#=LWE S WC_4,Reach-1         , 7
Up Type= 0
Dn Type= 3
Dn Slope=0.005
DSS Import GetInterval= 0
DSS Import GetPeak= 0
DSS Import FillOption= 0

--- LWE S WC_4.g01 (geometry) ---

Geom Title=Existing Conditions
Program Version=4.10

River Reach=LWE S WC_4      ,Reach-1
Reach XY= 30
        2394979.        7061960.      2395027.88      7061849.54
      2395028.93      7061680.19      2394936.77      7061613.62
       2394976.3      7061518.51      2394880.38      7061453.74
       2394883.8      7061415.65      2394971.74       7061360.3
      2394930.39      7061299.57       2394926.7       7061115.9
      2394878.46      7061034.87      2395078.02      7060899.72
        2395076.        7060718.      2394984.18      7060704.86
       2394976.4      7060615.99      2394936.33      7060559.91
      2395028.39      7060449.38       2394928.5      7060234.97
      2395025.53       7060108.5       2395027.9      7060020.55
      2394980.22       7059949.5      2394976.77       7059765.9
      2394922.98      7059665.79       2394882.5      7059651.52
      2394873.46      7059557.62       2394734.8      7059453.95
      2394720.52       7059413.5      2394630.55      7059406.37
      2394555.16      7059336.93        2394529.        7059210.

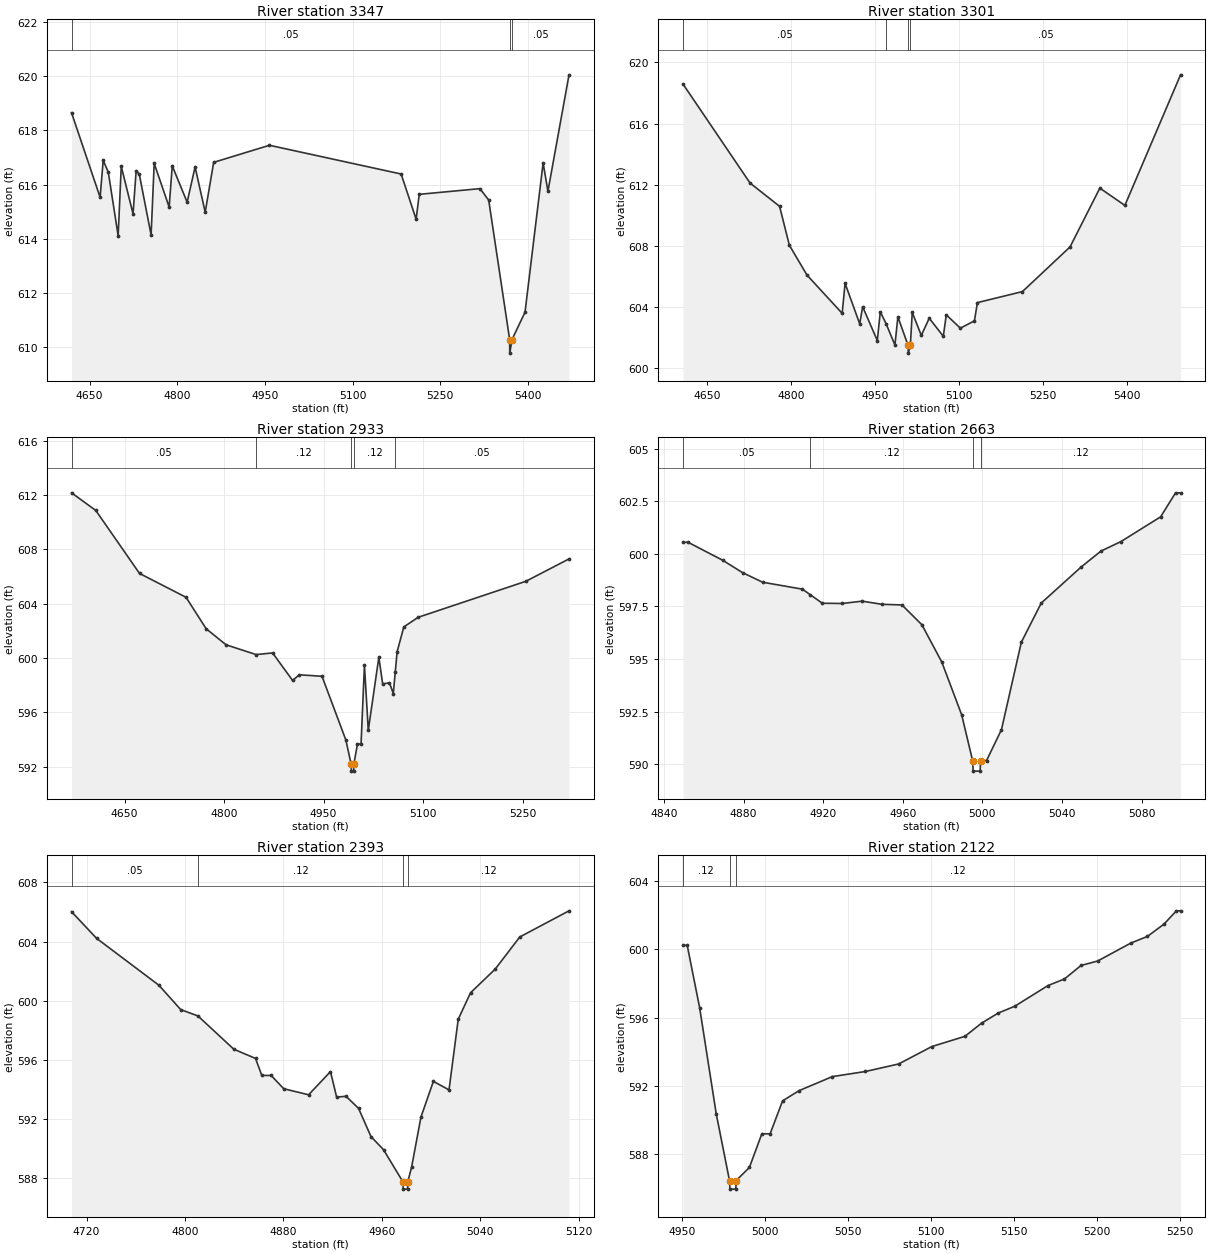
Type RM Length L Ch R = 1 ,3347    ,46,46,46
BEGIN DESCRIPTION:
Mapping XS c7b257d4
END DESCRIPTION:
XS GIS Cut Line= 3
      2395388.31      7061618.02      2395025.02      7061746.93
      2394584.95      7061900.56
#Sta/Elev= 30
    4619  618.65  4667.9  615.53  4673.2  616.89  4681.9  616.46  4698.8  614.11
  4704.1  616.67  4724.3  614.92  4729.6  616.51    4735  616.38  4755.2  614.14
  4760.5  616.78  4786.1  615.17  4791.4  616.69  4816.9  615.35  4830.5  616.65
  4847.8  614.98  4862.3  616.82  4957.8  617.45  5183.2  616.39  5208.9  614.72
  5214.2  615.64    5318  615.85  5333.1  615.43    5369  610.28  5369.2  609.78
    5373  610.28  5395.3  611.29  5426.3   616.8  5434.5  615.75  5470.6  620.05
#Mann= 3 ,-1 , 0
    4619     .05       0    5369    .033       0    5373     .05       0
Bank Sta=5369,5373
XS Rating Curve= 0 ,0
Exp/Cntr=0.3,0.1

Type RM Length L Ch R = 1 ,3301    ,368,368,368
BEGIN DESCRIPTION:
LWE S WC_4 12.0
END DESCRIPTION:
XS GIS Cut Line= 3
      2395402.65      7061573.74      2395029.65      7061699.41
      2394563.42      7061870.39
#Sta/Elev= 30
  4606.4  618.57  4726.3  612.11  4779.1  610.59  4796.6  608.05  4828.1   606.1
  4891.1   603.6  4896.3  605.56  4922.5  602.91  4927.8  604.03    4954  601.82
  4959.3   603.7  4969.6  602.93  4985.5  601.53  4990.8  603.37  5009.1   601.5
  5009.4     601  5013.1   601.5  5016.5  603.66  5032.7  602.16  5046.9  603.28
  5072.1   602.1  5077.4   603.5  5102.6  602.63  5127.8  603.11  5133.1   604.3
  5213.7  605.02  5298.9  607.94  5352.2  611.78    5397  610.65  5496.6  619.18
#Mann= 4 ,-1 , 0
  4606.4     .05       0  4969.6     .12       0  5009.1     .07       0
  5013.1     .05       0
Bank Sta=5009.1,5013.1
XS Rating Curve= 0 ,0
Exp/Cntr=0.3,0.1

Type RM Length L Ch R = 1 ,2933    ,270,270,270
BEGIN DESCRIPTION:
LWE S WC_4 11.0
END DESCRIPTION:
XS GIS Cut Line= 3
      2395311.06      7061421.84        2394879.        7061460.
      2394602.69      7061614.26
#Sta/Elev= 30
  4569.9  612.17  4606.5  610.87  4672.4  606.23  4742.6  604.47  4772.8  602.16
  4802.9  600.97  4848.2  600.25  4873.1  600.37  4903.3  598.34  4913.3  598.76
  4947.6  598.65  4983.6  593.95  4991.6  592.16  4991.9  591.66  4995.4  591.66
  4995.6  592.16  5001.1  593.66  5006.5  593.66  5011.6  599.46  5017.4  594.67
  5033.3  600.05  5039.1  598.09  5049.3  598.17  5055.1  597.38  5058.1  598.97
  5060.9  600.46    5071  602.29  5092.8     603    5255  605.65  5320.1   607.3
#Mann= 5 ,-1 , 0
  4569.9     .05       0  4848.2     .12       0  4991.6     .07       0
  4995.6     .12       0  5058.1     .05       0
Bank Sta=4991.6,4995.6
XS Rating Curve= 0 ,0
Exp/Cntr=0.3,0.1

Type RM Length L Ch R = 1 ,2663    ,270,270,270
BEGIN DESCRIPTION:
LWE S WC_4 10.0
END DESCRIPTION:
XS GIS Cut Line= 3
      2395079.03        7061260.        2394929.        7061260.
      2394829.03        7061260.
#Sta/Elev= 29
  4849.6  600.55  4852.1  600.55  4869.6  599.69  4879.6   599.1  4889.6  598.65
  4909.6  598.32  4913.6  598.05  4919.6  597.65  4929.6  597.64  4939.6  597.75
  4949.6   597.6  4959.6  597.57  4969.6  596.63  4979.6  594.86  4989.6  592.35
  4995.1  590.17  4995.4  589.67  4998.9  589.67  4999.1  590.17  5002.1  590.17
  5009.6  591.64  5019.6   595.8  5029.6  597.66  5049.6  599.37  5059.6  600.13
  5069.6  600.58  5089.6  601.76  5097.1   602.9  5099.6   602.9
#Mann= 4 ,-1 , 0
  4849.6     .05       0  4913.6     .12       0  4995.1     .07       0
  4999.1     .12       0
Bank Sta=4995.1,4999.1
XS Rating Curve= 0 ,0
Exp/Cntr=0.3,0.1

Type RM Length L Ch R = 1 ,2393    ,271,271,271
BEGIN DESCRIPTION:
LWE S WC_4 9.0
END DESCRIPTION:
XS GIS Cut Line= 3
      2395179.01        7061060.        2394879.        7061010.
      2394778.95        7061010.
#Sta/Elev= 30
  4707.8  606.02  4728.1  604.22  4778.8  601.04  4796.5  599.39  4810.5  598.96
  4839.6  596.71  4857.3  596.08  4862.4  594.93    4870  594.93  4880.2  594.03
  4900.4  593.62  4918.2  595.19  4923.2  593.46  4930.8  593.52    4941   592.7
  4951.1  590.79  4961.3   589.9    4977  587.73  4977.3  587.23  4980.8  587.23
    4981  587.73  4984.1  588.72  4991.7  592.11  5001.8  594.53  5014.5  593.95
    5022  598.74    5032  600.53    5052  602.13    5072  604.31    5112  606.08
#Mann= 4 ,-1 , 0
  4707.8     .05       0  4810.5     .12       0    4977     .07       0
    4981     .12       0
Bank Sta=4977,4981
XS Rating Curve= 0 ,0
Exp/Cntr=0.3,0.1

Type RM Length L Ch R = 1 ,2122    ,283,283,283
BEGIN DESCRIPTION:
LWE S WC_4 8.0
END DESCRIPTION:
XS GIS Cut Line= 3
      2395129.02        7060860.        2395079.        7060860.
      2394829.02        7060860.
#Sta/Elev= 30
  4950.4  600.23  4952.9  600.23  4960.4  596.57  4970.4  590.36  4978.4  586.45
  4978.7  585.95  4982.2  585.95  4982.4  586.45  4990.4  587.22  4997.9  589.19
  5002.9  589.19  5010.4  591.12  5020.4  591.72  5040.4  592.54  5060.4  592.84
  5080.4  593.28  5100.4   594.3  5120.4   594.9  5130.4  595.67  5140.4  596.26
  5150.4  596.66  5170.4  597.87  5180.4  598.26  5190.4  599.05  5200.4  599.31
  5220.4  600.36  5230.4  600.75  5240.4  601.47  5247.9  602.25  5250.4  602.25
#Mann= 3 ,-1 , 0
  4950.4     .12       0  4978.4     .07       0  4982.4     .12       0
Bank Sta=4978.4,4982.4
XS Rating Curve= 0 ,0
Exp/Cntr=0.3,0.1

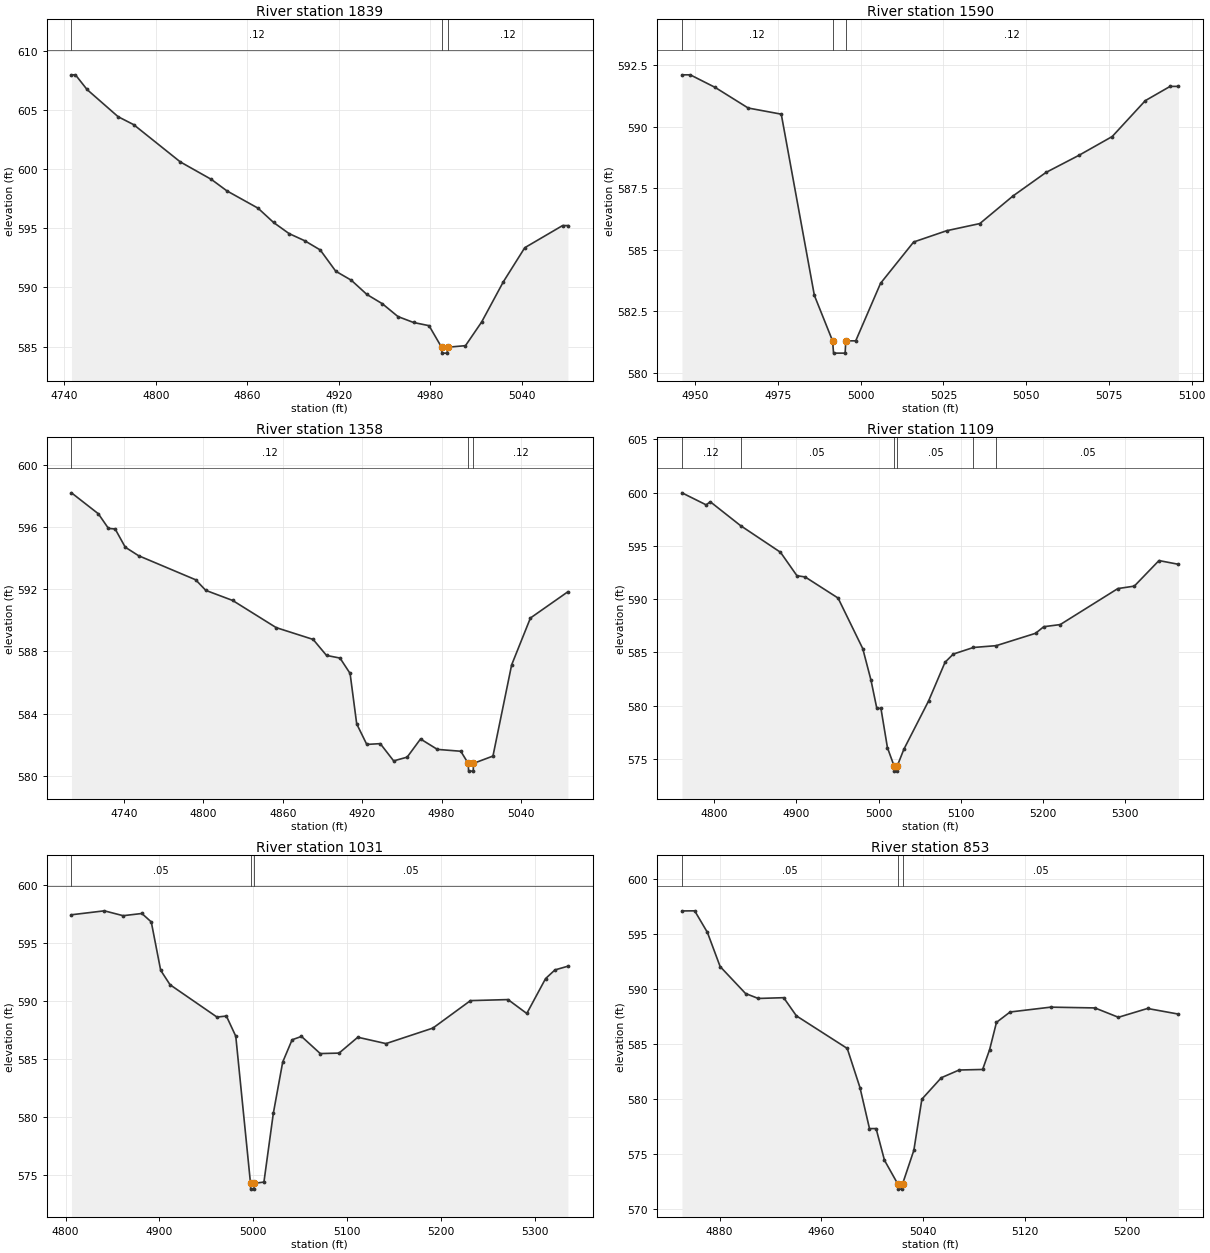
Type RM Length L Ch R = 1 ,1839    ,249,249,249
BEGIN DESCRIPTION:
LWE S WC_4 7.0
END DESCRIPTION:
XS GIS Cut Line= 3
      2395229.03      7060710.01        2394979.        7060660.
        2394929.        7060710.
#Sta/Elev= 30
  4744.7  607.97  4747.3  607.97  4754.9  606.73  4775.3  604.43  4785.5  603.76
  4816.1  600.61  4836.5  599.13  4846.7  598.16  4867.1   596.7  4877.3  595.49
  4887.5  594.55  4897.7  593.95  4907.9  593.17  4918.1  591.37  4928.3  590.61
  4938.5  589.41  4948.7  588.62  4958.9  587.54  4969.1  587.04  4979.3  586.77
  4987.5  584.95  4987.7  584.45  4991.2  584.45  4991.5  584.95  5003.2  585.08
  5013.8  587.08    5028  590.47  5042.1  593.36  5066.9  595.23  5070.4  595.23
#Mann= 3 ,-1 , 0
  4744.7     .12       0  4987.5     .07       0  4991.5     .12       0
Bank Sta=4987.5,4991.5
XS Rating Curve= 0 ,0
Exp/Cntr=0.3,0.1

Type RM Length L Ch R = 1 ,1590    ,232,232,232
BEGIN DESCRIPTION:
LWE S WC_4 6.0
END DESCRIPTION:
XS GIS Cut Line= 3
      2395079.03        7060460.        2395029.        7060460.
      2394929.03        7060460.
#Sta/Elev= 22
    4946  592.12  4948.5  592.12    4956  591.61    4966  590.77    4976  590.52
    4986  583.15  4991.5   581.3  4991.8   580.8  4995.3   580.8  4995.5   581.3
  4998.5   581.3    5006  583.64    5016  585.32    5026  585.78    5036  586.07
    5046  587.19    5056  588.15    5066  588.85    5076  589.61    5086  591.07
  5093.5  591.65    5096  591.65
#Mann= 3 ,-1 , 0
    4946     .12       0  4991.5     .07       0  4995.5     .12       0
Bank Sta=4991.5,4995.5
XS Rating Curve= 0 ,0
Exp/Cntr=0.3,0.1

Type RM Length L Ch R = 1 ,1358    ,249,249,249
BEGIN DESCRIPTION:
LWE S WC_4 5.0
END DESCRIPTION:
XS GIS Cut Line= 3
      2395229.01        7060310.        2394929.        7060260.
      2394878.97      7060310.03
#Sta/Elev= 30
  4700.5  598.21  4720.8  596.86  4728.4  595.92  4733.5  595.88  4741.1  594.71
  4751.2  594.16  4794.3  592.61  4801.9  591.93  4822.2  591.28  4855.1  589.53
    4883  588.77  4893.1  587.74  4903.3  587.57  4910.9  586.58  4915.9  583.33
  4923.5  582.01  4933.7  582.06  4943.8  580.95    4954  581.19  4964.1  582.36
  4976.8  581.69  4994.5  581.57  5000.1  580.79  5000.4  580.29  5003.9  580.29
  5004.1  580.79  5018.8  581.26  5032.9  587.13  5047.1  590.15  5075.4  591.84
#Mann= 3 ,-1 , 0
  4700.5     .12       0  5000.1     .07       0  5004.1     .12       0
Bank Sta=5000.1,5004.1
XS Rating Curve= 0 ,0
Exp/Cntr=0.3,0.1

Type RM Length L Ch R = 1 ,1109    ,78,78,78
BEGIN DESCRIPTION:
LWE S WC_4 4.0
END DESCRIPTION:
XS GIS Cut Line= 3
      2395268.62      7060055.84      2395029.79      7060049.96
      2394665.39      7060049.76
#Sta/Elev= 30
  4761.1  599.98  4790.5  598.85  4795.5  599.14  4832.3   596.9  4880.8   594.4
  4900.8   592.2  4910.8  592.08  4950.8   590.1  4980.8  585.35  4990.8  582.39
  4997.9  579.74  5002.9  579.74  5010.8  576.05  5018.8  574.35    5019  573.85
  5022.5  573.85  5022.8  574.35  5030.8  575.91  5060.8  580.44  5080.8  584.07
  5090.8  584.84  5115.3  585.46    5143  585.63  5190.8  586.79  5200.8  587.41
  5220.8  587.61  5290.8  590.99  5310.8  591.22  5340.8  593.62  5364.4  593.27
#Mann= 6 ,-1 , 0
  4761.1     .12       0  4832.3     .05       0  5018.8    .033       0
  5022.8     .05       0  5115.3     .12       0    5143     .05       0
Bank Sta=5018.8,5022.8
XS Rating Curve= 0 ,0
Exp/Cntr=0.3,0.1

Type RM Length L Ch R = 1 ,1031    ,178,178,178
BEGIN DESCRIPTION:
Mapping XS 2cc06a36
END DESCRIPTION:
XS GIS Cut Line= 3
        2395194.      7059982.06      2394998.68      7059981.19
       2394665.2      7059981.01
#Sta/Elev= 30
  4806.3  597.45  4841.3  597.79  4861.3  597.37  4881.3  597.56  4891.3  596.83
  4901.3  592.66  4911.3  591.41  4961.3  588.62  4971.3  588.71  4981.3  586.97
    4997  574.27  4997.2  573.77  5000.7  573.77    5001  574.27  5011.3  574.38
  5021.3  580.31  5031.3  584.74  5041.3  586.66  5051.3  586.95  5071.3  585.47
  5091.3  585.51  5111.3  586.88  5141.3  586.33  5191.3  587.67  5231.3  590.04
  5271.3  590.13  5291.3  588.93  5311.3  591.94  5321.3  592.69  5335.1  593.01
#Mann= 3 ,-1 , 0
  4806.3     .05       0    4997    .033       0    5001     .05       0
Bank Sta=4997,5001
XS Rating Curve= 0 ,0
Exp/Cntr=0.3,0.1

Type RM Length L Ch R = 1 ,853     ,247,247,247
BEGIN DESCRIPTION:
LWE S WC_4 3.0
END DESCRIPTION:
XS GIS Cut Line= 3
        2395129.        7059810.        2394979.        7059810.
      2394756.51      7059901.32
#Sta/Elev= 30
  4850.4  597.11  4860.4  597.12  4870.4  595.16  4880.4  592.06  4900.4  589.61
  4910.4  589.16  4930.4  589.23  4940.4  587.58  4980.4  584.62  4990.4  581.07
  4997.9  577.34  5003.1  577.34  5009.7  574.46    5020  572.34  5020.3  571.84
  5023.8  571.84    5024  572.34  5032.8  575.37  5039.1  580.01  5054.4  581.96
  5068.4  582.66  5086.9  582.71  5092.4  584.51  5097.8  586.99  5108.5  587.93
  5140.4  588.37  5175.2   588.3  5193.7  587.45  5216.6  588.25  5240.9  587.74
#Mann= 3 ,-1 , 0
  4850.4     .05       0    5020    .033       0    5024     .05       0
Bank Sta=5020,5024
XS Rating Curve= 0 ,0
Exp/Cntr=0.3,0.1

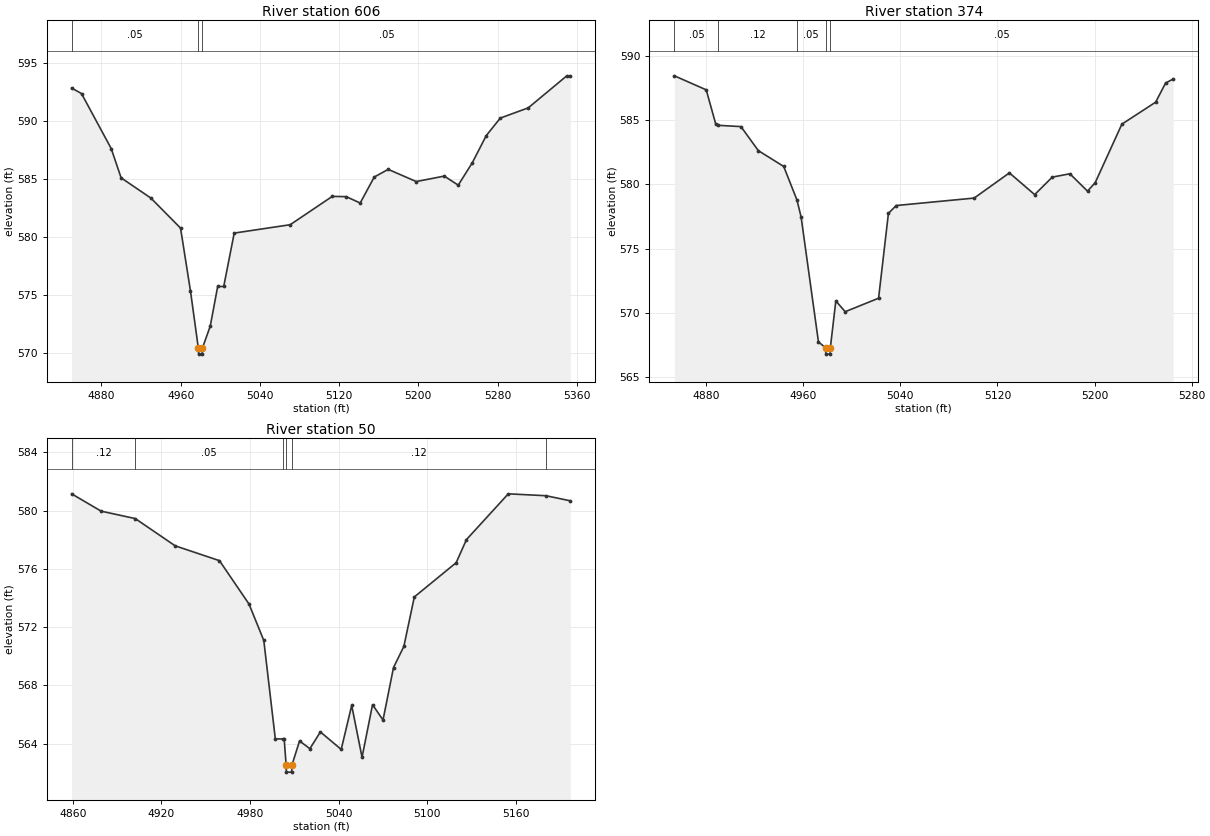
Type RM Length L Ch R = 1 ,606     ,232,232,232
BEGIN DESCRIPTION:
LWE S WC_4 2.0
END DESCRIPTION:
XS GIS Cut Line= 3
      2395029.02        7059610.        2394879.        7059610.
      2394628.98      7059860.02
#Sta/Elev= 30
  4849.9  592.83  4859.9  592.35  4889.9  587.61  4899.9  585.09  4929.9  583.35
  4959.9  580.76  4969.9  575.36  4977.9   570.4  4978.2   569.9  4981.7   569.9
  4981.9   570.4  4989.9  572.31  4997.4  575.73  5003.5  575.73  5014.1  580.33
  5070.6  581.05  5113.1  583.49  5127.2  583.47  5141.3  582.92  5155.5  585.16
  5169.6  585.82  5197.9  584.77  5226.2  585.24  5240.3  584.46  5254.5  586.39
  5268.6  588.73  5282.8  590.24    5311  591.12  5349.9  593.88  5353.5  593.88
#Mann= 3 ,-1 , 0
  4849.9     .05       0  4977.9    .033       0  4981.9     .05       0
Bank Sta=4977.9,4981.9
XS Rating Curve= 0 ,0
Exp/Cntr=0.3,0.1

Type RM Length L Ch R = 1 ,374     ,324,324,324
BEGIN DESCRIPTION:
Mapping XS 244334bf
END DESCRIPTION:
XS GIS Cut Line= 3
      2394828.26      7059341.89      2394731.93      7059457.75
      2394572.89      7059663.34
#Sta/Elev= 30
  4854.1  588.44  4880.3  587.35  4888.1   584.7  4890.2  584.59  4908.9  584.49
  4923.2  582.62  4944.1  581.39    4955  578.78  4958.4  577.47  4972.7  567.74
  4978.5  567.29  4978.8  566.79  4982.3  566.79  4982.5  567.29    4987  570.93
  4994.7  570.09  5022.2  571.14  5030.3  577.74  5036.7  578.35  5100.9  578.93
  5129.9  580.89  5150.7   579.2  5165.2  580.56  5179.7  580.82  5194.2  579.47
  5200.5  580.12  5222.5  584.68  5250.3  586.39  5258.5  587.88  5264.7  588.19
#Mann= 5 ,-1 , 0
  4854.1     .05       0  4890.2     .12       0    4955     .05       0
  4978.5    .033       0  4982.5     .05       0
Bank Sta=4978.5,4982.5
XS Rating Curve= 0 ,0
Exp/Cntr=0.3,0.1

Type RM Length L Ch R = 1 ,50      ,0,0,0
BEGIN DESCRIPTION:
LWE S WC_4 1.0
END DESCRIPTION:
XS GIS Cut Line= 3
        2394669.      7059255.06       2394528.3      7059260.29
      2394390.29      7059400.58
#Sta/Elev= 30
  4859.2  581.16  4879.2  579.97  4902.3  579.46  4929.3  577.59  4959.3  576.57
  4979.3  573.59  4989.3  571.09  4997.1  564.33  5002.2  564.33  5003.1  564.33
  5004.4  562.55  5004.6  562.05  5008.1  562.05  5008.4  562.55  5013.5  564.19
  5020.5  563.66  5027.6  564.81  5041.7  563.61  5048.8  566.63  5055.8  563.07
  5062.9  566.68    5070  565.63  5077.1  569.23  5084.1  570.68  5091.2  574.08
  5119.5  576.43  5126.5  578.02  5154.8  581.16  5180.3  581.03  5196.8  580.68
#Mann= 6 ,-1 , 0
  4859.2     .12       0  4902.3     .05       0  5002.2     .12       0
  5004.4    .033       0  5008.4     .12       0  5180.3     .05       0
Bank Sta=5004.4,5008.4
XS Rating Curve= 0 ,0
Exp/Cntr=0.3,0.1

Chan Stop Cuts=-1
Use User Specified Reach Order=0
Composite Channel Slope=5