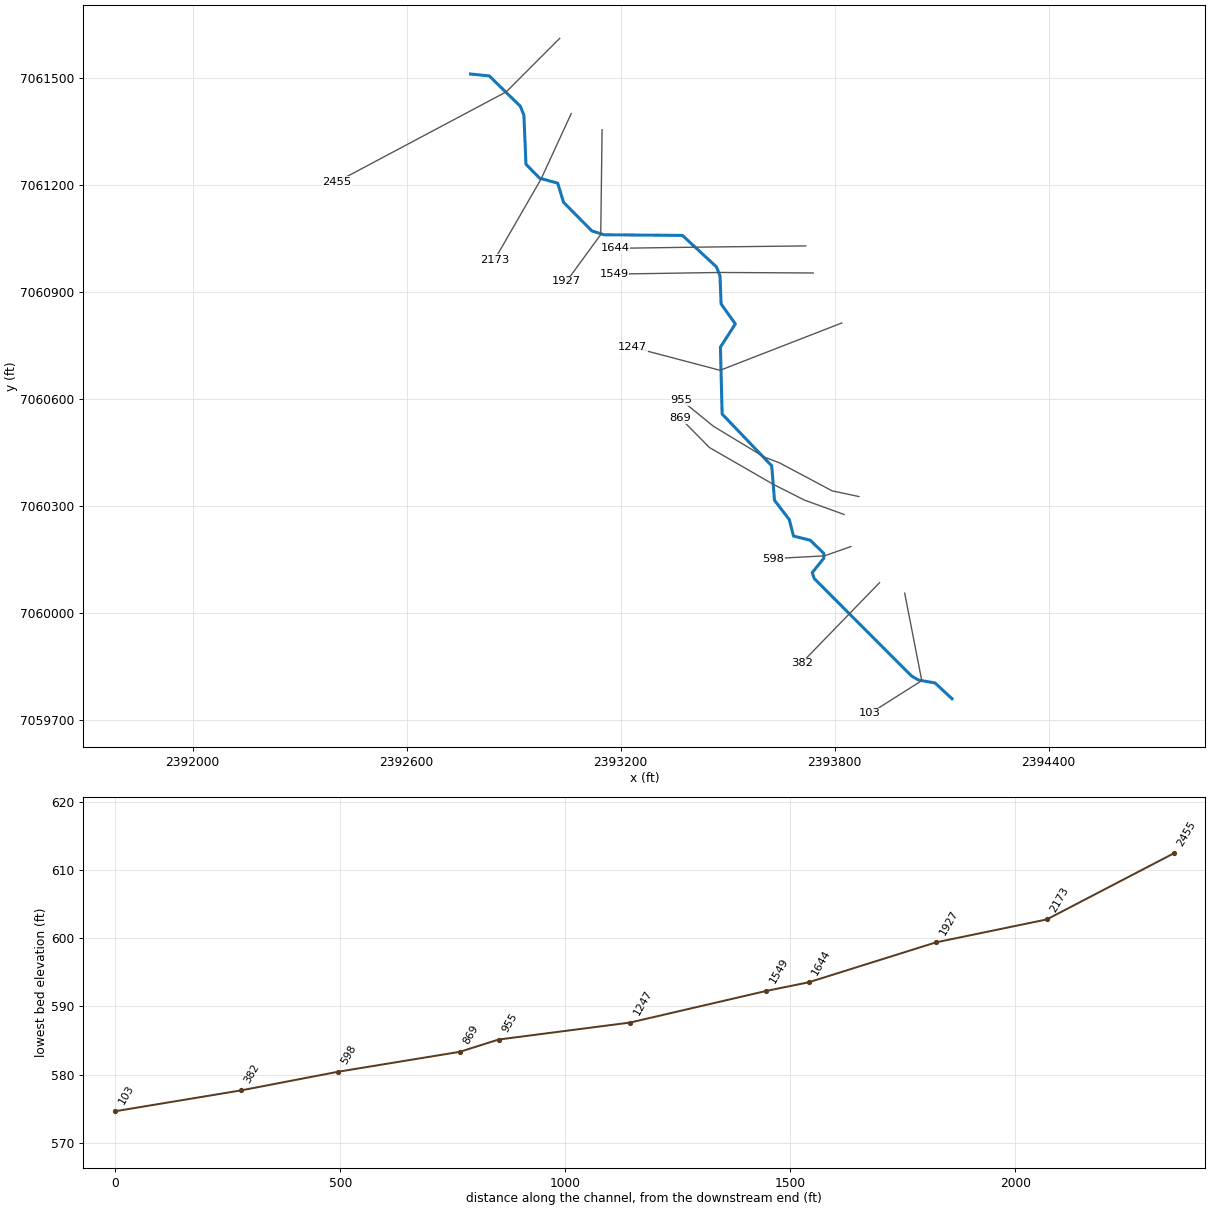
--- LWE S WC_5.prj (project) ---

Proj Title=LWE S WC_5 Base Level Engineering
Current Plan=p01
Default Exp/Contr=0.3,0.1
English Units
Geom File=g01
Flow File=f01
Plan File=p01
Y Axis Title=Elevation
X Axis Title(PF)=Main Channel Distance
X Axis Title(XS)=Station
BEGIN DESCRIPTION:
LWE S WC_5
END DESCRIPTION:
DSS Export Rating Curves= 0
DSS Export Rating Curve Sorted= 0
DSS Export Volume Flow Curves= 0
DXF OffsetX= 0
DXF OffsetY= 0
DXF ScaleX= 1
DXF ScaleY= 10

--- LWE S WC_5.p01 (plan) ---

Plan Title=Multiple Run
Short Identifier=Multiple
Geom File=g01
Flow File=f01
Subcritical Flow
K Sum by GR= 0
Std Step Tol= 0.01
Critical Tol= 0.01
Num of Std Step Trials= 20
Max Error Tol= 0.3
Flow Tol Ratio= 0.001
Split Flow NTrial= 30
Split Flow Tol= 0.02
Split Flow Ratio= 0.02
Log Output Level= 0
Friction Slope Method= 1
Unsteady Friction Slope Method= 2
Unsteady Bridges Friction Slope Method= 1
Parabolic Critical Depth
Global Vel Dist=  1 , 1 , 1
Global Log Level= 0
CheckData=True
Encroach Param= -1, 0, 0, 0
BEGIN DESCRIPTION:
Multiple Run
END DESCRIPTION:

--- LWE S WC_5.f01 (steady flow) ---

Flow Title=Multiple
Program Version=4.10
Number of Profiles= 7
Profile Names=10-year,25-year,50-year,1pct_min,100-year,1pct_plu,500-year
River Rch & RM=LWE S WC_5,Reach-1         ,2455
     289     380     452     268     536    1069     751
Boundary for River Rch & Prof#=LWE S WC_5,Reach-1         , 1
Up Type= 0
Dn Type= 3
Dn Slope=0.01175
Boundary for River Rch & Prof#=LWE S WC_5,Reach-1         , 2
Up Type= 0
Dn Type= 3
Dn Slope=0.01175
Boundary for River Rch & Prof#=LWE S WC_5,Reach-1         , 3
Up Type= 0
Dn Type= 3
Dn Slope=0.01175
Boundary for River Rch & Prof#=LWE S WC_5,Reach-1         , 4
Up Type= 0
Dn Type= 3
Dn Slope=0.01175
Boundary for River Rch & Prof#=LWE S WC_5,Reach-1         , 5
Up Type= 0
Dn Type= 3
Dn Slope=0.01175
Boundary for River Rch & Prof#=LWE S WC_5,Reach-1         , 6
Up Type= 0
Dn Type= 3
Dn Slope=0.01175
Boundary for River Rch & Prof#=LWE S WC_5,Reach-1         , 7
Up Type= 0
Dn Type= 3
Dn Slope=0.01175
DSS Import GetInterval= 0
DSS Import GetPeak= 0
DSS Import FillOption= 0

--- LWE S WC_5.g01 (geometry) ---

Geom Title=Existing Conditions
Program Version=4.10

River Reach=LWE S WC_5      ,Reach-1
Reach XY= 30
        2392779.        7061510.      2392831.54       7061504.7
      2392918.54      7061419.82      2392928.61      7061394.84
       2392934.4      7061257.32      2392972.92      7061218.15
      2393023.35      7061204.36      2393039.88      7061150.56
      2393119.18      7061070.47      2393153.87       7061059.7
      2393373.16      7061057.95      2393468.49      7060969.81
      2393478.49      7060944.79      2393481.56       7060865.9
      2393521.44        7060810.      2393479.66      7060744.84
      2393484.46      7060557.55      2393623.48      7060412.43
      2393631.32      7060315.94      2393672.73      7060261.84
      2393684.65      7060215.61       2393731.5      7060204.01
      2393769.77      7060166.93      2393769.43      7060153.48
      2393737.16      7060113.35      2393742.65      7060096.67
      2394015.77      7059823.57      2394034.97      7059812.34
      2394081.35      7059804.29        2394129.        7059760.

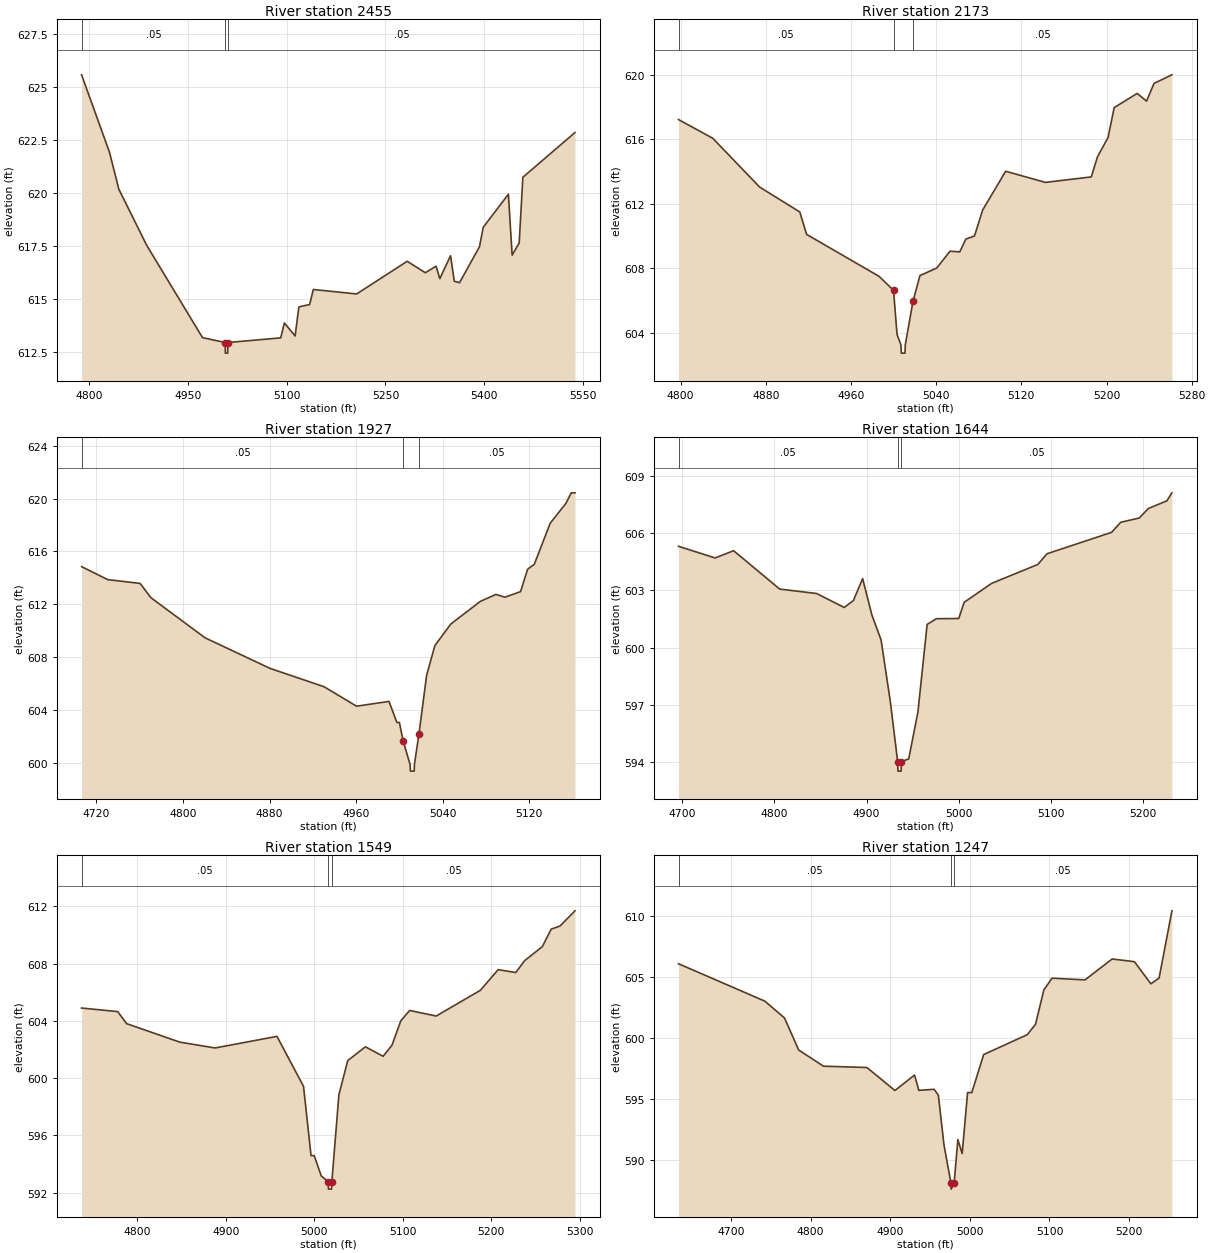
Type RM Length L Ch R = 1 ,2455    ,282,282,282
BEGIN DESCRIPTION:
LWE S WC_5 9.0
END DESCRIPTION:
XS GIS Cut Line= 3
        2393029.        7061610.        2392879.        7061460.
      2392404.13      7061207.84
#Sta/Elev= 30
  4788.3  625.56  4830.7  621.91  4844.9  620.17  4887.3  617.52  4972.1  613.17
  5006.6  612.94  5006.8  612.44  5010.3  612.44  5010.6  612.94  5090.9  613.16
  5096.5  613.86  5112.8  613.25  5118.5  614.62  5134.8  614.73  5140.5  615.44
  5206.4  615.23  5283.1  616.77  5310.7  616.23    5327  616.54  5332.7  615.95
    5349  617.03  5354.7  615.83  5362.7  615.76    5393  617.46  5398.6  618.37
  5436.9  619.93  5442.6  617.06  5453.3  617.63  5458.9  620.73  5538.1  622.84
#Mann= 3 ,-1 , 0
  4788.3     .05       0  5006.6    .033       0  5010.6     .05       0
Bank Sta=5006.6,5010.6
XS Rating Curve= 0 ,0
Exp/Cntr=0.3,0.1

Type RM Length L Ch R = 1 ,2173    ,246,246,246
BEGIN DESCRIPTION:
LWE S WC_5 8.0
END DESCRIPTION:
XS GIS Cut Line= 3
      2393061.35       7061399.2      2392976.76      7061215.87
      2392846.18      7060989.42
#Sta/Elev= 30
  4798.1  617.21  4830.3  616.05  4874.3  613.03    4912  611.49  4918.4   610.1
  4986.3  607.51    5000  606.64  5003.3  603.91    5007  603.25  5007.3  602.75
  5010.8  602.75    5011  603.25  5018.3  605.96  5024.8  607.55  5040.6  608.02
    5053  609.06  5062.2  609.02  5067.9  609.81    5076     610  5083.7  611.61
  5105.3  614.01  5142.6  613.32  5185.7  613.66  5191.5   614.9  5201.5  616.11
  5207.2  617.95  5228.8  618.83  5237.6  618.35  5244.6  619.45  5261.4  619.98
#Mann= 3 ,-1 , 0
  4798.1     .05       0    5000    .033       0  5018.3     .05       0
Bank Sta=5000,5018.3
XS Rating Curve= 0 ,0
Exp/Cntr=0.3,0.1

Type RM Length L Ch R = 1 ,1927    ,283,283,283
BEGIN DESCRIPTION:
LWE S WC_5 7.0
END DESCRIPTION:
XS GIS Cut Line= 3
      2393147.83      7061354.06      2393144.15      7061060.38
      2393048.37      7060929.36
#Sta/Elev= 30
  4706.3  614.85  4730.4  613.87  4760.4  613.58  4770.4   612.5  4820.4  609.47
  4880.4  607.16  4930.4  605.77  4960.4   604.3  4990.4  604.66  4997.7  603.07
    5000  603.07  5003.5  601.67  5009.9  599.89  5010.2  599.39  5013.7  599.39
  5013.9  599.89  5018.1   602.2  5025.2  606.64  5032.8  608.88  5047.5  610.51
  5074.8  612.22  5089.2  612.75  5097.6  612.54    5112  612.96  5118.5  614.65
  5124.7  615.03  5139.4  618.13    5154  619.64  5158.8  620.43  5162.3  620.43
#Mann= 3 ,-1 , 0
  4706.3     .05       0  5003.5    .033       0  5018.1     .05       0
Bank Sta=5003.5,5018.1
XS Rating Curve= 0 ,0
Exp/Cntr=0.3,0.1

Type RM Length L Ch R = 1 ,1644    ,95,95,95
BEGIN DESCRIPTION:
LWE S WC_5 6.0
END DESCRIPTION:
XS GIS Cut Line= 3
      2393718.83       7061028.5      2393414.75      7061025.02
      2393183.47      7061021.73
#Sta/Elev= 30
  4695.9   605.3  4735.7  604.69  4755.7  605.07  4805.7  603.06  4845.7  602.83
  4875.7   602.1  4885.7  602.46  4895.7  603.61  4905.7  601.71  4915.7   600.4
  4925.7  597.19  4933.7  594.03    4934  593.53  4937.5  593.53  4937.7  594.03
  4945.7  594.17  4955.7  596.63  4965.7  601.21  4975.7  601.51    5000  601.52
  5005.9  602.37  5035.7  603.36  5085.8  604.35  5095.8  604.91  5165.8  606.03
  5175.8  606.56  5195.8  606.78  5205.8  607.28  5225.8  607.68  5231.3   608.1
#Mann= 3 ,-1 , 0
  4695.9     .05       0  4933.7     .05       0  4937.7     .05       0
Bank Sta=4933.7,4937.7
XS Rating Curve= 0 ,0
Exp/Cntr=0.3,0.1

Type RM Length L Ch R = 1 ,1549    ,302,302,302
BEGIN DESCRIPTION:
Mapping XS 1255d47b
END DESCRIPTION:
XS GIS Cut Line= 3
      2393739.85      7060952.69      2393476.86      7060954.12
      2393182.09      7060949.53
#Sta/Elev= 30
    4737   604.9  4777.9  604.65  4787.9  603.81  4847.9  602.52  4887.9  602.11
  4957.9  602.92  4987.9  599.43  4996.4  594.59    5000  594.59  5007.9  593.18
  5015.9  592.75  5016.1  592.25  5019.6  592.25  5019.9  592.75  5027.9  598.84
  5037.9  601.23  5057.9  602.19  5077.9  601.53  5087.9   602.3  5097.9  604.01
  5107.9  604.73  5137.9  604.34  5187.9  606.14  5207.9  607.58  5227.9  607.38
  5237.9  608.21  5257.9  609.19  5267.9  610.41  5277.9  610.63  5294.8  611.69
#Mann= 3 ,-1 , 0
    4737     .05       0  5015.9     .05       0  5019.9     .05       0
Bank Sta=5015.9,5019.9
XS Rating Curve= 0 ,0
Exp/Cntr=0.3,0.1

Type RM Length L Ch R = 1 ,1247    ,292,292,292
BEGIN DESCRIPTION:
LWE S WC_5 5.0
END DESCRIPTION:
XS GIS Cut Line= 3
       2393819.7      7060812.46      2393478.81      7060680.06
      2393233.46      7060744.61
#Sta/Elev= 30
  4634.3  606.06  4742.7     603  4767.3  601.63  4785.2     599  4816.3  597.68
  4870.8  597.57    4906  595.69  4930.6  596.95    4936   595.7  4955.1  595.79
  4960.5  595.31  4967.6  591.22  4976.3  588.12  4976.6  587.62  4980.3  588.12
    4985  591.67  4990.4  590.53  4997.2  595.52  5002.5  595.52  5017.4  598.63
  5072.2  600.26  5082.5  601.11  5092.9  603.91  5103.2  604.88  5144.6  604.74
  5178.7  606.45  5206.6  606.23  5227.3  604.42  5237.6  604.89  5253.7  610.39
#Mann= 3 ,-1 , 0
  4634.3     .05       0  4976.3    .033       0  4980.3     .05       0
Bank Sta=4976.3,4980.3
XS Rating Curve= 0 ,0
Exp/Cntr=0.3,0.1

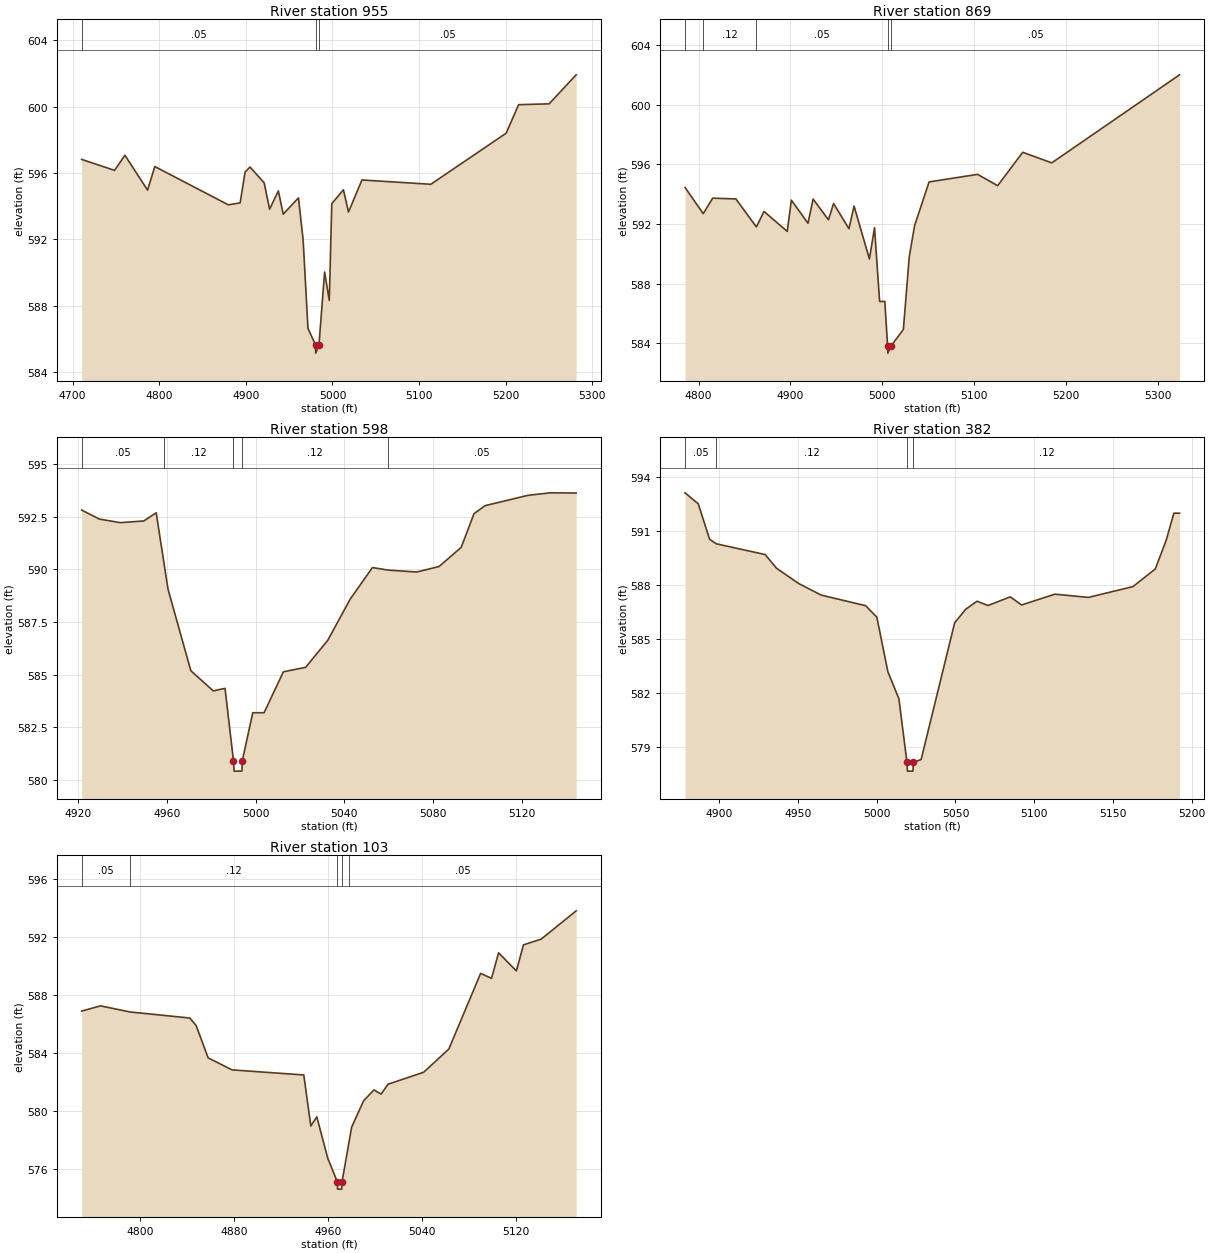
Type RM Length L Ch R = 1 ,955     ,86,86,86
BEGIN DESCRIPTION:
LWE S WC_5 4.0
END DESCRIPTION:
XS GIS Cut Line= 6
      2393867.91      7060326.36      2393792.98      7060342.38
      2393644.11      7060421.37      2393602.54      7060437.09
      2393459.95       7060523.4      2393370.97      7060595.65
#Sta/Elev= 30
  4710.4  596.81  4748.4  596.15  4760.4  597.06  4786.5  594.96  4794.9  596.38
  4879.8  594.07  4893.4  594.19  4899.1  596.05  4904.8  596.35  4921.1   595.4
  4927.4  593.81  4937.5  594.91  4943.1  593.51  4960.7  594.49  4966.1  591.96
  4971.7  586.62  4980.4  585.63  4980.7  585.13  4984.4  585.63  4990.9  590.02
  4996.3  588.31  4999.2  594.14  5012.6  594.98  5018.5  593.64    5034  595.57
  5113.5  595.31  5200.5  598.39  5214.9  600.11  5250.1  600.16  5281.3  601.91
#Mann= 3 ,-1 , 0
  4710.4     .05       0  4980.4     .05       0  4984.4     .05       0
Bank Sta=4980.4,4984.4
XS Rating Curve= 0 ,0
Exp/Cntr=0.3,0.1

Type RM Length L Ch R = 1 ,869     ,271,271,271
BEGIN DESCRIPTION:
LWE S WC_5 3.0
END DESCRIPTION:
XS GIS Cut Line= 5
      2393826.31      7060276.21      2393715.59      7060316.37
        2393629.        7060360.      2393448.77      7060463.76
      2393367.39      7060546.28
#Sta/Elev= 30
  4785.3  594.45  4805.1  592.69  4815.4  593.73  4840.7  593.68    4863   591.8
  4871.3  592.84  4896.6   591.5  4901.1   593.6  4919.2  592.05  4924.8  593.67
  4941.5  592.28  4947.1  593.37  4963.8  591.68  4969.4   593.2  4986.1  589.65
  4991.7  591.75  4997.2   586.8  5002.9   586.8  5005.9  583.83  5006.2  583.33
  5009.9  583.83  5023.1  584.92  5029.5  589.79  5035.3  591.88  5051.1  594.82
  5103.9  595.33  5125.8  594.57  5153.1  596.81  5184.7   596.1  5323.9  602.01
#Mann= 5 ,-1 , 0
  4785.3     .05       0  4805.1     .12       0    4863     .05       0
  5005.9     .05       0  5009.9     .05       0
Bank Sta=5005.9,5009.9
XS Rating Curve= 0 ,0
Exp/Cntr=0.3,0.1

Type RM Length L Ch R = 1 ,598     ,216,216,216
BEGIN DESCRIPTION:
LWE S WC_5 2.0
END DESCRIPTION:
XS GIS Cut Line= 3
      2393845.44      7060186.27       2393771.5       7060160.2
       2393627.3      7060152.63
#Sta/Elev= 30
  4921.6  592.83  4929.6   592.4    4939  592.23  4949.6  592.31  4955.2   592.7
  4958.7   590.3  4960.5  589.07  4970.8  585.18  4980.9  584.22  4986.2  584.34
    4990   580.9  4990.3   580.4  4993.8   580.4    4994   580.9  4998.7  583.18
  5003.8  583.18  5012.5  585.13  5022.5  585.34  5032.5  586.63  5042.6  588.59
  5052.6  590.09  5059.8  589.97  5072.6  589.88  5082.6  590.14  5092.6  591.05
  5098.4  592.66  5103.4  593.04  5122.7  593.53  5132.7  593.65  5144.4  593.64
#Mann= 5 ,-1 , 0
  4921.6     .05       0  4958.7     .12       0    4990     .07       0
    4994     .12       0  5059.8     .05       0
Bank Sta=4990,4994
XS Rating Curve= 0 ,0
Exp/Cntr=0.3,0.1

Type RM Length L Ch R = 1 ,382     ,279,279,279
BEGIN DESCRIPTION:
Mapping XS 9316f440
END DESCRIPTION:
XS GIS Cut Line= 3
      2393925.92      7060085.15      2393841.05      7059997.76
      2393707.16      7059859.89
#Sta/Elev= 30
  4878.3  593.12  4886.7  592.51  4893.9  590.54  4898.1  590.29  4929.2  589.69
  4936.4  588.93  4950.5  588.08  4964.7  587.44    4993  586.85  5000.1  586.21
  5007.1  583.18  5014.1  581.68  5019.2  578.16  5019.5  577.66    5023  577.66
  5023.2  578.16  5028.2   578.3  5049.5   585.9  5056.5  586.65  5063.7   587.1
  5070.7  586.86  5084.8  587.34    5092  586.89  5113.1  587.49  5134.4  587.31
  5162.7  587.91  5176.9  588.89  5183.8  590.48  5188.7  591.99  5192.3  591.99
#Mann= 4 ,-1 , 0
  4878.3     .05       0  4898.1     .12       0  5019.2     .07       0
  5023.2     .12       0
Bank Sta=5019.2,5023.2
XS Rating Curve= 0 ,0
Exp/Cntr=0.3,0.1

Type RM Length L Ch R = 1 ,103     ,0,0,0
BEGIN DESCRIPTION:
LWE S WC_5 1.0
END DESCRIPTION:
XS GIS Cut Line= 3
      2393996.38       7060055.8      2394044.26      7059810.63
      2393899.19      7059718.98
#Sta/Elev= 30
  4750.2   586.9  4766.3  587.26  4791.3  586.84  4842.4  586.42  4847.8   585.9
    4858  583.67  4878.4  582.84  4939.5  582.49  4945.5  578.97  4950.6   579.6
  4959.9  576.75  4968.1  575.11  4968.3  574.61  4971.8  574.61  4972.1  575.11
  4977.8  577.74  4980.3  578.89  4990.5  580.71  4999.3  581.46  5005.4  581.17
  5011.3  581.85  5041.7  582.68  5063.1  584.28  5090.2   589.5  5099.5  589.16
  5105.5  590.92  5120.7  589.67  5126.7  591.47  5141.9  591.87  5171.6  593.82
#Mann= 5 ,-1 , 0
  4750.2     .05       0  4791.3     .12       0  4968.1     .05       0
  4972.1     .12       0  4977.8     .05       0
Bank Sta=4968.1,4972.1
XS Rating Curve= 0 ,0
Exp/Cntr=0.3,0.1

Chan Stop Cuts=-1
Use User Specified Reach Order=0
Composite Channel Slope=5