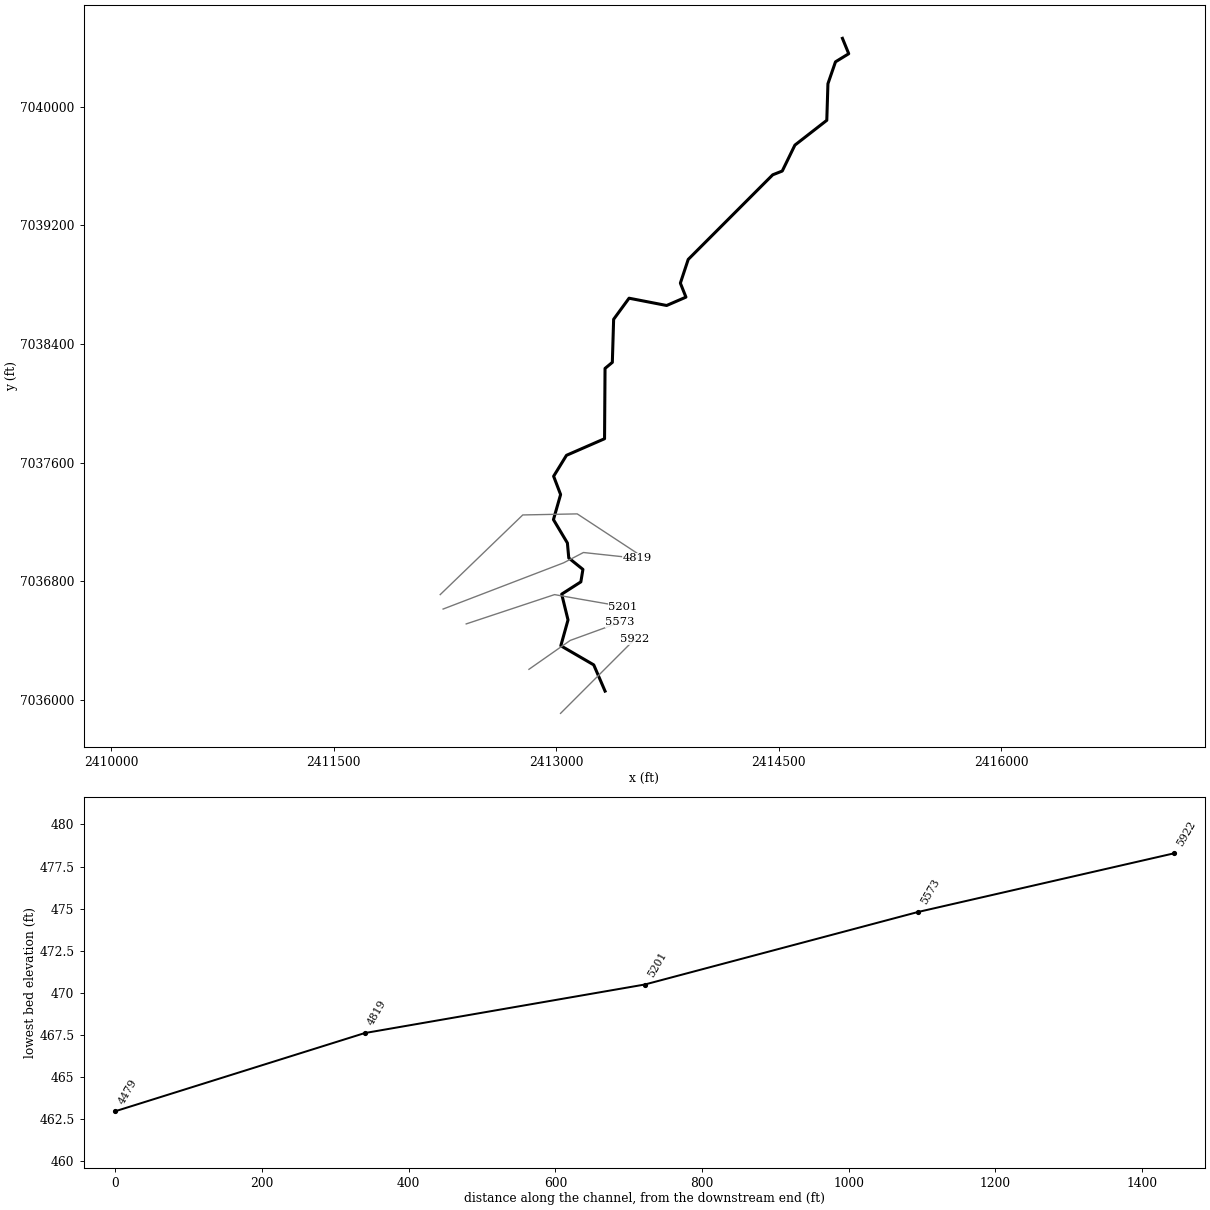
--- Lower Denton East 1.prj (project) ---

Proj Title=Lower Denton East 1 Base Level Engineering
Current Plan=p01
Default Exp/Contr=0.3,0.1
English Units
Geom File=g01
Flow File=f01
Plan File=p01
BEGIN DESCRIPTION:
Lower Denton East 1
END DESCRIPTION:

--- Lower Denton East 1.p01 (plan) ---

Plan Title=Multiple Run
Short Identifier=Multiple
Geom File=g01
Flow File=f01
Subcritical Flow
K Sum by GR= 0
Std Step Tol= 0.01
Critical Tol= 0.01
Num of Std Step Trials= 20
Max Error Tol= 0.3
Flow Tol Ratio= 0.001
Split Flow NTrial= 30
Split Flow Tol= 0.02
Split Flow Ratio= 0.02
Log Output Level= 0
Friction Slope Method= 1
Unsteady Friction Slope Method= 2
Unsteady Bridges Friction Slope Method= 1
Parabolic Critical Depth
Global Vel Dist=  1 , 1 , 1
Global Log Level= 0
CheckData=True
Encroach Param= -1, 0, 0, 0
BEGIN DESCRIPTION:
Multiple Run
END DESCRIPTION:

--- Lower Denton East 1.f01 (steady flow) ---

Flow Title=Multiple
Number of Profiles=7
Profile Names=10-year,25-year,50-year,1pct_min,100-year,1pct_plu,500-year
River Rch & RM= Lower Denton Eas,Reach-1,5922
     732    1011    1244     758    1513    3019    2239
Boundary for River Rch & Prof#=Lower Denton Eas,Reach-1,1
Up Type=0
Dn Type=3
Dn Slope=0.005
Boundary for River Rch & Prof#=Lower Denton Eas,Reach-1,2
Up Type=0
Dn Type=3
Dn Slope=0.005
Boundary for River Rch & Prof#=Lower Denton Eas,Reach-1,3
Up Type=0
Dn Type=3
Dn Slope=0.005
Boundary for River Rch & Prof#=Lower Denton Eas,Reach-1,4
Up Type=0
Dn Type=3
Dn Slope=0.005
Boundary for River Rch & Prof#=Lower Denton Eas,Reach-1,5
Up Type=0
Dn Type=3
Dn Slope=0.005
Boundary for River Rch & Prof#=Lower Denton Eas,Reach-1,6
Up Type=0
Dn Type=3
Dn Slope=0.005
Boundary for River Rch & Prof#=Lower Denton Eas,Reach-1,7
Up Type=0
Dn Type=3
Dn Slope=0.005

--- Lower Denton East 1.g01 (geometry) ---

Geom Title=Existing Conditions

River Reach=Lower Denton Eas,Reach-1
Reach XY= 30
      2413329.00      7036060.00      2413252.74      7036236.89
      2413030.88      7036365.69      2413079.39      7036539.87
      2413036.69      7036713.67      2413165.82      7036796.38
      2413179.79      7036880.32      2413084.46      7036957.34
      2413075.17      7037058.41      2412981.14      7037215.97
      2413029.39      7037385.00      2412982.34      7037508.28
      2413069.00      7037649.37      2413325.56      7037761.22
      2413328.88      7038235.12      2413378.04      7038275.96
      2413386.83      7038566.19      2413490.83      7038708.39
      2413744.07      7038659.28      2413874.21      7038715.59
      2413836.60      7038809.96      2413889.52      7038969.79
      2414459.08      7039540.14      2414523.41      7039565.61
      2414608.58      7039740.23      2414823.55      7039907.53
      2414831.26      7040154.07      2414882.21      7040301.66
      2414971.48      7040356.36      2414929.00      7040460.00

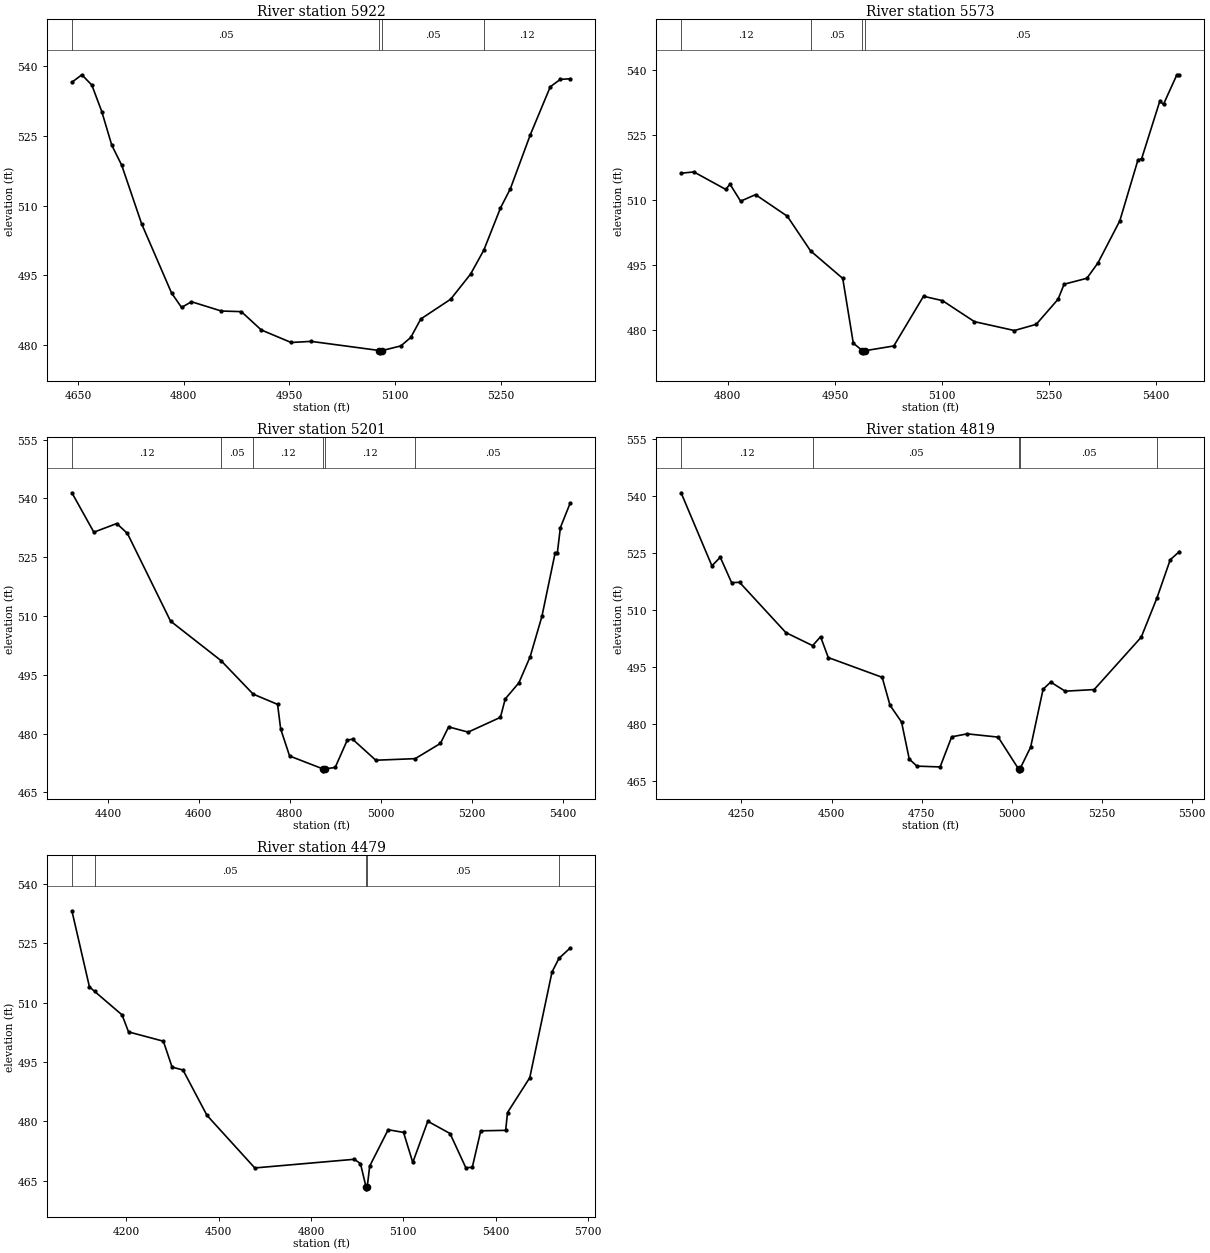
Type RM Length L Ch R = 1,5922,349,349,349
BEGIN DESCRIPTION:
Denton Creek 16.0
END DESCRIPTION:
XS GIS Cut Line= 3
      2413029.00      7035910.00      2413279.00      7036160.00
      2413529.00      7036410.00
#Sta/Elev= 30
  4641.5  536.59  4655.6  538.20  4669.8  535.98  4683.9  530.27  4698.1  523.02
  4712.2  518.70  4740.5  506.06  4782.9  491.18  4797.1  488.06  4811.2  489.29
  4853.6  487.29  4881.9  487.16  4910.2  483.21  4952.6  480.51  4980.9  480.75
  5077.9  478.78  5078.2  478.28  5081.9  478.78  5108.2  479.77  5122.3  481.59
  5136.5  485.57  5178.9  489.83  5207.2  495.25  5226.0  500.42  5249.6  509.49
  5263.7  513.67  5292.0  525.30  5320.3  535.62  5334.5  537.21  5348.6  537.34
#Mann=4,-1,0
  4641.5    0.05       0  5077.9   0.033       0  5081.9    0.05       0
  5226.0    0.12       0
Bank Sta=5077.9,5081.9
Exp/Cntr=0.3,0.1

Type RM Length L Ch R = 1,5573,372,372,372
BEGIN DESCRIPTION:
Denton Creek 15.0
END DESCRIPTION:
XS GIS Cut Line= 3
      2412816.03      7036207.02      2413094.21      7036401.75
      2413430.79      7036524.14
#Sta/Elev= 30
  4734.7  516.26  4752.6  516.55  4797.1  512.53  4803.2  513.72  4818.0  509.80
  4838.9  511.31  4883.4  506.33  4915.9  498.34  4961.0  491.97  4975.8  477.02
  4988.6  475.29  4988.9  474.79  4992.6  475.29  5032.5  476.38  5074.1  487.85
  5100.6  486.84  5145.4  481.99  5201.3  479.94  5231.9  481.37  5262.5  487.17
  5270.9  490.63  5302.8  492.00  5318.3  495.54  5348.9  505.26  5374.2  519.26
  5379.5  519.63  5404.8  532.84  5410.1  532.17  5428.8  538.98  5432.4  538.98
#Mann=4,-1,0
  4734.7    0.12       0  4915.9    0.05       0  4988.6   0.033       0
  4992.6    0.05       0
Bank Sta=4988.6,4992.6
Exp/Cntr=0.3,0.1

Type RM Length L Ch R = 1,5201,382,382,382
BEGIN DESCRIPTION:
Denton Creek 14.0
END DESCRIPTION:
XS GIS Cut Line= 4
      2412393.15      7036513.01      2412988.50      7036710.54
      2413160.98      7036679.94      2413450.34      7036629.86
#Sta/Elev= 30
  4320.9  541.44  4369.2  531.38  4419.5  533.59  4443.0  531.07  4537.8  508.70
  4648.9  498.61  4719.6  490.06  4773.3  487.44  4780.1  481.17  4799.7  474.27
  4872.9  470.98  4873.2  470.48  4876.9  470.98  4900.0  471.34  4926.5  478.31
  4938.2  478.56  4989.3  473.19  5076.0  473.59  5131.5  477.48  5149.5  481.70
  5192.4  480.36  5263.4  484.13  5274.1  488.85  5304.0  492.93  5328.8  499.60
  5354.7  509.90  5383.5  525.95  5388.6  526.07  5395.3  532.55  5417.0  538.85
#Mann=6,-1,0
  4320.9    0.12       0  4648.9    0.05       0  4719.6    0.12       0
  4872.9    0.07       0  4876.9    0.12       0  5076.0    0.05       0
Bank Sta=4872.9,4876.9
Exp/Cntr=0.3,0.1

Type RM Length L Ch R = 1,4819,340,340,340
BEGIN DESCRIPTION:
Denton Creek 13.0
END DESCRIPTION:
XS GIS Cut Line= 4
      2412237.40      7036613.18      2413049.70      7036924.74
      2413183.23      7036994.29      2413544.49      7036955.39
#Sta/Elev= 30
  4082.3  540.88  4167.8  521.63  4191.1  523.88  4222.5  517.21  4244.7  517.27
  4373.2  504.03  4447.6  500.59  4469.6  502.94  4491.0  497.45  4640.7  492.24
  4662.4  484.88  4694.5  480.46  4715.9  470.68  4737.3  468.83  4801.6  468.62
  4833.7  476.55  4876.6  477.34  4962.8  476.48  5019.3  468.09  5019.6  467.59
  5023.3  468.09  5053.0  473.84  5087.6  489.12  5108.7  490.98  5148.9  488.59
  5229.4  489.01  5360.1  502.82  5403.9  513.20  5440.6  523.22  5466.2  525.40
#Mann=5,-1,0
  4082.3    0.12       0  4447.6    0.05       0  5019.3   0.033       0
  5023.3    0.05       0  5403.9    0.12       0
Bank Sta=5019.3,5023.3
Exp/Cntr=0.3,0.1

Type RM Length L Ch R = 1,4479,0,0,0
BEGIN DESCRIPTION:
Denton Creek 12.0
END DESCRIPTION:
XS GIS Cut Line= 4
      2412217.96      7036710.57      2412774.30      7037247.44
      2413141.53      7037254.64      2413542.09      7036991.51
#Sta/Elev= 30
  4022.9  533.21  4079.9  513.98  4096.6  512.84  4185.9  506.90  4207.0  502.60
  4320.2  500.25  4348.5  493.70  4384.0  492.97  4461.7  481.53  4617.3  468.22
  4940.8  470.41  4960.8  469.31  4978.8  463.44  4979.0  462.94  4982.8  463.44
  4990.8  468.69  5050.8  477.88  5100.8  477.20  5130.8  469.60  5179.6  480.02
  5251.9  476.92  5303.2  468.28  5324.2  468.37  5351.8  477.60  5432.7  477.72
  5438.7  482.22  5511.0  491.02  5583.3  517.73  5605.9  521.18  5642.6  523.82
#Mann=5,-1,0
  4022.9    0.12       0  4096.6    0.05       0  4978.8   0.033       0
  4982.8    0.05       0  5605.9    0.12       0
Bank Sta=4978.8,4982.8
Exp/Cntr=0.3,0.1

Chan Stop Cuts=-1