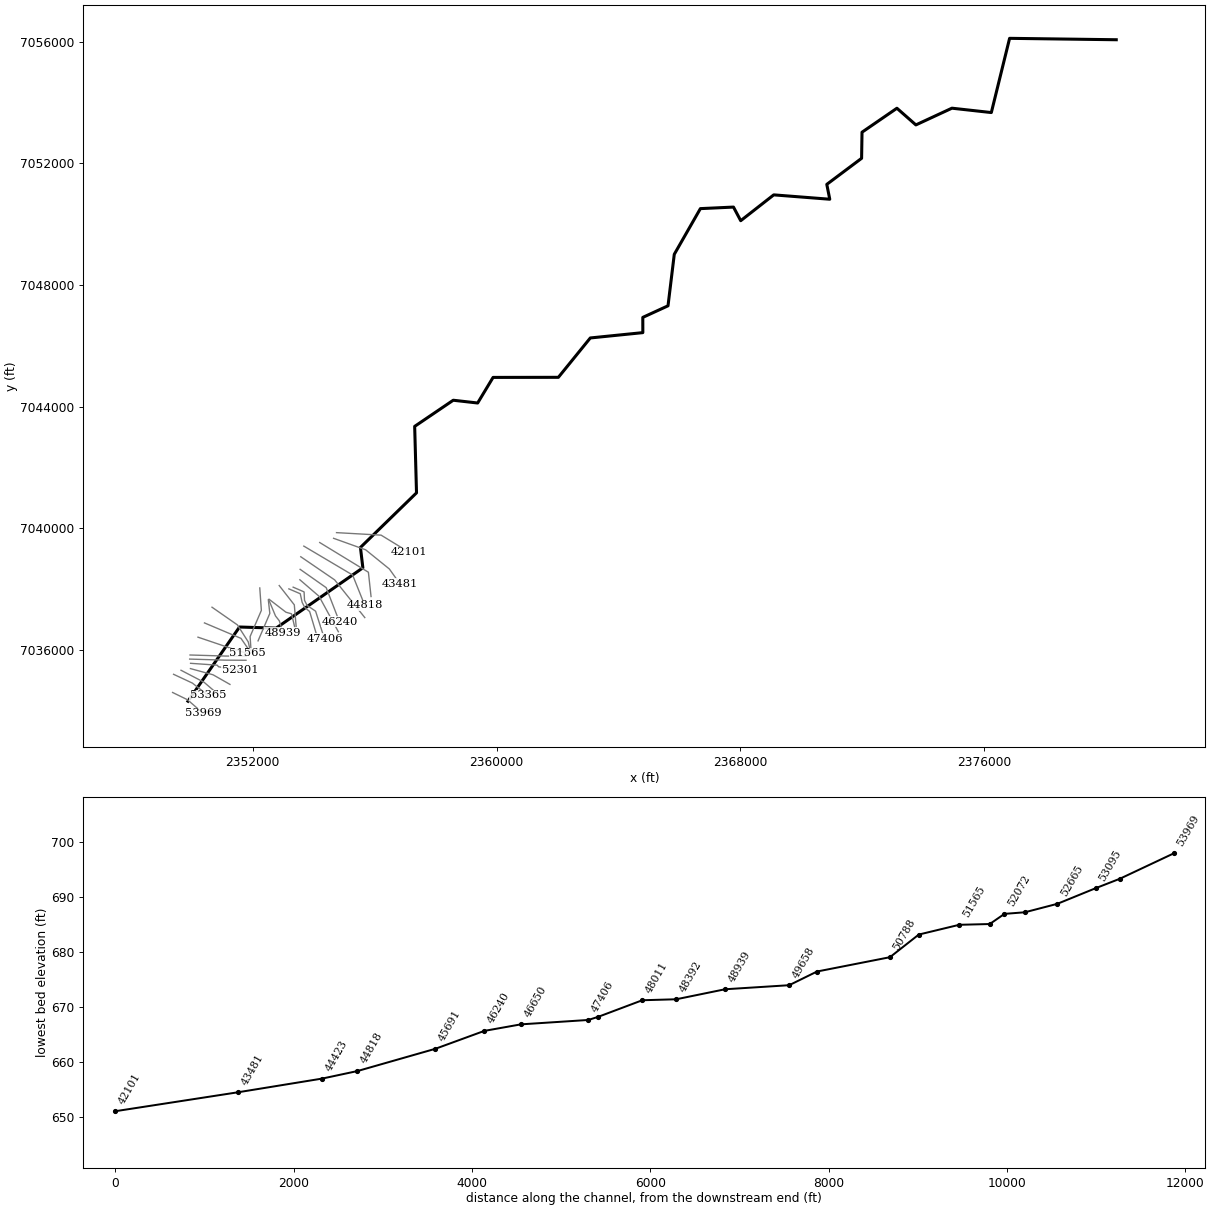
--- Marshall Branch.prj (project) ---

Proj Title=Marshall Branch Base Level Engineering
Current Plan=p01
Default Exp/Contr=0.3,0.1
English Units
Geom File=g01
Flow File=f01
Plan File=p01
Y Axis Title=Elevation
X Axis Title(PF)=Main Channel Distance
X Axis Title(XS)=Station
BEGIN DESCRIPTION:
Marshall Branch
END DESCRIPTION:
DSS Export Rating Curves= 0
DSS Export Rating Curve Sorted= 0
DSS Export Volume Flow Curves= 0
DXF OffsetX= 0
DXF OffsetY= 0
DXF ScaleX= 1
DXF ScaleY= 10

--- Marshall Branch.p01 (plan) ---

Plan Title=Multiple Run
Program Version=4.10
Short Identifier=Multiple
Geom File=g01
Flow File=f01
Subcritical Flow
K Sum by GR= 0
Std Step Tol= 0.01
Critical Tol= 0.01
Num of Std Step Trials= 20
Max Error Tol= 0.3
Flow Tol Ratio= 0.001
Split Flow NTrial= 30
Split Flow Tol= 0.02
Split Flow Ratio= 0.02
Log Output Level= 0
Friction Slope Method= 1
Unsteady Friction Slope Method= 2
Unsteady Bridges Friction Slope Method= 1
Parabolic Critical Depth
Global Vel Dist= 1 , 1 , 1
Global Log Level= 0
CheckData=True
Encroach Param=-1 ,0,0, 0
BEGIN DESCRIPTION:
Multiple Run
END DESCRIPTION:
Computation Interval=1HOUR
Output Interval=1HOUR
Run HTab= 0
Run UNet= 0
Run PostProcess= 0
Run WQNet= 0
UNET Theta= 1
UNET Theta Warmup= 1
UNET ZTol= 0.02
UNET ZSATol= 0.05
UNET MxIter= 20
UNET MaxInSteps= 0
UNET DtIC= 0
UNET DtMin= 0
UNET MaxCRTS= 20
UNET WFStab= 2
UNET SFStab= 1
UNET WFX= 1
UNET SFX= 1
UNET DSS MLevel= 4
UNET DZMax Abort= 100
UNET Convert EG Bridges= 0
UNET Use Existing IB Tables=-1
UNET Froude Reduction=False
UNET Froude Limit= 1
UNET Froude Power= 10
UNET Time Slicing=0,0, 5
UNET Junction Losses=0
Instantaneous Interval=1HOUR
Write IC File= 0
Write IC File at Sim End=0
Echo Input=False
Echo Parameters=False
Echo Output=False
Write Detailed= 0
WQ AD Non Conservative
WQ ULTIMATE=-1
WQ Max Comp Step=1HOUR
WQ Output Interval=15MIN
WQ Output Selected Increments= 0
WQ Output face flow=0
WQ Output face velocity=0
WQ Output face area=0
WQ Output face dispersion=0
WQ Output cell volume=0
WQ Output cell surface area=0
WQ Output cell continuity=0
WQ Output cumulative cell continuity=0
WQ Output face conc=0
WQ Output face dconc_dx=0
WQ Output face courant=0
WQ Output face peclet=0
WQ Output face adv mass=0
WQ Output face disp mass=0
WQ Output cell mass=0
WQ Output cell source sink temp=0
WQ Output cell source sink nsm=0
WQ Output MaxMinRange=-1
WQ Daily Max Min Mean=-1
WQ Daily Range=0
WQ Daily Time=0
WQ Create Restart=0
WQ Fixed Restart=0
WQ System Summary=0
WQ Use Fixed Temperature=0
Sorting and Armoring Iterations= 10
XS Update Threshold= 0.02
Hydraulics Update Threshold= 0.02
Energy Slope Method= 1
Volume Change Method= 0
XS Weighting Method= 0
Number of US Weighted Cross Sections= 1
Number of DS Weighted Cross Sections= 1
Upstream XS Weight=0.25
Main XS Weight=0.5
Downstream XS Weight=0.25
Number of DS XS's Weighted with US Boundary= 1
Upstream Boundary Weight= 1
Weight of XSs Associated with US Boundary= 0
Number of US XS's Weighted with DS Boundary= 1
Downstream Boundary Weight= 0.5
Weight of XSs Associated with DS Boundary= 0.5
Sediment Output Level= 4
Mass or Volume Output= 0
Output Increment Type= 1
Profile and TS Output Increment= 10
XS Output Flag= 0
XS Output Increment= 10
Disregard all LS=0
Disregard all Conn=0
Disregard all Breaches=0
Disregard all Pumps=0

--- Marshall Branch.f01 (steady flow) ---

Flow Title=Multiple
Number of Profiles=7
Profile Names=10-year,25-year,50-year,1pct_min,100-year,1pct_plu,500-year
River Rch & RM= Marshall Branch,Reach-1,53969
     719     990    1214     738    1473    2938    2166
River Rch & RM= Marshall Branch,Reach-1,51111
     957    1331    1644    1006    2006    4003    2987
River Rch & RM= Marshall Branch,Reach-1,48011
    1112    1557    1931    1185    2364    4717    3543
River Rch & RM= Marshall Branch,Reach-1,44818
    1234    1734    2155    1325    2643    5273    3975
River Rch & RM= Marshall Branch,Reach-1,43481
    2135    3079    3893    2430    4848    9674    7524
River Rch & RM= Marshall Branch,Reach-1,36821
    2434    3527    4475    2800    5588   11149    8721
River Rch & RM= Marshall Branch,Reach-1,33652
    2469    3579    4541    2843    5672   11318    8857
River Rch & RM= Marshall Branch,Reach-1,32693
    2658    3863    4909    3077    6139   12249    9610
River Rch & RM= Marshall Branch,Reach-1,30423
    2921    4258    5423    3405    6793   13555   10672
River Rch & RM= Marshall Branch,Reach-1,27694
    2939    4283    5453    3423    6830   13627   10723
River Rch & RM= Marshall Branch,Reach-1,26712
    3625    5337    6842    4323    8626   17212   13724
River Rch & RM= Marshall Branch,Reach-1,25916
    3679    5419    6951    4394    8767   17492   13958
River Rch & RM= Marshall Branch,Reach-1,24132
    3803    5609    7201    4555    9088   18133   14490
River Rch & RM= Marshall Branch,Reach-1,23252
    3824    5637    7234    4575    9128   18212   14543
River Rch & RM= Marshall Branch,Reach-1,20869
    3086    4520    5779    3648    7278   14522   11583
River Rch & RM= Marshall Branch,Reach-1,18972
    3122    4575    5850    3694    7370   14706   11736
River Rch & RM= Marshall Branch,Reach-1,18049
    3170    4646    5943    3753    7489   14942   11928
River Rch & RM= Marshall Branch,Reach-1,16585
    3210    4707    6022    3803    7588   15141   12088
River Rch & RM= Marshall Branch,Reach-1,14383
    3455    5069    6488    4098    8177   16315   13030
River Rch & RM= Marshall Branch,Reach-1,7676
    3497    5128    6562    4143    8266   16493   13161
Boundary for River Rch & Prof#=Marshall Branch,Reach-1,1
Up Type=0
Dn Type=3
Dn Slope=0.002
Boundary for River Rch & Prof#=Marshall Branch,Reach-1,2
Up Type=0
Dn Type=3
Dn Slope=0.002
Boundary for River Rch & Prof#=Marshall Branch,Reach-1,3
Up Type=0
Dn Type=3
Dn Slope=0.002
Boundary for River Rch & Prof#=Marshall Branch,Reach-1,4
Up Type=0
Dn Type=3
Dn Slope=0.002
Boundary for River Rch & Prof#=Marshall Branch,Reach-1,5
Up Type=0
Dn Type=3
Dn Slope=0.002
Boundary for River Rch & Prof#=Marshall Branch,Reach-1,6
Up Type=0
Dn Type=3
Dn Slope=0.002
Boundary for River Rch & Prof#=Marshall Branch,Reach-1,7
Up Type=0
Dn Type=3
Dn Slope=0.002

--- Marshall Branch.g01 (geometry) ---

Geom Title=Existing Conditions

River Reach=Marshall Branch,Reach-1
Reach XY= 30
      2349879.00      7034310.00      2351569.19      7036749.49
      2352770.72      7036713.05      2355615.63      7038696.27
      2355536.47      7039366.08      2357375.64      7041161.25
      2357315.25      7043346.80      2358580.25      7044206.49
      2359381.45      7044115.45      2359887.29      7044956.94
      2362029.00      7044960.00      2363076.64      7046254.25
      2364799.66      7046429.40      2364798.44      7046930.55
      2365625.62      7047311.40      2365831.08      7049004.76
      2366687.28      7050506.94      2367773.57      7050557.84
      2368010.55      7050109.85      2369093.70      7050959.12
      2370931.39      7050815.69      2370834.16      7051304.58
      2371975.90      7052161.65      2371989.76      7053019.68
      2373134.45      7053807.85      2373756.25      7053259.48
      2374938.79      7053809.30      2376231.32      7053665.82
      2376830.55      7056106.25      2380329.00      7056060.00

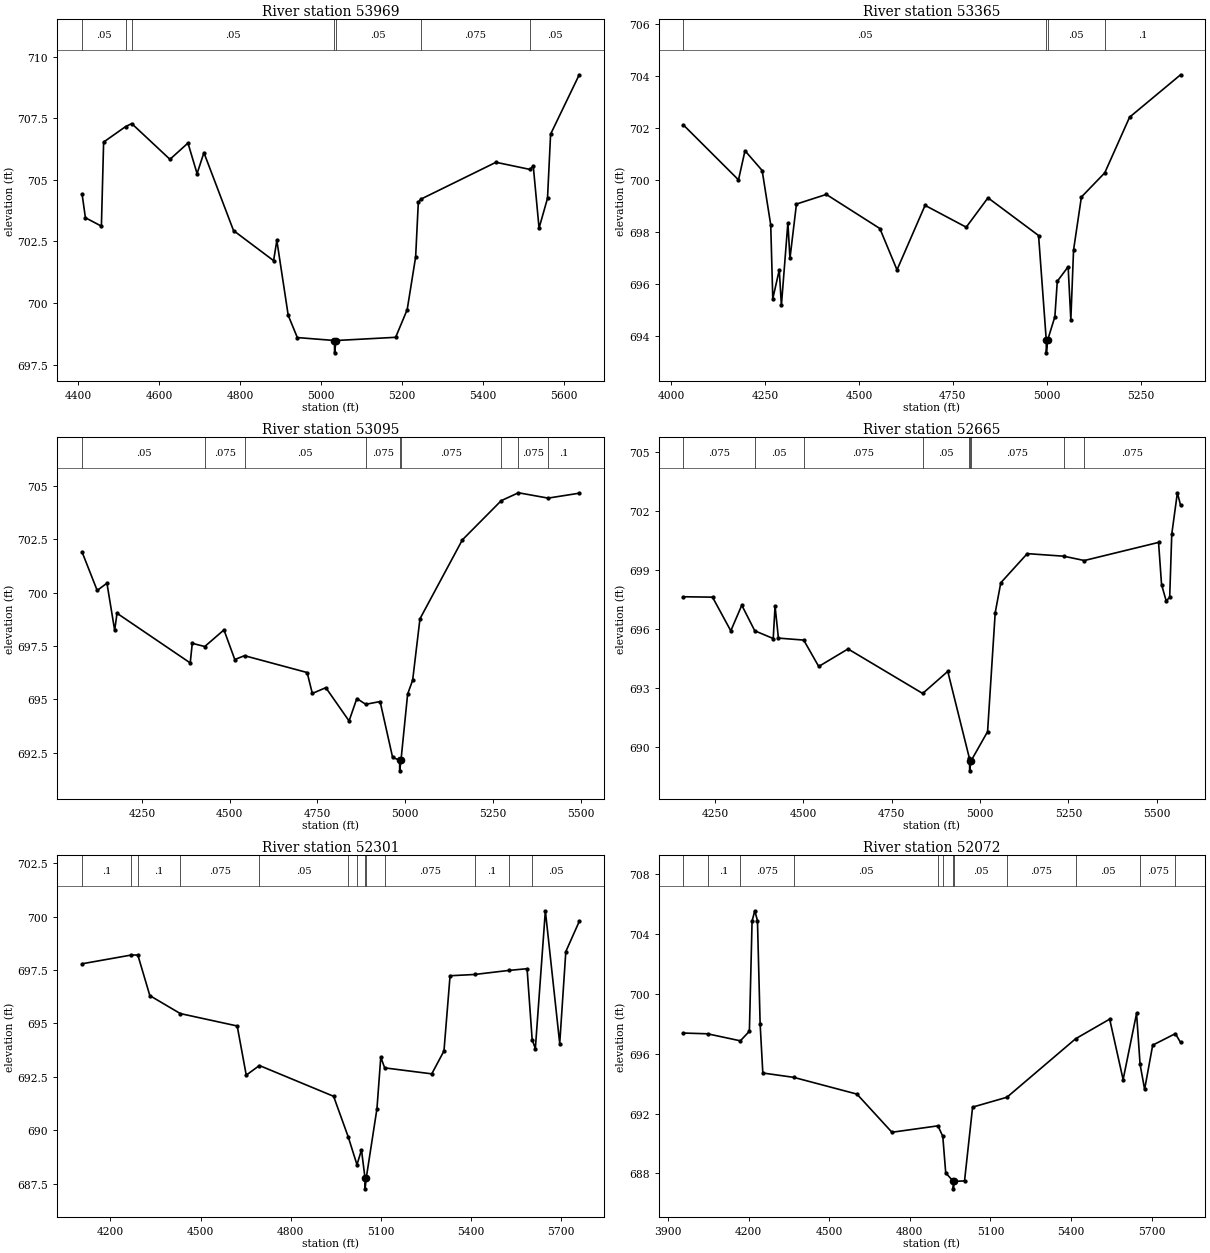
Type RM Length L Ch R = 1,53969,604,604,604
BEGIN DESCRIPTION:
Marshall Branch 80.0
END DESCRIPTION:
XS GIS Cut Line= 3
      2349374.07      7034597.36      2349863.43      7034358.12
      2350378.99      7033910.00
#Sta/Elev= 30
  4409.5  704.42  4417.7  703.46  4457.2  703.12  4462.7  706.53  4517.1  707.16
  4532.1  707.28  4626.5  705.83  4671.0  706.49  4693.5  705.25  4710.4  706.10
  4783.5  702.94  4882.5  701.72  4890.5  702.54  4918.6  699.50  4941.1  698.60
  5032.8  698.48  5033.1  697.98  5036.8  698.48  5183.9  698.61  5212.4  699.73
  5233.3  701.87  5239.9  704.08  5245.7  704.21  5431.7  705.71  5515.9  705.42
  5523.8  705.56  5538.1  703.04  5559.0  704.25  5566.6  706.85  5637.3  709.26
#Mann=7,-1,0
  4409.5    0.05       0  4517.1   0.075       0  4532.1    0.05       0
  5032.8   0.033       0  5036.8    0.05       0  5245.7   0.075       0
  5515.9    0.05       0
Bank Sta=5032.8,5036.8
Exp/Cntr=0.3,0.1

Type RM Length L Ch R = 1,53365,270,270,270
BEGIN DESCRIPTION:
Marshall Branch 79.0
END DESCRIPTION:
XS GIS Cut Line= 3
      2349406.42      7035194.93      2350022.64      7034906.32
      2350529.02      7034509.98
#Sta/Elev= 30
  4032.7  702.12  4179.3  700.01  4196.6  701.13  4242.3  700.37  4265.1  698.28
  4270.6  695.44  4287.9  696.55  4293.5  695.18  4310.8  698.36  4316.3  696.99
  4333.6  699.08  4413.1  699.45  4555.6  698.14  4601.3  696.55  4676.0  699.03
  4785.6  698.19  4843.5  699.32  4978.2  697.87  4998.6  693.86  4998.9  693.36
  5002.6  693.86  5021.6  694.75  5028.0  696.11  5056.9  696.67  5064.1  694.63
  5071.3  697.31  5092.2  699.35  5154.4  700.28  5220.5  702.42  5356.2  704.05
#Mann=4,-1,0
  4032.7    0.05       0  4998.6    0.05       0  5002.6    0.05       0
  5154.4     0.1       0
Bank Sta=4998.6,5002.6
Exp/Cntr=0.3,0.1

Type RM Length L Ch R = 1,53095,430,430,430
BEGIN DESCRIPTION:
Marshall Branch 78.0
END DESCRIPTION:
XS GIS Cut Line= 3
      2349650.83      7035327.53      2350407.45      7034932.32
      2350833.82      7034565.75
#Sta/Elev= 30
  4079.8  701.91  4122.8  700.11  4150.6  700.45  4172.6  698.24  4179.3  699.04
  4387.8  696.71  4393.6  697.63  4429.2  697.48  4483.9  698.26  4514.7  696.87
  4542.4  697.05  4720.8  696.26  4735.5  695.28  4774.0  695.55  4840.2  693.99
  4862.3  695.04  4887.8  694.77  4928.6  694.90  4964.2  692.28  4984.1  692.15
  4984.4  691.65  4988.1  692.15  5007.0  695.25  5021.3  695.90  5042.1  698.78
  5162.8  702.48  5273.6  704.32  5322.6  704.69  5407.1  704.44  5495.7  704.67
#Mann=9,-1,0
  4079.8    0.05       0  4429.2   0.075       0  4542.4    0.05       0
  4887.8   0.075       0  4984.1    0.07       0  4988.1   0.075       0
  5273.6     0.1       0  5322.6   0.075       0  5407.1     0.1       0
Bank Sta=4984.1,4988.1
Exp/Cntr=0.3,0.1

Type RM Length L Ch R = 1,52665,364,364,364
BEGIN DESCRIPTION:
Marshall Branch 77.0
END DESCRIPTION:
XS GIS Cut Line= 3
      2349959.68      7035382.58      2350701.91      7035178.58
      2351255.72      7034862.73
#Sta/Elev= 30
  4160.3  697.64  4242.6  697.62  4294.4  695.91  4325.5  697.21  4362.3  695.91
  4414.5  695.52  4419.7  697.16  4429.2  695.54  4500.8  695.44  4543.3  694.10
  4626.3  694.99  4837.6  692.73  4908.6  693.85  4969.5  689.46  4970.3  689.30
  4970.6  688.80  4974.3  689.30  5021.3  690.79  5042.9  696.83  5058.7  698.35
  5133.6  699.83  5236.6  699.70  5295.2  699.48  5505.3  700.40  5513.8  698.26
  5526.9  697.43  5536.8  697.61  5542.7  700.82  5558.6  702.92  5567.6  702.29
#Mann=9,-1,0
  4160.3   0.075       0  4362.3    0.05       0  4500.8   0.075       0
  4837.6    0.05       0  4969.5   0.075       0  4970.3    0.07       0
  4974.3   0.075       0  5236.6    0.05       0  5295.2   0.075       0
Bank Sta=4970.3,4974.3
Exp/Cntr=0.3,0.1

Type RM Length L Ch R = 1,52301,229,229,229
BEGIN DESCRIPTION:
Marshall Branch 76.0
END DESCRIPTION:
XS GIS Cut Line= 4
      2349964.07      7035556.18      2350836.46      7035495.42
      2350883.39      7035442.61      2351583.01      7035326.14
#Sta/Elev= 30
  4105.7  697.79  4269.6  698.20  4291.2  698.20  4331.2  696.30  4432.6  695.46
  4621.9  694.88  4652.0  692.58  4695.8  693.03  4942.7  691.59  4991.4  689.69
  5020.5  688.39  5035.5  689.08  5047.3  687.76  5047.5  687.26  5051.3  687.76
  5087.0  691.01  5099.7  693.42  5112.7  692.92  5269.4  692.64  5310.0  693.71
  5330.3  697.23  5412.4  697.29  5526.1  697.48  5586.6  697.56  5603.5  694.24
  5614.1  693.82  5647.4  700.27  5695.2  694.06  5715.5  698.36  5760.1  699.77
#Mann=13,-1,0
  4105.7     0.1       0  4269.6   0.075       0  4291.2     0.1       0
  4432.6   0.075       0  4695.8    0.05       0  4991.4   0.075       0
  5020.5    0.05       0  5047.3    0.07       0  5051.3    0.05       0
  5112.7   0.075       0  5412.4     0.1       0  5526.1   0.075       0
  5603.5    0.05       0
Bank Sta=5047.3,5051.3
Exp/Cntr=0.3,0.1

Type RM Length L Ch R = 1,52072,165,165,165
BEGIN DESCRIPTION:
Marshall Branch 75.5
END DESCRIPTION:
XS GIS Cut Line= 3
      2349933.69      7035695.07      2351088.20      7035660.35
      2351782.66      7035656.01
#Sta/Elev= 30
  3957.7  697.38  4047.3  697.33  4169.5  696.86  4203.1  697.50  4213.1  704.86
  4223.1  705.55  4233.1  704.90  4243.1  697.97  4253.1  694.71  4367.9  694.42
  4603.3  693.30  4733.4  690.75  4904.6  691.18  4922.6  690.48  4933.5  688.04
  4961.5  687.47  4961.7  686.97  4965.5  687.47  5003.5  687.50  5033.5  692.43
  5161.3  693.09  5416.9  697.00  5543.5  698.31  5593.5  694.27  5643.5  698.69
  5656.6  695.29  5673.5  693.62  5703.5  696.57  5787.8  697.34  5807.2  696.75
#Mann=12,-1,0
  3957.7   0.075       0  4047.3     0.1       0  4169.5   0.075       0
  4367.9    0.05       0  4904.6   0.075       0  4922.6    0.05       0
  4961.5   0.033       0  4965.5    0.05       0  5161.3   0.075       0
  5416.9    0.05       0  5656.6   0.075       0  5787.8    0.05       0
Bank Sta=4961.5,4965.5
Exp/Cntr=0.3,0.1

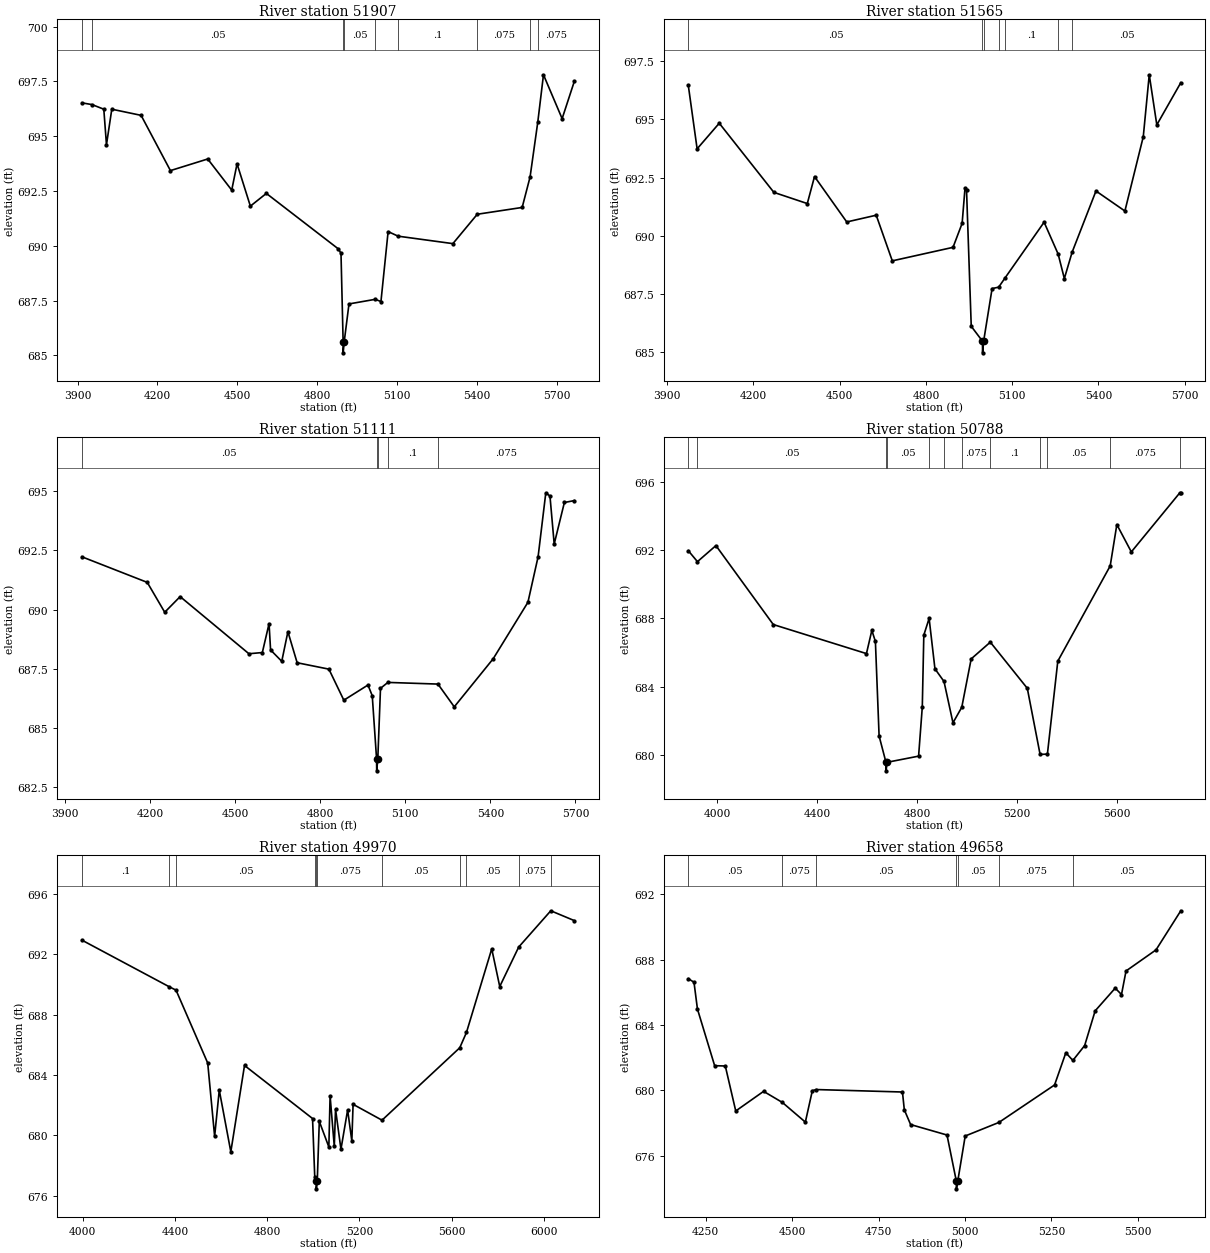
Type RM Length L Ch R = 1,51907,342,342,342
BEGIN DESCRIPTION:
Marshall Branch 75.0
END DESCRIPTION:
XS GIS Cut Line= 3
      2349946.68      7035829.62      2351101.22      7035794.90
      2351794.84      7035790.56
#Sta/Elev= 30
  3916.3  696.52  3954.7  696.44  3998.7  696.23  4008.7  694.61  4028.7  696.23
  4138.7  695.95  4248.8  693.43  4388.8  693.96  4478.9  692.54  4498.9  693.74
  4548.9  691.81  4608.9  692.39  4879.1  689.86  4889.1  689.66  4897.1  685.62
  4897.3  685.12  4901.1  685.62  4919.1  687.35  5017.4  687.56  5039.1  687.46
  5066.0  690.65  5103.5  690.44  5309.1  690.10  5400.7  691.44  5569.2  691.75
  5598.9  693.14  5627.9  695.65  5649.2  697.80  5719.2  695.80  5765.0  697.50
#Mann=9,-1,0
  3916.3   0.075       0  3954.7    0.05       0  4897.1   0.033       0
  4901.1    0.05       0  5017.4   0.075       0  5103.5     0.1       0
  5400.7   0.075       0  5598.9    0.05       0  5627.9   0.075       0
Bank Sta=4897.1,4901.1
Exp/Cntr=0.3,0.1

Type RM Length L Ch R = 1,51565,454,454,454
BEGIN DESCRIPTION:
Marshall Branch 74.0
END DESCRIPTION:
XS GIS Cut Line= 3
      2350207.15      7036415.55      2351461.46      7035990.21
      2351834.35      7035881.81
#Sta/Elev= 30
  3973.7  696.46  4004.3  693.74  4081.3  694.84  4271.3  691.87  4387.5  691.39
  4412.6  692.55  4524.7  690.60  4627.2  690.89  4683.1  688.93  4894.3  689.51
  4926.0  690.54  4936.0  692.05  4941.3  691.98  4957.7  686.12  4996.8  685.48
  4997.1  684.98  5000.8  685.48  5030.2  687.74  5053.1  687.80  5074.9  688.19
  5211.1  690.59  5260.0  689.22  5281.5  688.17  5308.5  689.30  5391.5  691.93
  5492.1  691.07  5556.0  694.26  5576.8  696.92  5603.1  694.77  5686.5  696.58
#Mann=7,-1,0
  3973.7    0.05       0  4996.8   0.033       0  5000.8    0.05       0
  5053.1   0.075       0  5074.9     0.1       0  5260.0   0.075       0
  5308.5    0.05       0
Bank Sta=4996.8,5000.8
Exp/Cntr=0.3,0.1

Type RM Length L Ch R = 1,51111,323,323,323
BEGIN DESCRIPTION:
Marshall Branch 73.0
END DESCRIPTION:
XS GIS Cut Line= 3
      2350419.84      7036884.29      2351617.71      7036376.49
      2351864.56      7036017.05
#Sta/Elev= 30
  3959.0  692.23  4189.7  691.15  4251.3  689.89  4305.7  690.55  4548.3  688.14
  4595.6  688.19  4619.3  689.41  4624.7  688.30  4664.1  687.82  4685.8  689.07
  4718.4  687.76  4830.4  687.49  4883.1  686.18  4968.2  686.82  4983.3  686.37
  4998.6  683.70  4999.0  683.20  5002.9  683.70  5012.4  686.68  5038.4  686.93
  5215.1  686.86  5272.6  685.90  5410.0  687.93  5532.4  690.31  5568.3  692.23
  5595.5  694.93  5610.2  694.79  5625.1  692.77  5661.0  694.52  5696.1  694.60
#Mann=5,-1,0
  3959.0    0.05       0  4998.6    0.05       0  5002.9    0.05       0
  5038.4     0.1       0  5215.1   0.075       0
Bank Sta=4998.6,5002.9
Exp/Cntr=0.3,0.1

Type RM Length L Ch R = 1,50788,818,818,818
BEGIN DESCRIPTION:
Marshall Branch 72.0
END DESCRIPTION:
XS GIS Cut Line= 4
      2350667.20      7037400.79      2351500.52      7036819.20
      2351856.71      7036259.48      2351921.53      7035977.17
#Sta/Elev= 30
  3884.6  691.96  3921.1  691.32  3995.0  692.26  4224.4  687.64  4596.9  685.94
  4618.5  687.30  4632.7  686.65  4647.5  681.12  4674.9  679.58  4675.4  679.08
  4679.4  679.58  4805.4  679.94  4820.2  682.81  4826.3  687.02  4847.5  688.00
  4870.8  685.05  4907.0  684.31  4942.9  681.89  4978.1  682.80  5015.7  685.63
  5092.2  686.61  5240.1  683.91  5291.3  680.04  5320.5  680.06  5362.1  685.50
  5571.6  691.07  5598.2  693.49  5656.1  691.89  5850.1  695.35  5853.9  695.31
#Mann=12,-1,0
  3884.6   0.075       0  3921.1    0.05       0  4674.9    0.07       0
  4679.4    0.05       0  4847.5   0.075       0  4907.0    0.05       0
  4978.1   0.075       0  5092.2     0.1       0  5291.3   0.075       0
  5320.5    0.05       0  5571.6   0.075       0  5850.1    0.05       0
Bank Sta=4674.9,4679.4
Exp/Cntr=0.3,0.1

Type RM Length L Ch R = 1,49970,312,312,312
BEGIN DESCRIPTION:
Marshall Branch 71.0
END DESCRIPTION:
XS GIS Cut Line= 4
      2352234.03      7038034.51      2352286.11      7037296.63
      2351917.19      7036437.26      2351947.57      7035977.19
#Sta/Elev= 30
  3996.2  692.92  4373.3  689.85  4404.7  689.61  4542.1  684.79  4572.1  679.94
  4592.2  683.00  4642.3  678.92  4701.7  684.63  4996.8  681.12  5006.4  677.23
  5012.7  676.97  5013.1  676.47  5017.2  676.97  5026.1  680.93  5067.5  679.24
  5072.9  682.61  5091.1  679.28  5096.5  681.73  5120.0  679.09  5149.0  681.69
  5167.2  679.63  5172.6  682.06  5298.1  681.01  5635.3  685.80  5664.3  686.81
  5774.0  692.34  5808.7  689.85  5890.9  692.46  6030.1  694.86  6132.2  694.21
#Mann=11,-1,0
  3996.2     0.1       0  4373.3   0.075       0  4404.7    0.05       0
  5006.4   0.075       0  5012.7   0.033       0  5017.2   0.075       0
  5298.1    0.05       0  5635.3   0.075       0  5664.3    0.05       0
  5890.9   0.075       0  6030.1    0.05       0
Bank Sta=5012.7,5017.2
Exp/Cntr=0.3,0.1

Type RM Length L Ch R = 1,49658,719,719,719
BEGIN DESCRIPTION:
Marshall Branch 70.0
END DESCRIPTION:
XS GIS Cut Line= 3
      2352515.13      7037636.28      2352563.89      7037196.81
      2352177.81      7036294.50
#Sta/Elev= 30
  4200.2  686.83  4216.6  686.61  4226.6  684.97  4276.3  681.51  4307.1  681.49
  4337.3  678.74  4417.8  679.94  4472.2  679.26  4538.5  678.06  4558.7  679.98
  4570.3  680.05  4819.2  679.90  4824.6  678.81  4842.8  677.91  4948.0  677.27
  4974.7  674.48  4975.2  673.98  4979.3  674.48  5000.6  677.21  5098.0  678.04
  5258.9  680.33  5291.5  682.30  5311.8  681.83  5345.9  682.74  5376.2  684.86
  5434.2  686.25  5452.4  685.86  5465.5  687.30  5552.2  688.59  5623.8  690.98
#Mann=7,-1,0
  4200.2    0.05       0  4472.2   0.075       0  4570.3    0.05       0
  4974.7   0.033       0  4979.3    0.05       0  5098.0   0.075       0
  5311.8    0.05       0
Bank Sta=4974.7,4979.3
Exp/Cntr=0.3,0.1

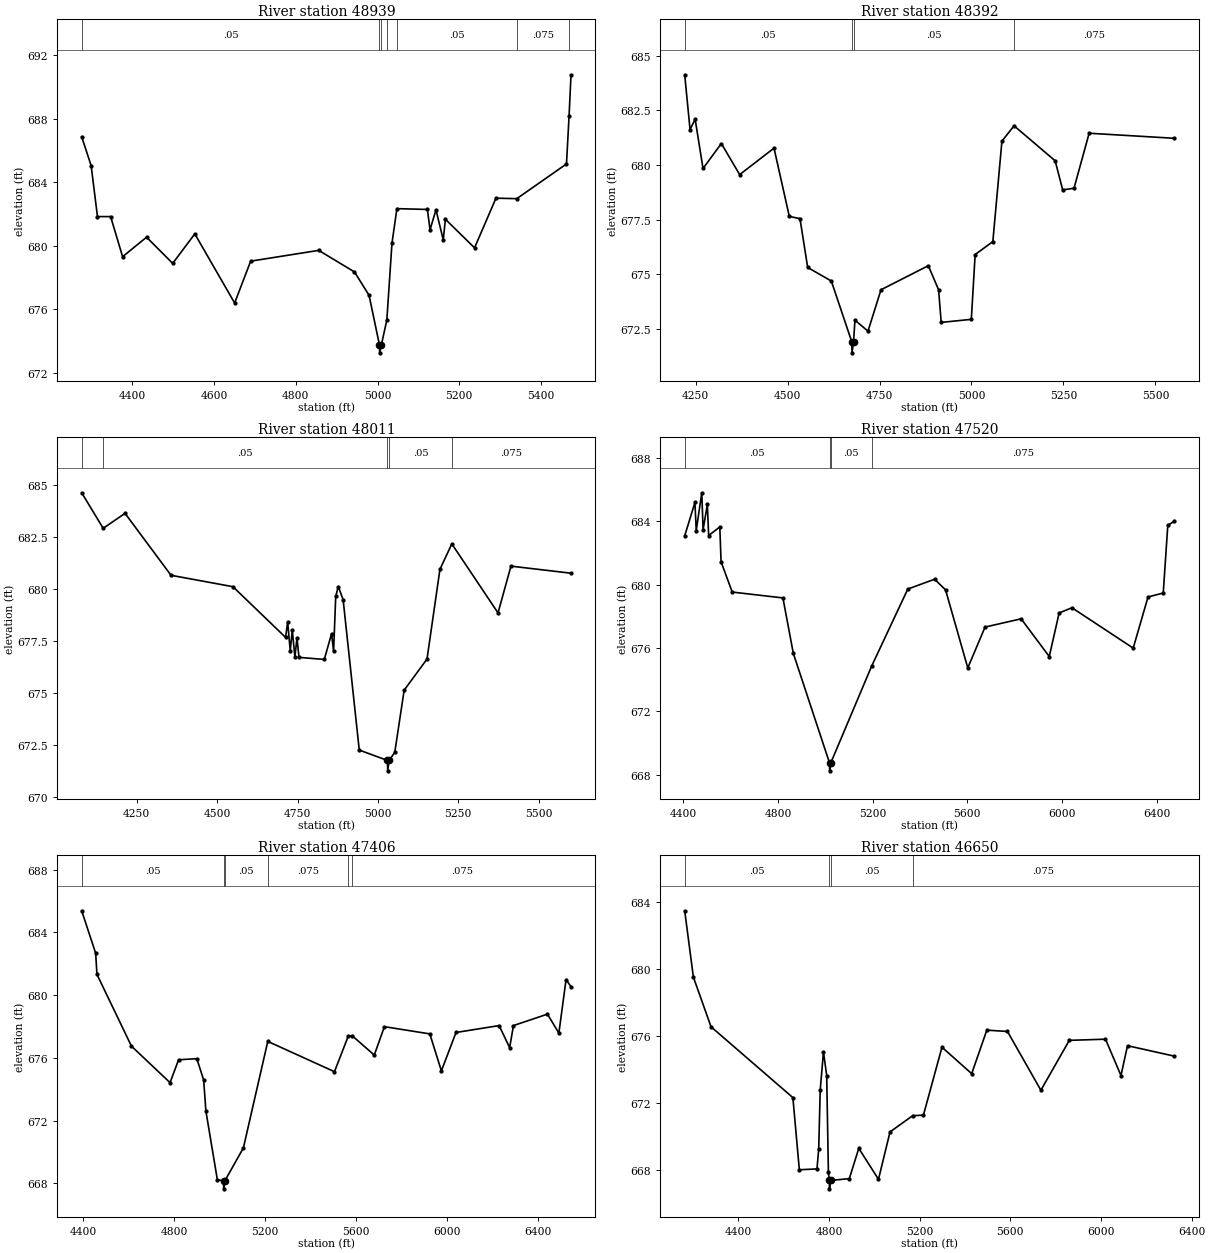
Type RM Length L Ch R = 1,48939,547,547,547
BEGIN DESCRIPTION:
Marshall Branch 69.0
END DESCRIPTION:
XS GIS Cut Line= 4
      2352524.83      7037655.63      2352749.98      7037113.81
      2352874.78      7036953.65      2352997.46      7036564.82
#Sta/Elev= 30
  4276.0  686.86  4299.1  685.04  4314.6  681.83  4346.8  681.83  4376.1  679.30
  4434.7  680.53  4498.7  678.88  4552.8  680.74  4650.3  676.38  4689.5  679.02
  4856.0  679.70  4943.6  678.34  4979.2  676.87  5004.7  673.74  5005.2  673.24
  5009.4  673.74  5022.8  675.32  5035.3  680.15  5047.4  682.33  5122.0  682.28
  5128.5  681.00  5143.0  682.26  5160.8  680.36  5166.1  681.66  5237.4  679.86
  5289.8  682.99  5340.8  682.96  5462.4  685.15  5468.7  688.17  5473.5  690.77
#Mann=7,-1,0
  4276.0    0.05       0  5004.7   0.033       0  5009.4    0.05       0
  5022.8    0.12       0  5047.4    0.05       0  5340.8   0.075       0
  5468.7    0.05       0
Bank Sta=5004.7,5009.4
Exp/Cntr=0.3,0.1

Type RM Length L Ch R = 1,48392,381,381,381
BEGIN DESCRIPTION:
Marshall Branch 68.0
END DESCRIPTION:
XS GIS Cut Line= 4
      2352546.52      7037656.89      2353093.40      7037235.87
      2353275.70      7037183.78      2353379.85      7036745.45
#Sta/Elev= 30
  4220.4  684.12  4234.9  681.62  4248.8  682.09  4270.2  679.84  4320.0  680.98
  4369.8  679.56  4463.2  680.77  4504.8  677.65  4533.8  677.55  4554.7  675.32
  4619.0  674.70  4674.7  671.92  4675.2  671.42  4679.4  671.92  4683.3  672.91
  4718.7  672.41  4754.0  674.30  4882.7  675.40  4910.6  674.30  4917.7  672.81
  4999.6  672.95  5010.0  675.91  5058.1  676.50  5082.8  681.09  5115.8  681.79
  5227.6  680.19  5248.0  678.86  5278.8  678.94  5319.9  681.45  5550.7  681.22
#Mann=4,-1,0
  4220.4    0.05       0  4674.7   0.033       0  4679.4    0.05       0
  5115.8   0.075       0
Bank Sta=4674.7,4679.4
Exp/Cntr=0.3,0.1

Type RM Length L Ch R = 1,48011,491,491,491
BEGIN DESCRIPTION:
Marshall Branch 67.0
END DESCRIPTION:
XS GIS Cut Line= 3
      2352872.06      7038112.59      2353366.84      7037478.92
      2353427.52      7036763.85
#Sta/Elev= 30
  4078.9  684.62  4145.7  682.91  4213.7  683.63  4356.6  680.65  4549.3  680.10
  4713.0  677.66  4719.3  678.41  4727.4  677.02  4733.8  678.00  4741.9  676.71
  4748.3  677.64  4754.6  676.70  4833.3  676.60  4855.9  677.84  4862.2  676.99
  4868.8  679.63  4876.7  680.11  4891.8  679.48  4942.0  672.24  5029.7  671.74
  5030.4  671.24  5035.0  671.74  5052.4  672.13  5081.6  675.12  5152.7  676.62
  5192.9  680.94  5229.8  682.16  5373.5  678.84  5413.7  681.09  5600.5  680.75
#Mann=5,-1,0
  4078.9   0.075       0  4145.7    0.05       0  5029.7   0.033       0
  5035.0    0.05       0  5229.8   0.075       0
Bank Sta=5029.7,5035
Exp/Cntr=0.3,0.1

Type RM Length L Ch R = 1,47520,114,114,114
BEGIN DESCRIPTION:
Marshall Branch 66.2
END DESCRIPTION:
XS GIS Cut Line= 6
      2353188.93      7038004.08      2353562.15      7037843.51
      2353623.59      7037561.64      2353706.44      7037396.99
      2353870.31      7037257.57      2354148.01      7036324.69
#Sta/Elev= 30
  4406.0  683.08  4449.2  685.19  4454.7  683.41  4478.2  685.80  4483.7  683.47
  4501.7  685.06  4507.2  683.10  4554.3  683.64  4559.7  681.44  4606.8  679.53
  4821.0  679.16  4864.9  675.66  5017.9  668.74  5018.7  668.24  5023.2  668.74
  5196.1  674.86  5348.7  679.72  5461.8  680.34  5508.1  679.67  5602.1  674.74
  5675.1  677.32  5827.5  677.84  5946.4  675.46  5988.1  678.21  6042.2  678.54
  6301.1  675.99  6363.7  679.22  6428.0  679.47  6447.2  683.74  6473.6  683.99
#Mann=4,-1,0
  4406.0    0.05       0  5017.9   0.033       0  5023.2    0.05       0
  5196.1   0.075       0
Bank Sta=5017.9,5023.2
Exp/Cntr=0.3,0.1

Type RM Length L Ch R = 1,47406,756,756,756
BEGIN DESCRIPTION:
Marshall Branch 66.0
END DESCRIPTION:
XS GIS Cut Line= 6
      2353328.99      7038060.01      2353688.02      7037904.27
      2353701.71      7037626.74      2353784.57      7037462.09
      2354065.17      7037269.93      2354356.43      7036359.10
#Sta/Elev= 30
  4394.6  685.38  4456.0  682.67  4461.5  681.33  4613.1  676.75  4782.8  674.42
  4820.3  675.88  4900.4  675.95  4930.4  674.59  4940.4  672.60  4990.5  668.24
  5017.9  668.15  5018.6  667.65  5023.2  668.15  5105.0  670.26  5212.2  677.05
  5505.2  675.12  5565.8  677.39  5583.0  677.41  5680.1  676.18  5724.6  677.99
  5924.1  677.53  5974.9  675.17  6039.2  677.62  6228.6  678.06  6274.8  676.65
  6291.6  678.06  6440.9  678.79  6491.1  677.58  6522.6  680.99  6544.5  680.54
#Mann=6,-1,0
  4394.6    0.05       0  5017.9   0.033       0  5023.2    0.05       0
  5212.2   0.075       0  5565.8    0.05       0  5583.0   0.075       0
Bank Sta=5017.9,5023.2
Exp/Cntr=0.3,0.1

Type RM Length L Ch R = 1,46650,410,410,410
BEGIN DESCRIPTION:
Marshall Branch 65.0
END DESCRIPTION:
XS GIS Cut Line= 3
      2353549.17      7038303.55      2354179.00      7037760.00
      2354811.73      7036594.29
#Sta/Elev= 30
  4163.7  683.46  4201.9  679.50  4279.8  676.53  4640.8  672.30  4669.3  667.99
  4747.2  668.04  4754.8  669.25  4761.4  672.75  4775.7  675.03  4790.0  673.62
  4797.5  667.85  4801.5  667.35  4802.3  666.85  4806.9  667.35  4889.8  667.46
  4931.5  669.27  5018.4  667.42  5069.3  670.25  5169.3  671.22  5216.6  671.25
  5298.4  675.31  5429.5  673.73  5496.3  676.33  5587.3  676.25  5734.7  672.74
  5860.1  675.72  6019.7  675.79  6087.9  673.62  6116.8  675.40  6322.0  674.78
#Mann=4,-1,0
  4163.7    0.05       0  4801.5   0.033       0  4806.9    0.05       0
  5169.3   0.075       0
Bank Sta=4801.5,4806.9
Exp/Cntr=0.3,0.1

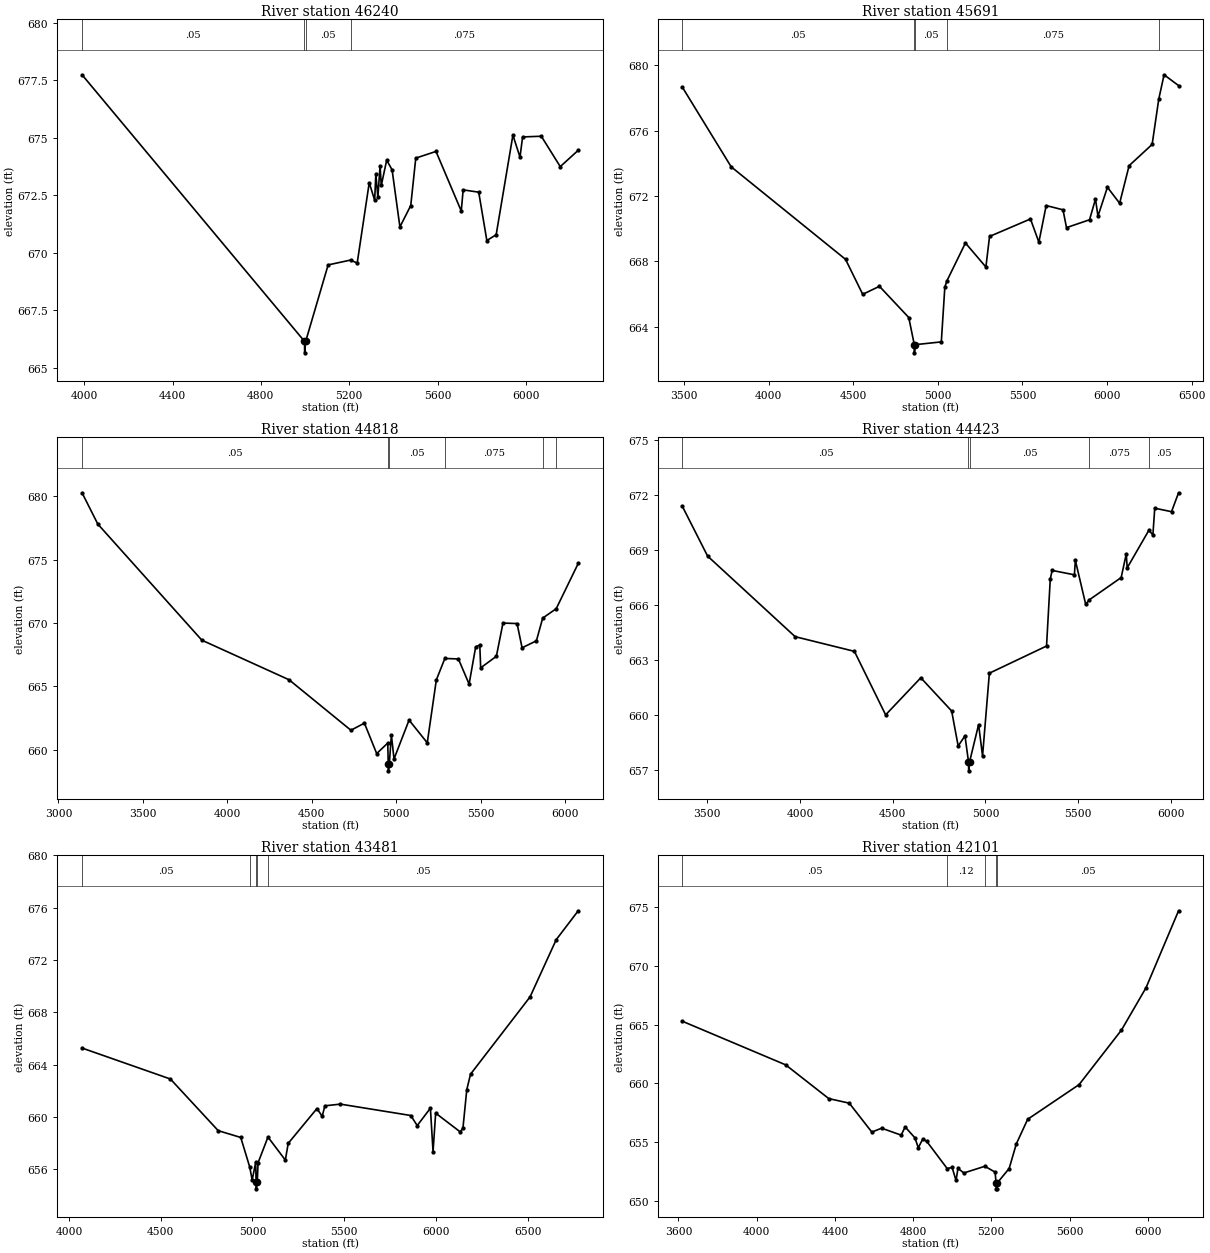
Type RM Length L Ch R = 1,46240,549,549,549
BEGIN DESCRIPTION:
Marshall Branch 64.0
END DESCRIPTION:
XS GIS Cut Line= 3
      2353557.79      7038646.47      2354412.85      7038043.16
      2354846.58      7036924.15
#Sta/Elev= 30
  3990.4  677.74  4997.6  666.16  4998.3  665.66  5003.0  666.16  5104.6  669.48
  5206.0  669.69  5236.2  669.56  5290.7  673.05  5315.3  672.29  5320.6  673.44
  5329.8  672.41  5339.8  673.79  5345.2  672.93  5369.7  674.03  5394.2  673.61
  5429.6  671.13  5478.7  672.06  5501.4  674.12  5593.0  674.41  5707.4  671.82
  5715.9  672.74  5786.4  672.64  5823.2  670.54  5865.4  670.79  5941.2  675.12
  5973.3  674.16  5985.1  675.04  6069.8  675.07  6155.6  673.75  6237.0  674.46
#Mann=4,-1,0
  3990.4    0.05       0  4997.6   0.033       0  5003.0    0.05       0
  5206.0   0.075       0
Bank Sta=4997.6,5003
Exp/Cntr=0.3,0.1

Type RM Length L Ch R = 1,45691,873,873,873
BEGIN DESCRIPTION:
Marshall Branch 63.0
END DESCRIPTION:
XS GIS Cut Line= 3
      2353579.00      7039060.00      2354690.63      7038299.24
      2355678.98      7037060.03
#Sta/Elev= 30
  3490.6  678.65  3779.1  673.78  4454.8  668.12  4556.4  665.98  4655.2  666.47
  4828.5  664.56  4861.1  662.90  4861.9  662.40  4866.5  662.90  5020.8  663.07
  5041.6  666.42  5053.3  666.79  5163.3  669.12  5284.3  667.65  5305.8  669.52
  5547.6  670.59  5597.3  669.17  5640.5  671.41  5739.8  671.15  5760.6  670.06
  5896.7  670.54  5931.9  671.81  5946.4  670.76  6002.4  672.53  6074.5  671.55
  6130.5  673.85  6266.6  675.15  6305.7  677.92  6337.1  679.41  6422.7  678.75
#Mann=5,-1,0
  3490.6    0.05       0  4861.1   0.033       0  4866.5    0.05       0
  5053.3   0.075       0  6305.7    0.05       0
Bank Sta=4861.1,4866.5
Exp/Cntr=0.3,0.1

Type RM Length L Ch R = 1,44818,395,395,395
BEGIN DESCRIPTION:
Marshall Branch 62.0
END DESCRIPTION:
XS GIS Cut Line= 3
      2353679.01      7039409.99      2355279.00      7038460.00
      2355679.00      7037460.00
#Sta/Elev= 30
  3139.6  680.27  3233.1  677.80  3848.9  668.65  4365.2  665.53  4731.5  661.55
  4811.4  662.11  4884.1  659.71  4949.7  660.54  4952.5  658.85  4953.5  658.35
  4958.5  658.85  4971.1  661.17  4986.7  659.29  5075.8  662.35  5183.5  660.56
  5237.3  665.52  5287.7  667.21  5367.9  667.17  5431.2  665.19  5470.2  668.12
  5494.5  668.27  5499.8  666.47  5592.7  667.38  5631.8  670.00  5715.2  669.96
  5744.9  668.05  5829.7  668.60  5866.9  670.39  5946.9  671.13  6077.4  674.70
#Mann=6,-1,0
  3139.6    0.05       0  4952.5   0.033       0  4958.5    0.05       0
  5287.7   0.075       0  5866.9    0.05       0  5946.9   0.075       0
Bank Sta=4952.5,4958.5
Exp/Cntr=0.3,0.1

Type RM Length L Ch R = 1,44423,942,942,942
BEGIN DESCRIPTION:
Marshall Branch 61.0
END DESCRIPTION:
XS GIS Cut Line= 3
      2354200.19      7039527.53      2355797.40      7038550.97
      2355884.20      7037752.37
#Sta/Elev= 30
  3365.6  671.39  3501.8  668.68  3973.7  664.29  4293.3  663.49  4461.6  660.03
  4651.3  662.05  4817.6  660.24  4852.8  658.33  4889.4  658.89  4908.4  657.48
  4909.4  656.98  4914.4  657.48  4962.9  659.50  4984.2  657.79  5020.9  662.30
  5329.2  663.78  5349.3  667.43  5359.4  667.90  5479.5  667.66  5484.5  668.45
  5540.4  666.05  5560.1  666.30  5731.6  667.51  5759.1  668.80  5764.1  668.04
  5881.2  670.09  5902.6  669.83  5912.6  671.29  6003.1  671.10  6041.0  672.13
#Mann=5,-1,0
  3365.6    0.05       0  4908.4   0.033       0  4914.4    0.05       0
  5560.1   0.075       0  5881.2    0.05       0
Bank Sta=4908.4,4914.4
Exp/Cntr=0.3,0.1

Type RM Length L Ch R = 1,43481,1380,1380,1380
BEGIN DESCRIPTION:
Marshall Branch 60.0
END DESCRIPTION:
XS GIS Cut Line= 4
      2354655.88      7039666.43      2355706.25      7039288.82
      2356485.66      7038657.20      2356824.99      7038179.19
#Sta/Elev= 30
  4070.9  665.26  4552.9  662.89  4813.4  658.94  4936.3  658.42  4985.2  656.16
  4998.7  655.17  5017.8  656.52  5020.1  654.99  5021.1  654.49  5026.3  654.99
  5030.6  656.48  5084.7  658.45  5179.4  656.69  5195.1  657.97  5351.7  660.63
  5380.5  660.04  5394.9  660.84  5479.6  660.97  5863.3  660.10  5898.5  659.33
  5970.4  660.66  5984.8  657.33  5999.1  660.28  6133.5  658.84  6147.8  659.13
  6168.8  662.08  6189.2  663.26  6513.7  669.17  6656.4  673.55  6776.5  675.76
#Mann=5,-1,0
  4070.9    0.05       0  4985.2    0.12       0  5020.1    0.07       0
  5026.3    0.12       0  5084.7    0.05       0
Bank Sta=5020.1,5026.3
Exp/Cntr=0.3,0.1

Type RM Length L Ch R = 1,42101,784,784,784
BEGIN DESCRIPTION:
Marshall Branch 59.0
END DESCRIPTION:
XS GIS Cut Line= 3
      2354751.43      7039853.05      2356214.06      7039770.59
      2357129.02      7039209.99
#Sta/Elev= 30
  3619.8  665.29  4148.2  661.58  4368.6  658.71  4473.6  658.32  4588.9  655.86
  4639.0  656.19  4739.1  655.60  4759.2  656.30  4809.3  655.37  4826.5  654.53
  4849.3  655.26  4869.4  655.08  4974.2  652.76  4999.6  652.85  5019.6  651.74
  5029.6  652.77  5059.7  652.38  5167.1  652.95  5219.6  652.45  5224.3  651.53
  5225.3  651.03  5229.5  651.03  5230.5  651.53  5291.3  652.76  5328.1  654.86
  5386.1  656.95  5649.1  659.90  5865.8  664.54  5991.4  668.14  6157.8  674.69
#Mann=5,-1,0
  3619.8    0.05       0  4974.2    0.12       0  5167.1    0.05       0
  5224.3    0.07       0  5230.5    0.05       0
Bank Sta=5224.3,5230.5
Exp/Cntr=0.3,0.1