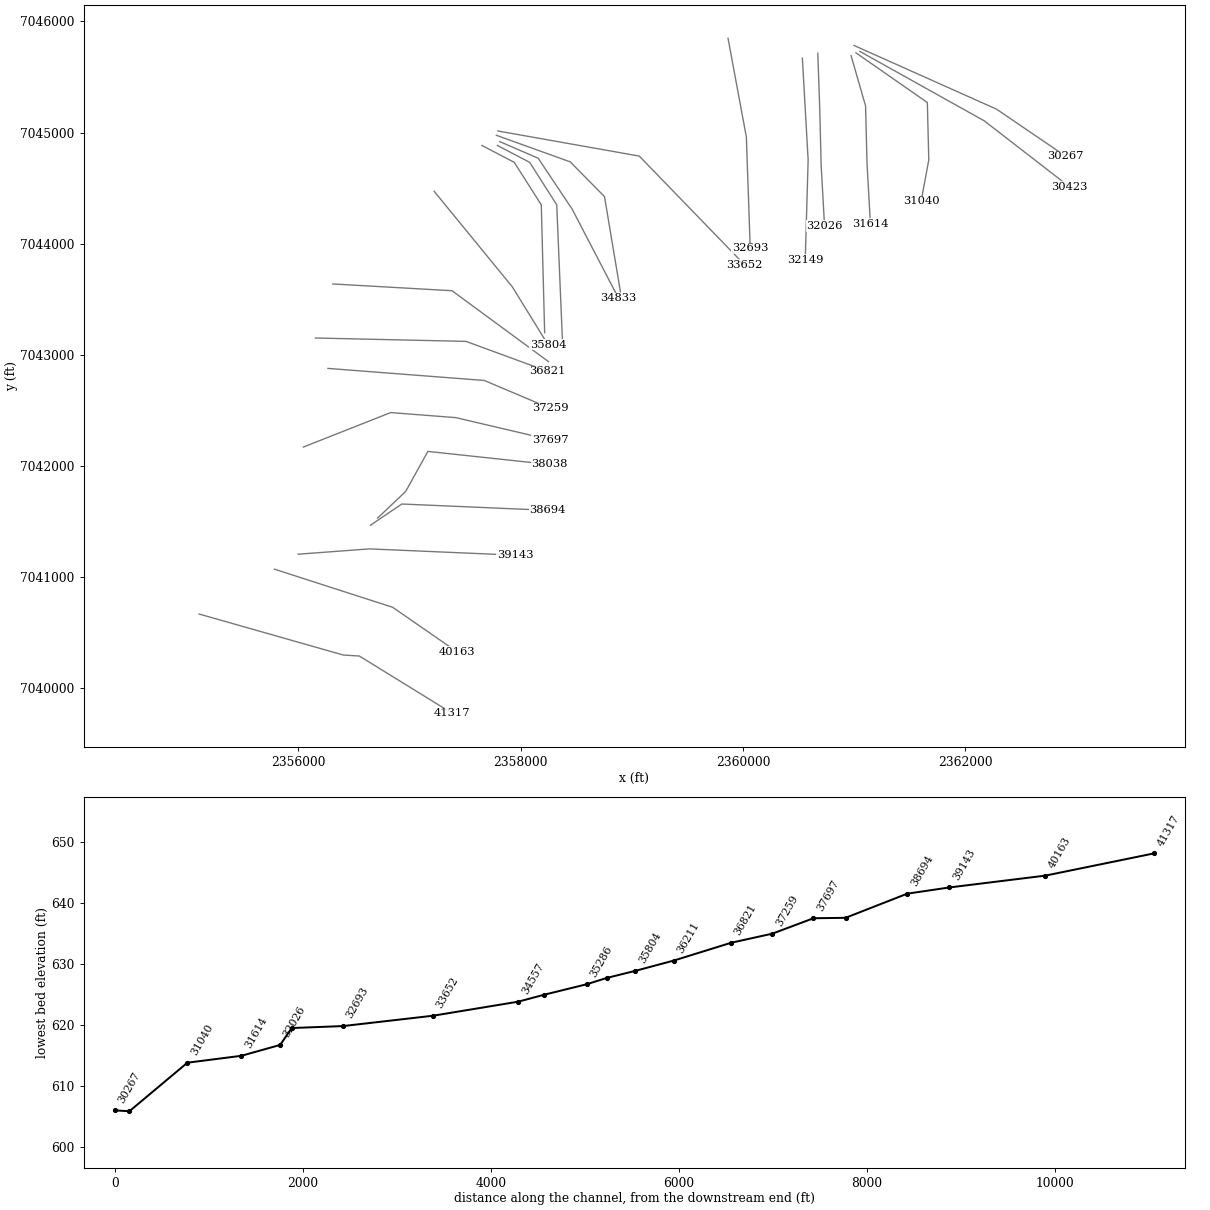
HEC-RAS study Marshall Branch.prj: Marshall Branch Base Level Engineering

--- Marshall Branch.g01 (geometry) --- (continued)

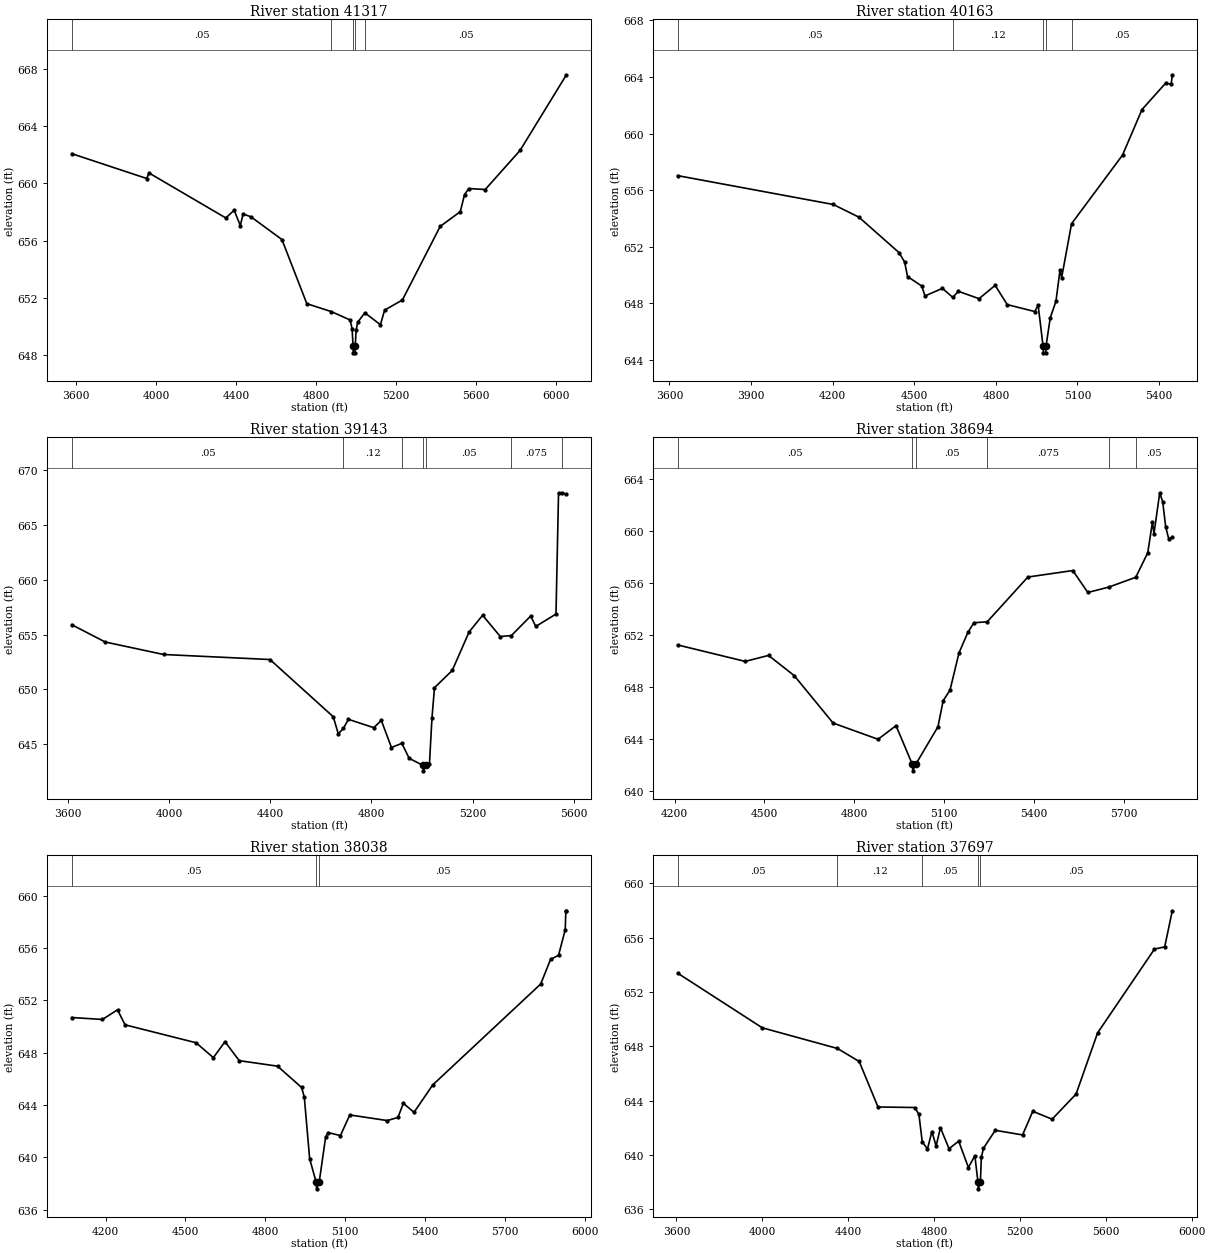
Type RM Length L Ch R = 1,41317,1154,1154,1154
BEGIN DESCRIPTION:
Marshall Branch 58.0
END DESCRIPTION:
XS GIS Cut Line= 4
      2355107.32      7040669.02      2356405.04      7040300.10
      2356548.27      7040291.42      2357384.89      7039775.58
#Sta/Elev= 30
  3576.8  662.08  3952.4  660.34  3963.2  660.73  4347.9  657.58  4389.5  658.12
  4420.6  657.05  4434.4  657.86  4473.5  657.66  4628.6  656.07  4753.3  651.58
  4875.1  651.03  4970.0  650.44  4980.0  649.81  4984.5  648.64  4986.0  648.14
  4994.0  648.14  4995.6  648.64  5000.0  649.73  5007.7  650.28  5043.6  650.94
  5121.5  650.11  5142.7  651.13  5231.5  651.84  5420.7  656.99  5521.2  658.02
  5542.5  659.22  5563.8  659.64  5645.9  659.57  5820.5  662.31  6052.3  667.60
#Mann=5,-1,0
  3576.8    0.05       0  4875.1    0.12       0  4984.5    0.07       0
  4995.6    0.12       0  5043.6    0.05       0
Bank Sta=4984.5,4995.6
Exp/Cntr=0.3,0.1

Type RM Length L Ch R = 1,40163,1020,1020,1020
BEGIN DESCRIPTION:
Marshall Branch 57.0
END DESCRIPTION:
XS GIS Cut Line= 3
      2355784.35      7041072.68      2356847.75      7040729.79
      2357424.49      7040330.84
#Sta/Elev= 30
  3629.9  657.03  4202.2  654.99  4296.7  654.09  4443.8  651.59  4464.6  650.92
  4475.3  649.89  4527.9  649.22  4539.2  648.52  4603.3  649.06  4641.5  648.42
  4662.1  648.85  4738.0  648.33  4797.4  649.27  4841.7  647.91  4943.1  647.42
  4955.4  647.87  4973.3  645.00  4974.9  644.50  4983.0  644.50  4984.5  645.00
  4999.9  646.98  5020.8  648.14  5035.7  650.35  5041.8  649.82  5078.2  653.63
  5265.5  658.48  5337.1  661.70  5423.6  663.56  5444.5  663.50  5448.5  664.16
#Mann=5,-1,0
  3629.9    0.05       0  4641.5    0.12       0  4973.3    0.07       0
  4984.5    0.12       0  5078.2    0.05       0
Bank Sta=4973.3,4984.5
Exp/Cntr=0.3,0.1

Type RM Length L Ch R = 1,39143,449,449,449
BEGIN DESCRIPTION:
Marshall Branch 56.5
END DESCRIPTION:
XS GIS Cut Line= 3
      2355997.00      7041207.22      2356639.41      7041254.97
      2357950.22      7041198.54
#Sta/Elev= 30
  3614.8  655.90  3747.2  654.32  3977.8  653.18  4398.7  652.72  4648.9  647.50
  4668.9  645.94  4689.0  646.43  4709.0  647.26  4809.1  646.50  4839.1  647.16
  4879.1  644.69  4920.2  645.07  4949.2  643.70  5003.6  643.06  5005.2  642.56
  5014.9  643.06  5029.3  643.16  5039.3  647.38  5049.3  650.15  5119.4  651.72
  5186.3  655.24  5239.5  656.76  5309.5  654.82  5353.4  654.91  5429.7  656.69
  5449.7  655.74  5529.7  656.87  5539.8  667.92  5552.0  667.94  5571.0  667.81
#Mann=7,-1,0
  3614.8    0.05       0  4689.0    0.12       0  4920.2    0.05       0
  5003.6   0.033       0  5014.9    0.05       0  5353.4   0.075       0
  5552.0     0.1       0
Bank Sta=5003.6,5014.9
Exp/Cntr=0.3,0.1

Type RM Length L Ch R = 1,38694,656,656,656
BEGIN DESCRIPTION:
Marshall Branch 56.0
END DESCRIPTION:
XS GIS Cut Line= 3
      2356648.12      7041467.65      2356930.21      7041658.61
      2358240.95      7041602.19
#Sta/Elev= 30
  4210.2  651.24  4436.0  649.97  4514.0  650.43  4599.7  648.88  4729.8  645.22
  4879.9  643.97  4940.0  645.02  4994.4  642.04  4996.0  641.54  5005.7  642.04
  5080.1  644.94  5097.5  646.95  5120.2  647.75  5150.2  650.62  5180.2  652.22
  5200.2  652.95  5244.5  653.02  5380.4  656.47  5530.5  656.97  5580.6  655.28
  5650.2  655.69  5740.8  656.45  5780.8  658.34  5796.6  660.71  5801.6  659.80
  5820.8  662.96  5830.8  662.26  5840.8  660.33  5850.8  659.42  5862.8  659.53
#Mann=6,-1,0
  4210.2    0.05       0  4994.4   0.033       0  5005.7    0.05       0
  5244.5   0.075       0  5650.2     0.1       0  5740.8    0.05       0
Bank Sta=4994.4,5005.7
Exp/Cntr=0.3,0.1

Type RM Length L Ch R = 1,38038,341,341,341
BEGIN DESCRIPTION:
Marshall Branch 55.0
END DESCRIPTION:
XS GIS Cut Line= 4
      2356713.16      7041532.71      2356964.93      7041771.46
      2357164.59      7042131.70      2358258.38      7042014.51
#Sta/Elev= 30
  4072.9  650.68  4188.4  650.53  4245.0  651.27  4273.3  650.12  4540.0  648.75
  4605.2  647.61  4648.7  648.83  4702.5  647.38  4846.2  646.96  4936.8  645.33
  4946.8  644.60  4966.9  639.89  4991.4  638.08  4993.0  637.58  5002.7  638.08
  5027.3  641.57  5037.3  641.88  5082.5  641.65  5117.8  643.23  5258.6  642.80
  5298.8  643.04  5318.9  644.12  5359.1  643.43  5429.6  645.53  5835.1  653.24
  5872.1  655.12  5902.2  655.44  5927.3  657.39  5929.6  658.84  5931.8  658.84
#Mann=3,-1,0
  4072.9    0.05       0  4991.4   0.033       0  5002.7    0.05       0
Bank Sta=4991.4,5002.7
Exp/Cntr=0.3,0.1

Type RM Length L Ch R = 1,37697,438,438,438
BEGIN DESCRIPTION:
Marshall Branch 54.0
END DESCRIPTION:
XS GIS Cut Line= 4
      2356044.80      7042170.76      2356829.53      7042480.95
      2357416.32      7042435.52      2358265.49      7042236.23
#Sta/Elev= 30
  3605.2  653.40  3999.9  649.37  4349.7  647.85  4451.3  646.89  4538.8  643.54
  4709.3  643.50  4729.3  643.01  4745.1  640.96  4769.4  640.45  4789.9  641.73
  4809.6  640.66  4829.6  642.01  4869.7  640.47  4914.8  641.02  4960.0  639.08
  4990.1  639.95  5004.5  638.01  5006.1  637.51  5015.9  638.01  5020.2  639.82
  5030.2  640.50  5085.1  641.82  5212.4  641.48  5259.9  643.22  5349.9  642.64
  5461.5  644.49  5562.0  649.00  5826.9  655.17  5874.4  655.33  5909.8  657.99
#Mann=5,-1,0
  3605.2    0.05       0  4349.7    0.12       0  4745.1    0.05       0
  5004.5   0.033       0  5015.9    0.05       0
Bank Sta=5004.5,5015.9
Exp/Cntr=0.3,0.1

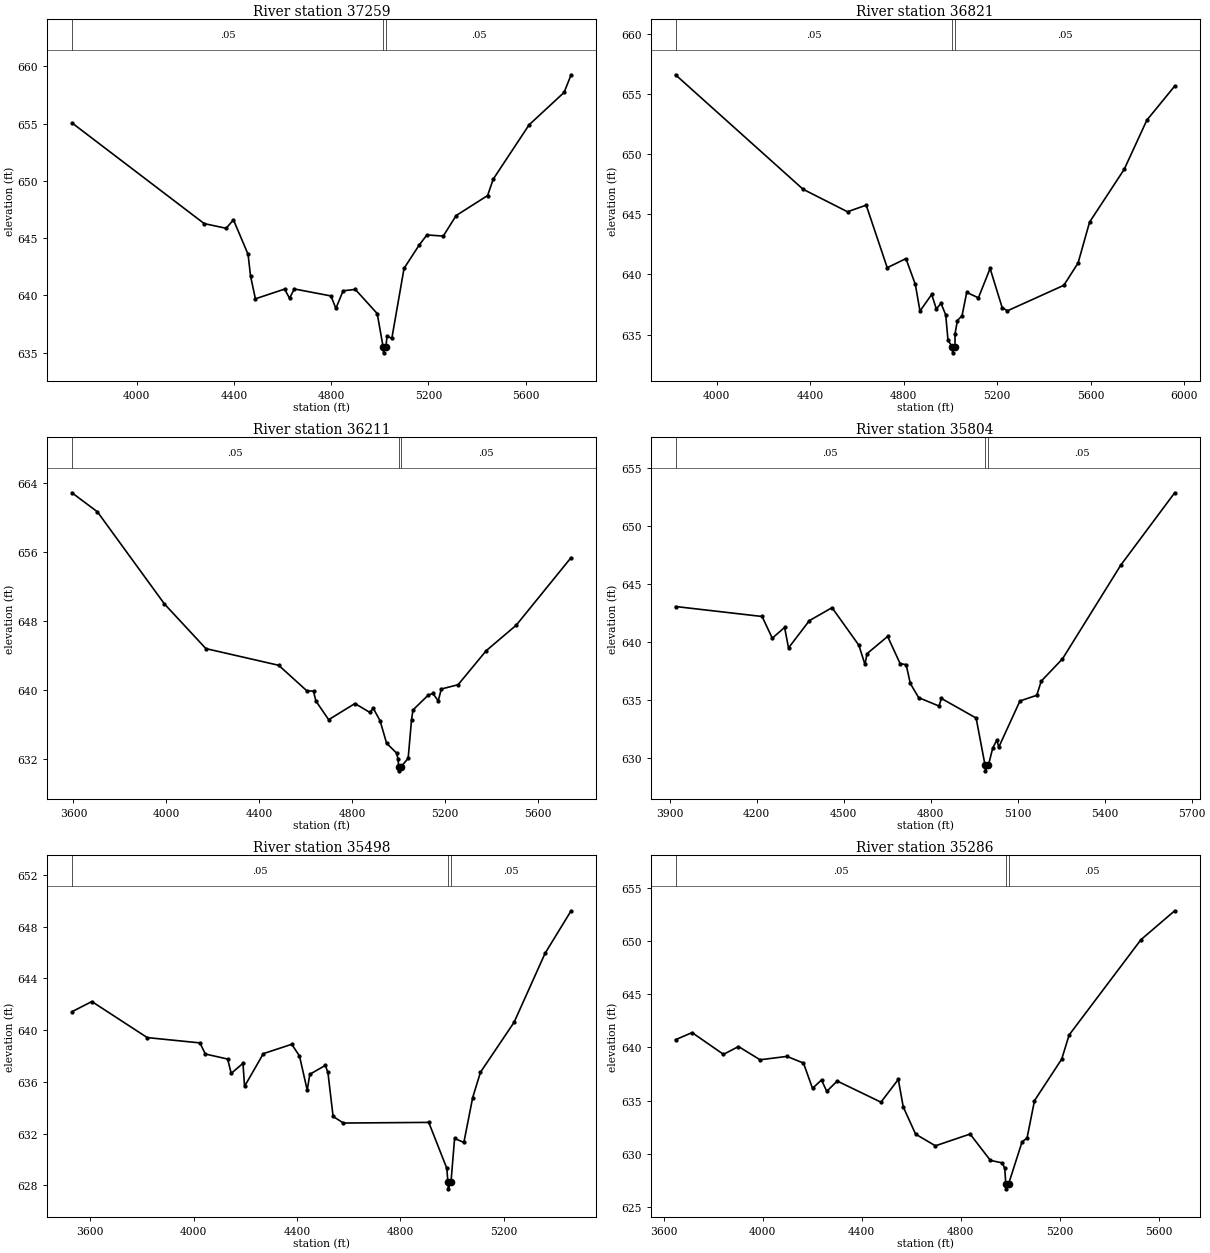
Type RM Length L Ch R = 1,37259,438,438,438
BEGIN DESCRIPTION:
Marshall Branch 53.0
END DESCRIPTION:
XS GIS Cut Line= 3
      2356266.18      7042878.23      2357672.40      7042769.72
      2358265.53      7042518.61
#Sta/Elev= 30
  3733.2  655.07  4277.6  646.27  4367.9  645.86  4398.0  646.60  4458.2  643.58
  4468.2  641.70  4488.3  639.70  4608.6  640.55  4628.7  639.75  4648.7  640.56
  4799.2  639.95  4819.6  638.86  4849.3  640.40  4899.5  640.52  4989.7  638.41
  5014.1  635.48  5015.7  634.98  5025.5  635.48  5029.9  636.43  5049.9  636.25
  5100.1  642.36  5161.6  644.37  5194.2  645.28  5261.6  645.18  5314.4  646.97
  5444.0  648.72  5467.3  650.16  5614.9  654.90  5758.9  657.73  5787.7  659.27
#Mann=3,-1,0
  3733.2    0.05       0  5014.1    0.04       0  5025.5    0.05       0
Bank Sta=5014.1,5025.5
Exp/Cntr=0.3,0.1

Type RM Length L Ch R = 1,36821,610,610,610
BEGIN DESCRIPTION:
Marshall Branch 52.0
END DESCRIPTION:
XS GIS Cut Line= 3
      2356153.30      7043151.67      2357507.47      7043121.28
      2358240.96      7042852.19
#Sta/Elev= 30
  3824.1  656.59  4369.9  647.08  4560.0  645.21  4640.0  645.76  4730.0  640.56
  4810.0  641.32  4850.1  639.18  4870.1  636.96  4920.1  638.34  4940.1  637.14
  4960.1  637.60  4980.1  636.65  4990.1  634.53  5008.1  633.99  5009.8  633.49
  5019.9  633.99  5020.1  635.07  5030.1  636.17  5050.1  636.58  5070.1  638.51
  5120.1  638.06  5170.1  640.50  5221.7  637.25  5244.1  636.98  5485.5  639.10
  5546.5  640.95  5595.7  644.35  5744.0  648.74  5840.8  652.82  5959.9  655.65
#Mann=3,-1,0
  3824.1    0.05       0  5008.1   0.033       0  5019.9    0.05       0
Bank Sta=5008.1,5019.9
Exp/Cntr=0.3,0.1

Type RM Length L Ch R = 1,36211,407,407,407
BEGIN DESCRIPTION:
Marshall Branch 51.0
END DESCRIPTION:
XS GIS Cut Line= 3
      2356309.53      7043637.78      2357381.60      7043577.01
      2358249.66      7042938.99
#Sta/Elev= 30
  3593.6  662.92  3703.2  660.71  3992.4  649.98  4170.9  644.79  4484.5  642.85
  4604.7  639.91  4634.7  639.83  4644.8  638.70  4699.9  636.52  4813.1  638.40
  4877.4  637.37  4892.0  637.85  4921.3  636.41  4949.6  633.78  4992.3  632.65
  4999.3  631.91  5001.1  631.07  5002.7  630.57  5012.9  631.07  5042.5  632.03
  5057.1  636.53  5063.3  637.65  5128.1  639.36  5149.0  639.58  5172.1  638.71
  5185.4  640.09  5257.7  640.59  5378.9  644.55  5508.1  647.51  5744.7  655.38
#Mann=3,-1,0
  3593.6    0.05       0  5001.1    0.04       0  5012.9    0.05       0
Bank Sta=5001.1,5012.9
Exp/Cntr=0.3,0.1

Type RM Length L Ch R = 1,35804,306,306,306
BEGIN DESCRIPTION:
Marshall Branch 50.0
END DESCRIPTION:
XS GIS Cut Line= 3
      2357221.01      7044471.11      2357924.13      7043611.74
      2358244.65      7043091.98
#Sta/Elev= 30
  3920.5  643.05  4219.0  642.19  4254.1  640.32  4296.6  641.25  4310.1  639.48
  4381.9  641.83  4460.1  642.95  4552.7  639.71  4573.6  638.06  4580.9  638.99
  4651.8  640.47  4694.9  638.13  4715.7  638.04  4730.0  636.42  4758.7  635.20
  4829.1  634.47  4837.0  635.13  4956.9  633.44  4987.6  629.39  4989.2  628.89
  4999.4  629.39  5014.3  630.86  5028.6  631.55  5034.8  630.92  5108.0  634.91
  5166.0  635.40  5181.4  636.62  5254.7  638.54  5455.8  646.62  5641.5  652.85
#Mann=3,-1,0
  3920.5    0.05       0  4987.6    0.04       0  4999.4    0.05       0
Bank Sta=4987.6,4999.4
Exp/Cntr=0.3,0.1

Type RM Length L Ch R = 1,35498,212,212,212
BEGIN DESCRIPTION:
Marshall Branch 49.6
END DESCRIPTION:
XS GIS Cut Line= 4
      2357650.71      7044883.43      2357941.50      7044731.53
      2358184.55      7044349.58      2358214.93      7043199.38
#Sta/Elev= 30
  3529.1  641.42  3606.1  642.21  3820.5  639.42  4024.2  639.01  4045.4  638.15
  4131.6  637.76  4145.3  636.65  4190.9  637.43  4197.0  635.65  4269.8  638.18
  4379.5  638.90  4409.5  638.00  4439.5  635.35  4449.5  636.58  4509.5  637.27
  4519.6  636.72  4539.6  633.32  4579.6  632.81  4909.7  632.86  4979.7  629.30
  4983.8  628.22  4985.4  627.72  4995.6  628.22  5009.7  631.62  5045.6  631.31
  5079.7  634.78  5109.8  636.74  5239.8  640.60  5359.8  645.94  5460.5  649.23
#Mann=3,-1,0
  3529.1    0.05       0  4983.8   0.033       0  4995.6    0.05       0
Bank Sta=4983.8,4995.6
Exp/Cntr=0.3,0.1

Type RM Length L Ch R = 1,35286,453,453,453
BEGIN DESCRIPTION:
Marshall Branch 49.4
END DESCRIPTION:
XS GIS Cut Line= 4
      2357789.60      7044883.43      2358080.38      7044731.53
      2358323.44      7044349.58      2358375.47      7043113.77
#Sta/Elev= 30
  3647.2  640.73  3714.2  641.40  3841.1  639.35  3901.7  640.09  3988.9  638.84
  4097.7  639.16  4164.5  638.53  4200.9  636.15  4237.3  636.94  4258.5  635.87
  4300.8  636.84  4477.6  634.85  4547.7  636.99  4567.7  634.40  4617.7  631.84
  4697.8  630.74  4837.9  631.85  4919.9  629.37  4968.1  629.13  4978.1  628.61
  4982.1  627.19  4983.8  626.69  4994.0  627.19  5048.1  631.12  5068.1  631.47
  5098.2  634.99  5208.3  638.91  5238.3  641.18  5528.6  650.15  5664.9  652.87
#Mann=3,-1,0
  3647.2    0.05       0  4982.1    0.05       0  4994.0    0.05       0
Bank Sta=4982.1,4994
Exp/Cntr=0.3,0.1

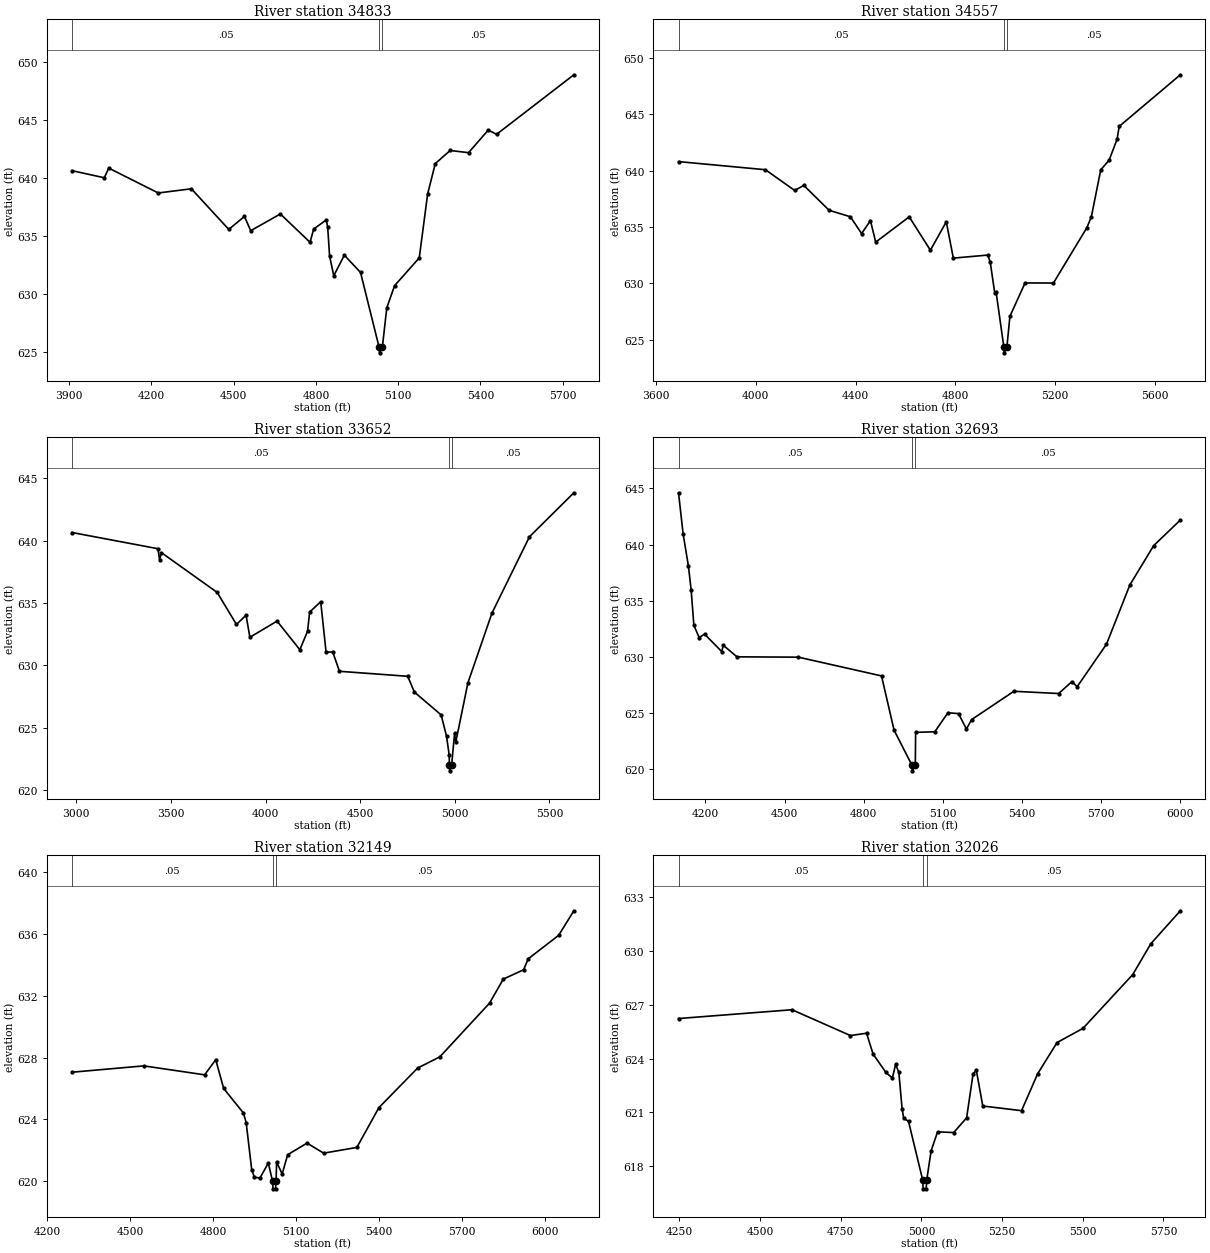
Type RM Length L Ch R = 1,34833,276,276,276
BEGIN DESCRIPTION:
Marshall Branch 49.0
END DESCRIPTION:
XS GIS Cut Line= 4
      2357811.24      7044918.18      2358157.17      7044768.25
      2358462.33      7044310.52      2358878.99      7043510.02
#Sta/Elev= 30
  3911.0  640.66  4028.4  640.05  4044.8  640.88  4225.4  638.74  4346.0  639.10
  4482.4  635.60  4539.5  636.72  4562.3  635.49  4670.5  636.93  4778.7  634.49
  4791.9  635.63  4838.1  636.42  4843.1  635.78  4850.0  633.30  4865.2  631.61
  4903.7  633.38  4962.7  631.90  5030.3  625.47  5032.0  624.97  5042.4  625.47
  5058.5  628.84  5086.8  630.75  5176.9  633.15  5207.5  638.66  5235.3  641.27
  5289.7  642.40  5356.6  642.21  5428.6  644.16  5458.8  643.79  5740.6  648.92
#Mann=3,-1,0
  3911.0    0.05       0  5030.3    0.04       0  5042.4    0.05       0
Bank Sta=5030.3,5042.4
Exp/Cntr=0.3,0.1

Type RM Length L Ch R = 1,34557,905,905,905
BEGIN DESCRIPTION:
Marshall Branch 48.0
END DESCRIPTION:
XS GIS Cut Line= 4
      2357780.92      7044974.58      2358444.97      7044735.87
      2358753.13      7044423.37      2358896.36      7043568.31
#Sta/Elev= 30
  3690.3  640.79  4038.7  640.07  4155.8  638.23  4192.3  638.68  4294.0  636.47
  4379.0  635.90  4424.2  634.41  4459.6  635.56  4480.7  633.65  4615.0  635.89
  4699.9  632.93  4763.6  635.45  4791.9  632.23  4929.5  632.50  4939.6  631.90
  4958.0  629.12  4963.1  629.26  4994.4  624.33  4996.1  623.83  5006.5  624.33
  5018.7  627.07  5079.4  630.03  5193.1  630.02  5327.2  634.93  5345.2  635.90
  5382.8  640.06  5416.2  640.91  5448.5  642.79  5456.7  643.91  5701.8  648.49
#Mann=3,-1,0
  3690.3    0.05       0  4994.4    0.04       0  5006.5    0.05       0
Bank Sta=4994.4,5006.5
Exp/Cntr=0.3,0.1

Type RM Length L Ch R = 1,33652,959,959,959
BEGIN DESCRIPTION:
Marshall Branch 47.0
END DESCRIPTION:
XS GIS Cut Line= 3
      2357793.88      7045013.65      2359065.63      7044787.95
      2360011.83      7043811.37
#Sta/Elev= 30
  2977.4  640.66  3431.0  639.36  3439.6  638.48  3449.8  639.04  3744.3  635.85
  3845.9  633.28  3896.7  634.02  3917.0  632.25  4060.6  633.55  4181.0  631.25
  4221.7  632.74  4232.8  634.28  4291.2  635.10  4319.5  631.07  4354.8  631.06
  4390.3  629.52  4750.9  629.12  4786.2  627.85  4927.6  626.02  4955.9  624.31
  4970.1  622.80  4971.0  622.03  4972.7  621.53  4983.2  622.03  4998.4  624.53
  5005.3  623.87  5069.1  628.60  5196.5  634.21  5394.3  640.32  5628.8  643.85
#Mann=3,-1,0
  2977.4    0.05       0  4971.0    0.04       0  4983.2    0.05       0
Bank Sta=4971,4983.2
Exp/Cntr=0.3,0.1

Type RM Length L Ch R = 1,32693,544,544,544
BEGIN DESCRIPTION:
Marshall Branch 46.0
END DESCRIPTION:
XS GIS Cut Line= 3
      2359864.24      7045846.95      2360029.00      7044960.00
      2360063.89      7043958.93
#Sta/Elev= 30
  4097.9  644.61  4115.1  640.98  4135.5  638.06  4145.7  635.97  4156.1  632.80
  4176.2  631.70  4196.5  632.02  4261.7  630.46  4267.7  631.02  4319.6  629.99
  4552.5  629.96  4868.0  628.29  4915.7  623.45  4983.5  620.33  4985.3  619.83
  4996.2  620.33  4997.5  623.26  5070.1  623.31  5120.1  625.01  5160.1  624.93
  5190.1  623.56  5210.1  624.40  5370.2  626.92  5540.3  626.72  5590.4  627.78
  5610.4  627.33  5721.6  631.12  5810.5  636.41  5900.6  639.90  6001.7  642.18
#Mann=3,-1,0
  4097.9    0.05       0  4983.5    0.04       0  4996.2    0.05       0
Bank Sta=4983.5,4996.2
Exp/Cntr=0.3,0.1

Type RM Length L Ch R = 1,32149,123,123,123
BEGIN DESCRIPTION:
Marshall Branch 45.0
END DESCRIPTION:
XS GIS Cut Line= 3
      2360532.64      7045669.06      2360584.72      7044753.23
      2360558.69      7043854.92
#Sta/Elev= 30
  4289.8  627.06  4549.3  627.47  4769.6  626.89  4809.7  627.87  4838.4  626.01
  4909.9  624.42  4919.9  623.80  4939.9  620.75  4949.9  620.25  4970.0  620.22
  5000.0  621.18  5015.3  620.01  5017.1  619.51  5026.2  619.51  5028.0  620.01
  5030.1  621.25  5050.1  620.47  5070.1  621.72  5140.2  622.47  5200.3  621.82
  5320.4  622.19  5400.4  624.77  5540.5  627.33  5620.5  628.05  5800.6  631.53
  5850.6  633.09  5924.0  633.69  5940.6  634.40  6050.7  635.92  6105.8  637.51
#Mann=3,-1,0
  4289.8    0.05       0  5015.3    0.04       0  5028.0    0.05       0
Bank Sta=5015.3,5028
Exp/Cntr=0.3,0.1

Type RM Length L Ch R = 1,32026,412,412,412
BEGIN DESCRIPTION:
Marshall Branch 44.7
END DESCRIPTION:
XS GIS Cut Line= 4
      2360671.53      7045712.42      2360688.89      7045217.64
      2360701.91      7044701.15      2360732.29      7044158.64
#Sta/Elev= 30
  4247.2  626.24  4598.8  626.73  4779.9  625.29  4830.0  625.42  4850.0  624.26
  4890.0  623.23  4910.0  622.92  4920.0  623.69  4930.0  623.23  4940.0  621.21
  4945.0  620.68  4960.0  620.50  5003.7  617.24  5005.5  616.74  5014.6  616.74
  5016.4  617.24  5030.0  618.86  5050.0  619.92  5100.0  619.88  5140.0  620.70
  5160.1  623.16  5170.1  623.35  5190.1  621.36  5310.2  621.10  5360.2  623.16
  5420.3  624.90  5500.5  625.69  5654.8  628.69  5710.8  630.41  5802.3  632.25
#Mann=3,-1,0
  4247.2    0.05       0  5003.7    0.04       0  5016.4    0.05       0
Bank Sta=5003.7,5016.4
Exp/Cntr=0.3,0.1

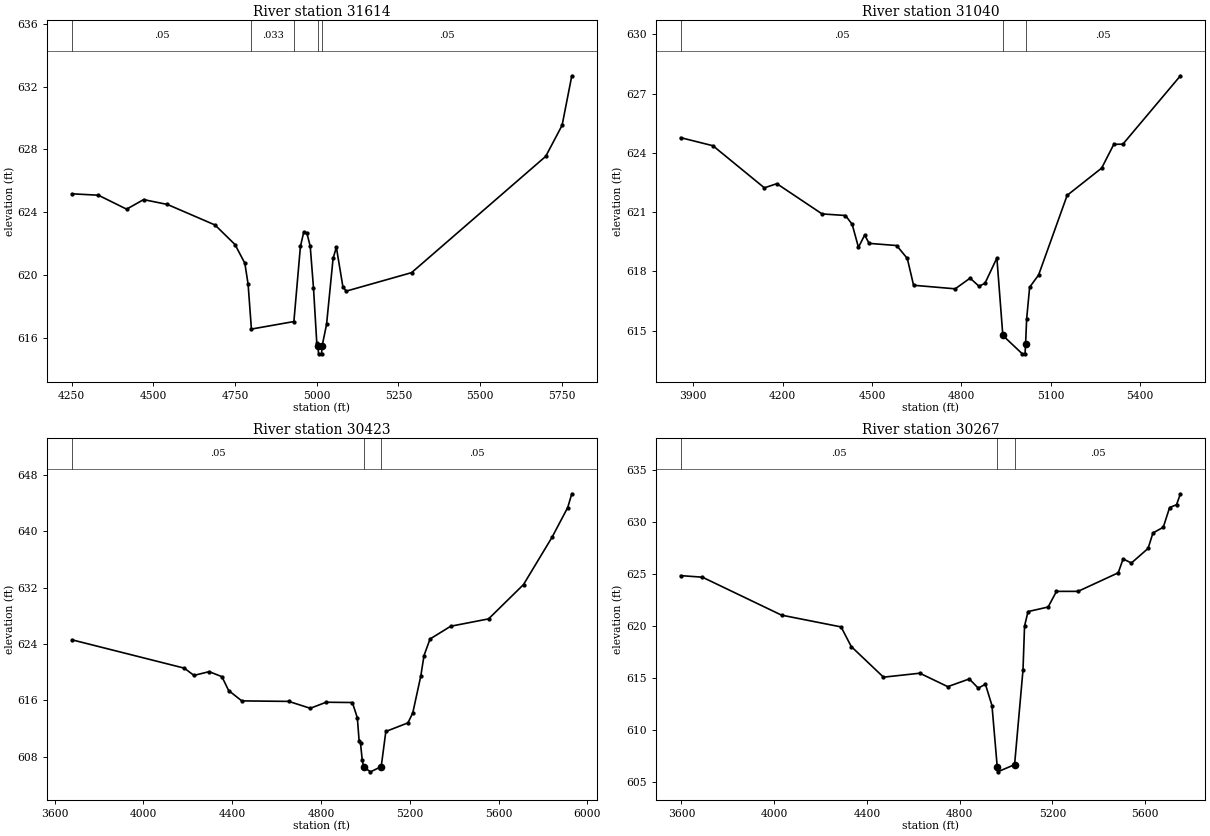
Type RM Length L Ch R = 1,31614,574,574,574
BEGIN DESCRIPTION:
Marshall Branch 44.5
END DESCRIPTION:
XS GIS Cut Line= 4
      2360971.01      7045690.71      2361101.22      7045239.34
      2361114.24      7044722.85      2361144.62      7044180.33
#Sta/Elev= 30
  4250.8  625.17  4331.7  625.08  4418.1  624.19  4470.1  624.80  4543.0  624.49
  4688.7  623.18  4749.9  621.93  4779.9  620.74  4789.9  619.40  4800.0  616.54
  4930.0  617.02  4950.0  621.81  4960.0  622.71  4970.0  622.65  4980.0  621.82
  4990.0  619.17  5000.0  615.68  5003.7  615.46  5005.4  614.96  5014.6  614.96
  5016.4  615.46  5030.0  616.84  5050.0  621.05  5060.0  621.76  5080.0  619.24
  5090.0  618.96  5290.2  620.14  5700.8  627.56  5750.9  629.54  5780.6  632.70
#Mann=5,-1,0
  4250.8    0.05       0  4800.0   0.033       0  4930.0    0.05       0
  5003.7   0.033       0  5016.4    0.05       0
Bank Sta=5003.7,5016.4
Exp/Cntr=0.3,0.1

Type RM Length L Ch R = 1,31040,617,617,617
BEGIN DESCRIPTION:
Marshall Branch 44.3
END DESCRIPTION:
XS GIS Cut Line= 4
      2361014.42      7045716.76      2361656.77      7045269.72
      2361669.79      7044753.23      2361600.35      7044379.99
#Sta/Elev= 30
  3857.1  624.77  3965.7  624.36  4138.5  622.23  4180.4  622.44  4332.3  620.91
  4410.9  620.83  4433.5  620.38  4454.5  619.22  4475.4  619.84  4490.3  619.42
  4582.8  619.31  4618.5  618.66  4639.7  617.30  4779.5  617.12  4829.5  617.66
  4859.5  617.25  4879.5  617.40  4919.5  618.68  4939.5  614.76  5004.9  613.83
  5014.1  613.83  5015.9  614.33  5019.5  615.60  5029.5  617.20  5059.6  617.82
  5155.5  621.85  5271.5  623.23  5312.2  624.43  5342.7  624.44  5536.0  627.90
#Mann=3,-1,0
  3857.1    0.05       0  4939.5   0.033       0  5015.9    0.05       0
Bank Sta=4939.5,5015.9
Exp/Cntr=0.3,0.1

Type RM Length L Ch R = 1,30423,156,156,156
BEGIN DESCRIPTION:
Marshall Branch 44.2
END DESCRIPTION:
XS GIS Cut Line= 3
      2361049.16      7045729.77      2362168.93      7045104.79
      2362935.55      7044511.42
#Sta/Elev= 30
  3678.2  624.61  4184.0  620.59  4227.7  619.56  4296.4  620.09  4353.7  619.38
  4384.0  617.41  4443.4  615.94  4654.8  615.87  4751.9  614.89  4823.2  615.75
  4941.5  615.71  4963.8  613.54  4971.8  610.30  4978.1  609.93  4986.0  607.51
  4992.6  606.54  5023.1  605.87  5071.4  606.61  5092.2  611.60  5191.8  612.82
  5213.6  614.24  5249.7  619.47  5264.2  622.38  5291.4  624.73  5384.6  626.54
  5555.0  627.58  5712.4  632.45  5841.0  639.17  5911.6  643.39  5930.0  645.34
#Mann=3,-1,0
  3678.2    0.05       0  4992.6   0.033       0  5071.4    0.05       0
Bank Sta=4992.6,5071.4
Exp/Cntr=0.3,0.1

Type RM Length L Ch R = 1,30267,379,379,379
BEGIN DESCRIPTION:
Marshall Branch 44.0
END DESCRIPTION:
XS GIS Cut Line= 3
      2360997.15      7045782.89      2362279.00      7045210.00
      2362900.19      7044787.15
#Sta/Elev= 30
  3596.2  624.83  3690.2  624.68  4031.5  621.04  4288.3  619.91  4332.1  618.03
  4471.2  615.09  4627.8  615.47  4748.4  614.18  4841.2  614.92  4879.8  614.04
  4910.8  614.41  4939.0  612.37  4961.6  606.51  4963.4  606.01  5036.5  606.70
  5072.8  615.78  5079.5  619.99  5094.5  621.38  5181.2  621.82  5217.2  623.32
  5310.0  623.32  5483.5  625.10  5504.5  626.43  5540.4  626.04  5612.2  627.44
  5633.2  628.92  5677.7  629.47  5705.1  631.36  5734.9  631.63  5751.7  632.68
#Mann=3,-1,0
  3596.2    0.05       0  4961.6   0.033       0  5036.5    0.05       0
Bank Sta=4961.6,5036.5
Exp/Cntr=0.3,0.1