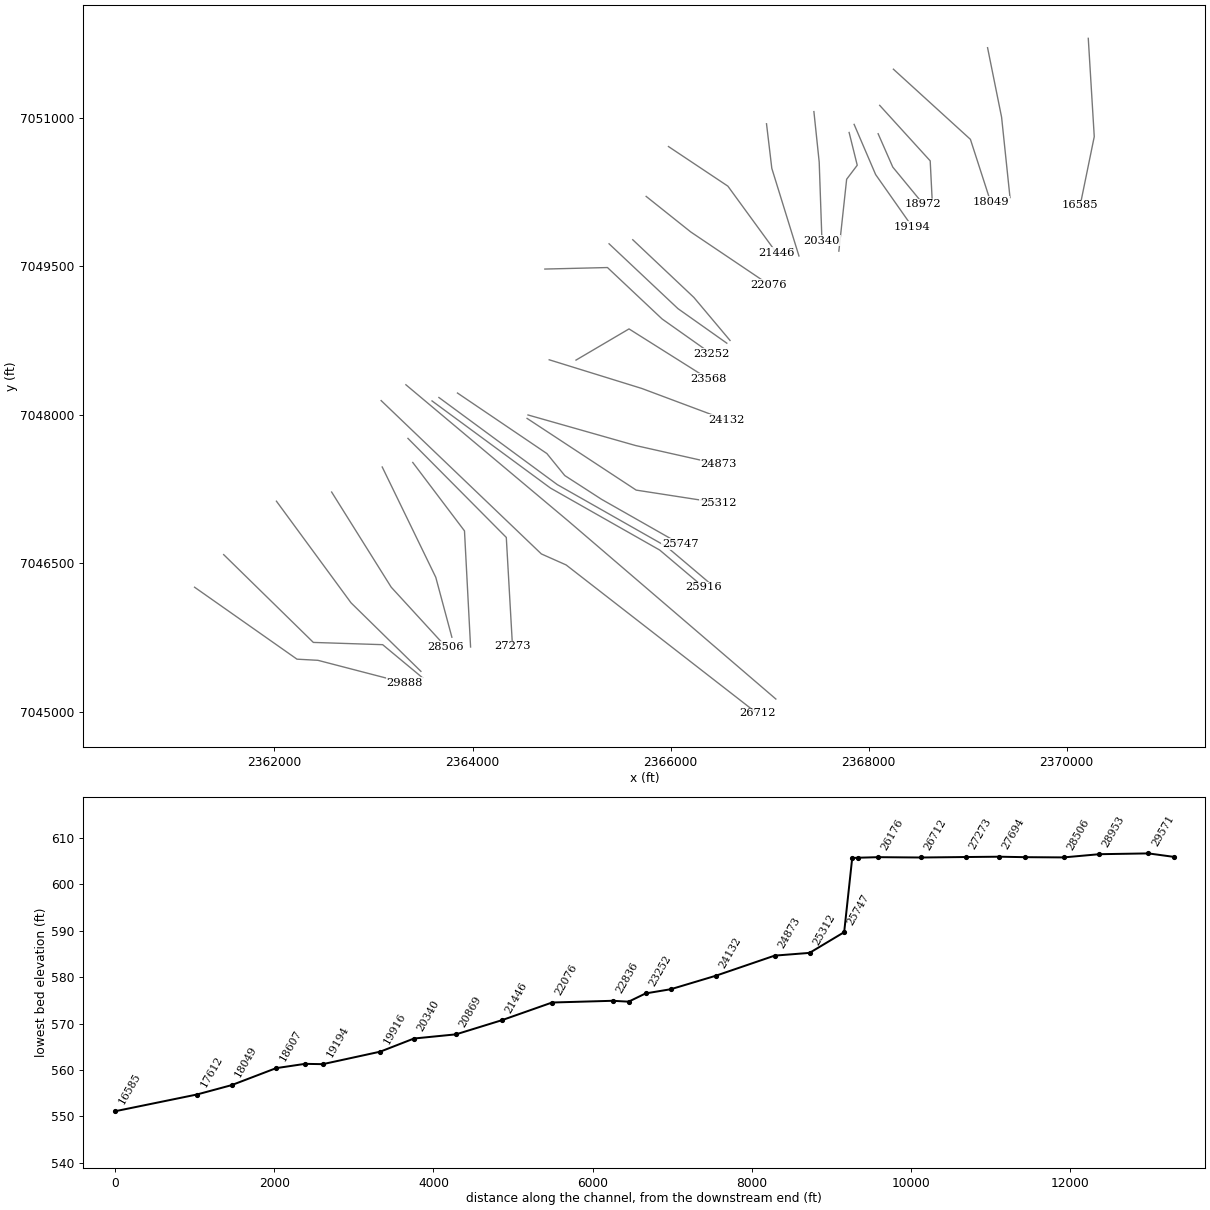
HEC-RAS study Marshall Branch.prj: Marshall Branch Base Level Engineering

--- Marshall Branch.g01 (geometry) --- (continued)

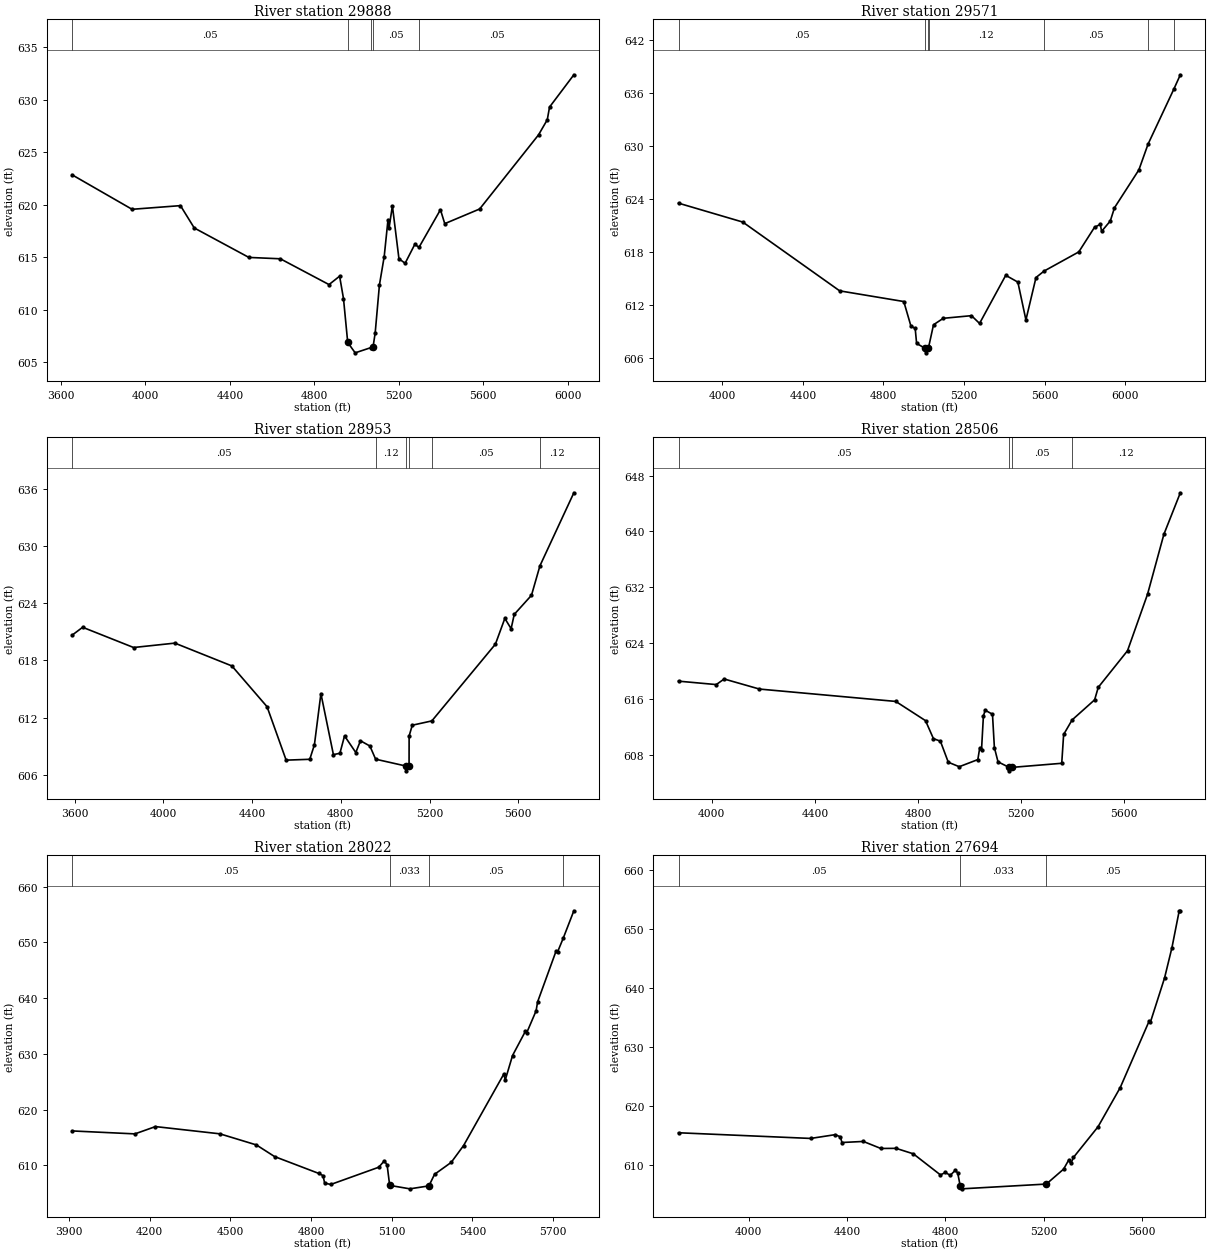
Type RM Length L Ch R = 1,29888,317,317,317
BEGIN DESCRIPTION:
Marshall Branch 43.0
END DESCRIPTION:
XS GIS Cut Line= 4
      2361193.21      7046259.62      2362227.40      7045532.99
      2362438.85      7045521.46      2363310.87      7045294.81
#Sta/Elev= 30
  3652.7  622.85  3936.9  619.56  4166.1  619.91  4231.4  617.78  4490.2  614.97
  4639.2  614.84  4869.7  612.38  4919.9  613.18  4938.3  611.04  4958.3  606.86
  4993.6  605.87  5068.5  606.37  5078.5  606.45  5088.5  607.79  5108.5  612.35
  5131.1  615.05  5149.1  618.57  5154.2  617.78  5169.9  619.89  5200.9  614.85
  5230.1  614.41  5275.9  616.21  5296.1  615.94  5397.5  619.52  5417.9  618.19
  5583.2  619.59  5862.1  626.66  5903.5  628.10  5914.2  629.31  6029.4  632.39
#Mann=5,-1,0
  3652.7    0.05       0  4958.3   0.033       0  5068.5    0.12       0
  5078.5    0.05       0  5296.1    0.05       0
Bank Sta=4958.3,5078.5
Exp/Cntr=0.3,0.1

Type RM Length L Ch R = 1,29571,618,618,618
BEGIN DESCRIPTION:
Marshall Branch 42.0
END DESCRIPTION:
XS GIS Cut Line= 4
      2361487.06      7046588.85      2362392.71      7045702.15
      2363092.67      7045679.36      2363494.78      7045345.70
#Sta/Elev= 30
  3783.2  623.56  4102.0  621.42  4582.9  613.63  4901.1  612.42  4936.4  609.65
  4957.7  609.37  4964.7  607.68  5007.5  607.11  5009.4  606.61  5021.0  607.11
  5024.6  607.28  5048.6  609.79  5097.0  610.52  5237.0  610.82  5277.1  609.94
  5407.1  615.39  5467.2  614.62  5507.2  610.34  5557.2  615.14  5597.3  615.87
  5769.6  618.04  5847.7  620.83  5876.2  621.16  5882.9  620.37  5925.9  621.54
  5946.7  623.04  6067.8  627.33  6113.4  630.25  6241.2  636.47  6273.5  638.10
#Mann=7,-1,0
  3783.2    0.05       0  5007.5    0.04       0  5021.0    0.05       0
  5024.6    0.12       0  5597.3    0.05       0  6113.4    0.12       0
  6241.2    0.05       0
Bank Sta=5007.5,5021
Exp/Cntr=0.3,0.1

Type RM Length L Ch R = 1,28953,447,447,447
BEGIN DESCRIPTION:
Marshall Branch 41.0
END DESCRIPTION:
XS GIS Cut Line= 3
      2362019.82      7047128.43      2362773.32      7046101.98
      2363479.02      7045409.98
#Sta/Elev= 30
  3588.8  620.65  3636.5  621.48  3866.1  619.36  4052.1  619.82  4309.1  617.43
  4467.6  613.16  4553.7  607.56  4660.2  607.65  4681.1  609.17  4710.4  614.53
  4766.7  608.14  4796.0  608.28  4816.9  610.10  4867.6  608.36  4888.7  609.59
  4931.2  609.04  4957.0  607.66  5094.2  606.94  5096.1  606.44  5107.7  606.94
  5108.0  610.09  5122.2  611.22  5210.4  611.67  5496.9  619.71  5539.4  622.41
  5567.7  621.33  5581.8  622.83  5659.5  624.83  5697.6  627.92  5850.5  635.57
#Mann=6,-1,0
  3588.8    0.05       0  4957.0    0.12       0  5094.2    0.07       0
  5107.7    0.12       0  5210.4    0.05       0  5697.6    0.12       0
Bank Sta=5094.2,5107.7
Exp/Cntr=0.3,0.1

Type RM Length L Ch R = 1,28506,484,484,484
BEGIN DESCRIPTION:
Marshall Branch 40.0
END DESCRIPTION:
XS GIS Cut Line= 3
      2362577.32      7047220.84      2363179.00      7046260.00
      2363728.99      7045660.01
#Sta/Elev= 30
  3870.6  618.58  4017.1  618.09  4047.7  618.89  4184.5  617.45  4713.7  615.68
  4829.2  612.93  4859.9  610.36  4887.0  609.99  4917.6  606.98  4960.1  606.34
  5032.3  607.36  5039.7  609.06  5046.5  608.70  5053.9  613.60  5060.7  614.42
  5089.1  613.85  5096.5  609.08  5110.6  607.04  5153.2  606.25  5155.1  605.75
  5166.7  606.25  5357.9  606.83  5365.3  610.95  5398.1  613.03  5485.6  615.91
  5499.7  617.70  5613.2  622.93  5690.9  631.01  5754.4  639.59  5818.2  645.53
#Mann=4,-1,0
  3870.6    0.05       0  5153.2   0.033       0  5166.7    0.05       0
  5398.1    0.12       0
Bank Sta=5153.2,5166.7
Exp/Cntr=0.3,0.1

Type RM Length L Ch R = 1,28022,328,328,328
BEGIN DESCRIPTION:
Marshall Branch 39.0
END DESCRIPTION:
XS GIS Cut Line= 3
      2363088.23      7047473.75      2363629.00      7046360.00
      2363791.63      7045754.76
#Sta/Elev= 30
  3912.0  616.19  4145.6  615.66  4221.9  616.97  4461.5  615.67  4596.9  613.68
  4664.6  611.59  4828.1  608.58  4844.5  608.18  4850.6  606.84  4873.2  606.58
  5051.9  609.68  5072.6  610.84  5082.9  610.06  5092.3  606.42  5167.4  605.80
  5238.2  606.33  5259.0  608.40  5321.1  610.55  5366.9  613.56  5516.5  626.40
  5521.7  625.31  5548.9  629.72  5596.4  634.04  5601.6  633.80  5636.4  637.73
  5642.1  639.35  5711.2  648.53  5716.4  648.32  5737.3  650.77  5776.8  655.69
#Mann=4,-1,0
  3912.0    0.05       0  5092.3   0.033       0  5238.2    0.05       0
  5737.3    0.05       0
Bank Sta=5092.3,5238.2
Exp/Cntr=0.3,0.1

Type RM Length L Ch R = 1,27694,421,421,421
BEGIN DESCRIPTION:
Marshall Branch 38.0
END DESCRIPTION:
XS GIS Cut Line= 3
      2363396.77      7047519.43      2363918.99      7046828.59
      2363980.50      7045656.01
#Sta/Elev= 30
  3714.9  615.40  4252.2  614.44  4352.1  615.08  4373.0  614.71  4379.2  613.75
  4466.3  613.93  4537.4  612.74  4599.5  612.76  4669.6  611.83  4779.8  608.26
  4799.8  608.67  4819.8  608.19  4839.8  609.03  4849.9  608.61  4859.9  606.44
  4866.2  606.47  4866.3  605.90  5210.4  606.71  5280.5  609.24  5300.5  610.72
  5310.5  610.21  5320.5  611.22  5420.6  616.42  5510.8  623.06  5628.5  634.34
  5633.5  634.14  5691.0  641.63  5721.1  646.78  5750.6  653.01  5755.1  653.01
#Mann=3,-1,0
  3714.9    0.05       0  4859.9   0.033       0  5210.4    0.05       0
Bank Sta=4859.9,5210.4
Exp/Cntr=0.3,0.1

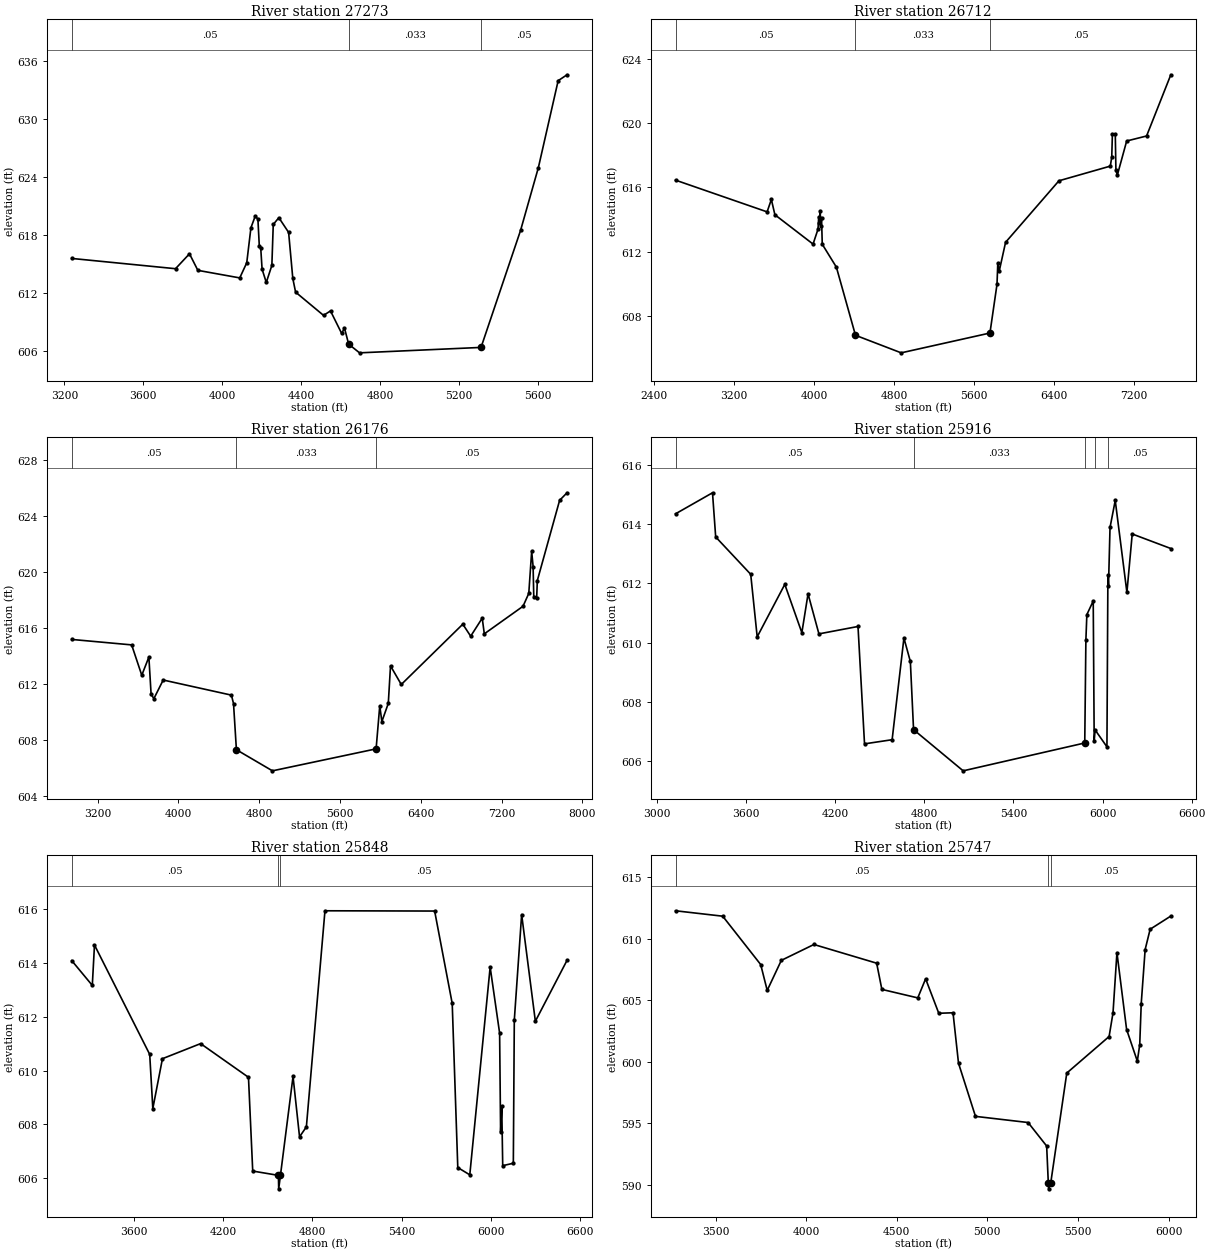
Type RM Length L Ch R = 1,27273,561,561,561
BEGIN DESCRIPTION:
Marshall Branch 37.0
END DESCRIPTION:
XS GIS Cut Line= 3
      2363348.14      7047762.49      2364341.23      7046762.46
      2364403.73      7045665.20
#Sta/Elev= 30
  3237.6  615.58  3763.2  614.52  3833.9  616.06  3876.3  614.35  4088.5  613.57
  4123.9  615.13  4145.1  618.75  4166.3  619.92  4180.4  619.66  4187.5  616.87
  4194.6  616.71  4201.6  614.47  4222.9  613.10  4251.1  614.86  4258.2  619.09
  4286.5  619.79  4336.0  618.27  4357.2  613.51  4371.3  612.10  4512.8  609.70
  4548.1  610.16  4604.7  607.83  4618.8  608.40  4640.0  606.73  4695.2  605.83
  5310.5  606.39  5510.8  618.48  5601.0  624.97  5701.1  633.94  5746.0  634.55
#Mann=3,-1,0
  3237.6    0.05       0  4640.0   0.033       0  5310.5    0.05       0
Bank Sta=4640,5310.5
Exp/Cntr=0.3,0.1

Type RM Length L Ch R = 1,26712,536,536,536
BEGIN DESCRIPTION:
Marshall Branch 36.0
END DESCRIPTION:
XS GIS Cut Line= 4
      2363077.32      7048144.43      2364695.40      7046595.80
      2364945.40      7046484.68      2366874.76      7044985.61
#Sta/Elev= 30
  2613.6  616.45  3530.2  614.48  3572.6  615.25  3608.2  614.30  3990.0  612.48
  4039.7  613.41  4046.6  614.19  4053.8  613.78  4060.7  614.54  4068.0  613.61
  4074.9  614.08  4082.1  612.47  4223.3  611.05  4414.5  606.82  4871.9  605.73
  5760.2  606.96  5830.8  609.98  5838.9  611.31  5853.3  610.81  5916.6  612.59
  6450.7  616.41  6964.8  617.32  6979.2  617.88  6985.6  619.29  7014.5  619.32
  7020.9  617.05  7035.4  616.77  7128.6  618.88  7327.7  619.19  7570.2  622.99
#Mann=3,-1,0
  2613.6    0.05       0  4414.5   0.033       0  5760.2    0.05       0
Bank Sta=4414.5,5760.2
Exp/Cntr=0.3,0.1

Type RM Length L Ch R = 1,26176,260,260,260
BEGIN DESCRIPTION:
Marshall Branch 35.0
END DESCRIPTION:
XS GIS Cut Line= 3
      2363327.32      7048304.15      2364966.23      7046929.13
      2367063.47      7045130.50
#Sta/Elev= 30
  2944.7  615.19  3537.7  614.80  3637.9  612.63  3708.1  613.93  3730.1  611.28
  3757.6  610.96  3849.9  612.29  4525.1  611.21  4545.9  610.61  4574.5  607.31
  4931.3  605.80  5957.2  607.37  5993.4  610.45  6014.2  609.32  6077.9  610.62
  6099.8  613.30  6206.3  611.97  6815.4  616.28  6893.3  615.42  7007.5  616.71
  7028.3  615.59  7411.4  617.56  7468.4  618.48  7497.0  621.49  7511.2  620.40
  7517.8  618.23  7546.4  618.14  7553.0  619.40  7773.6  625.13  7846.9  625.67
#Mann=3,-1,0
  2944.7    0.05       0  4574.5   0.033       0  5957.2    0.05       0
Bank Sta=4574.5,5957.2
Exp/Cntr=0.3,0.1

Type RM Length L Ch R = 1,25916,68,68,68
BEGIN DESCRIPTION:
Marshall Branch 34.2
END DESCRIPTION:
XS GIS Cut Line= 4
      2363591.20      7048140.96      2364787.45      7047260.78
      2365890.43      7046634.92      2366334.68      7046259.15
#Sta/Elev= 30
  3124.4  614.35  3373.4  615.06  3394.8  613.57  3630.7  612.31  3674.3  610.20
  3860.2  611.97  3975.1  610.34  4016.8  611.65  4090.0  610.30  4353.2  610.55
  4397.1  606.59  4583.0  606.73  4662.4  610.16  4705.7  609.37  4727.3  607.07
  5061.4  605.68  5880.1  606.62  5887.8  610.10  5894.3  610.95  5937.2  611.41
  5943.7  606.70  5950.0  607.06  6029.5  606.49  6036.0  612.27  6040.0  611.92
  6050.3  613.89  6085.4  614.80  6164.0  611.70  6199.8  613.67  6459.6  613.18
#Mann=5,-1,0
  3124.4    0.05       0  4727.3   0.033       0  5880.1    0.05       0
  5950.0   0.043       0  6040.0    0.05       0
Bank Sta=4727.3,5880.1
Exp/Cntr=0.3,0.1

Type RM Length L Ch R = 1,25848,101,101,101
BEGIN DESCRIPTION:
Marshall Branch 34.1
END DESCRIPTION:
XS GIS Cut Line= 4
      2363660.64      7048175.68      2364856.90      7047295.50
      2365959.88      7046669.64      2366403.44      7046294.46
#Sta/Elev= 30
  3179.4  614.08  3317.8  613.16  3332.5  614.66  3704.3  610.60  3725.2  608.59
  3790.0  610.44  4046.9  611.00  4369.2  609.75  4397.8  606.27  4570.7  606.11
  4572.7  605.61  4584.4  606.11  4669.2  609.78  4713.0  607.54  4759.0  607.91
  4884.1  615.93  5622.5  615.92  5740.8  612.49  5778.3  606.40  5859.1  606.13
  5996.2  613.84  6059.9  611.39  6066.5  607.72  6074.2  608.69  6080.8  606.47
  6152.2  606.56  6158.8  611.87  6208.2  615.79  6300.5  611.83  6513.7  614.09
#Mann=3,-1,0
  3179.4    0.05       0  4570.7    0.04       0  4584.4    0.05       0
Bank Sta=4570.7,4584.4
Exp/Cntr=0.3,0.1

Type RM Length L Ch R = 1,25747,435,435,435
BEGIN DESCRIPTION:
Marshall Branch 34.0
END DESCRIPTION:
XS GIS Cut Line= 5
      2363848.18      7048220.79      2364750.95      7047609.68
      2364931.51      7047387.46      2365303.90      7047147.01
      2366098.14      7046695.64
#Sta/Elev= 30
  3279.2  612.26  3539.6  611.82  3749.2  607.89  3785.2  605.79  3863.1  608.23
  4042.9  609.52  4389.2  608.00  4417.9  605.87  4616.1  605.18  4659.4  606.73
  4732.0  603.93  4810.6  603.97  4840.9  599.87  4934.6  595.55  5225.0  595.05
  5327.4  593.14  5336.4  590.16  5338.4  589.66  5350.1  590.16  5438.4  599.07
  5672.0  602.04  5693.6  603.97  5715.2  608.86  5768.6  602.61  5827.7  600.04
  5841.0  601.38  5849.3  604.72  5870.9  609.11  5898.5  610.76  6012.5  611.83
#Mann=3,-1,0
  3279.2    0.05       0  5336.4    0.04       0  5350.1    0.05       0
Bank Sta=5336.4,5350.1
Exp/Cntr=0.3,0.1

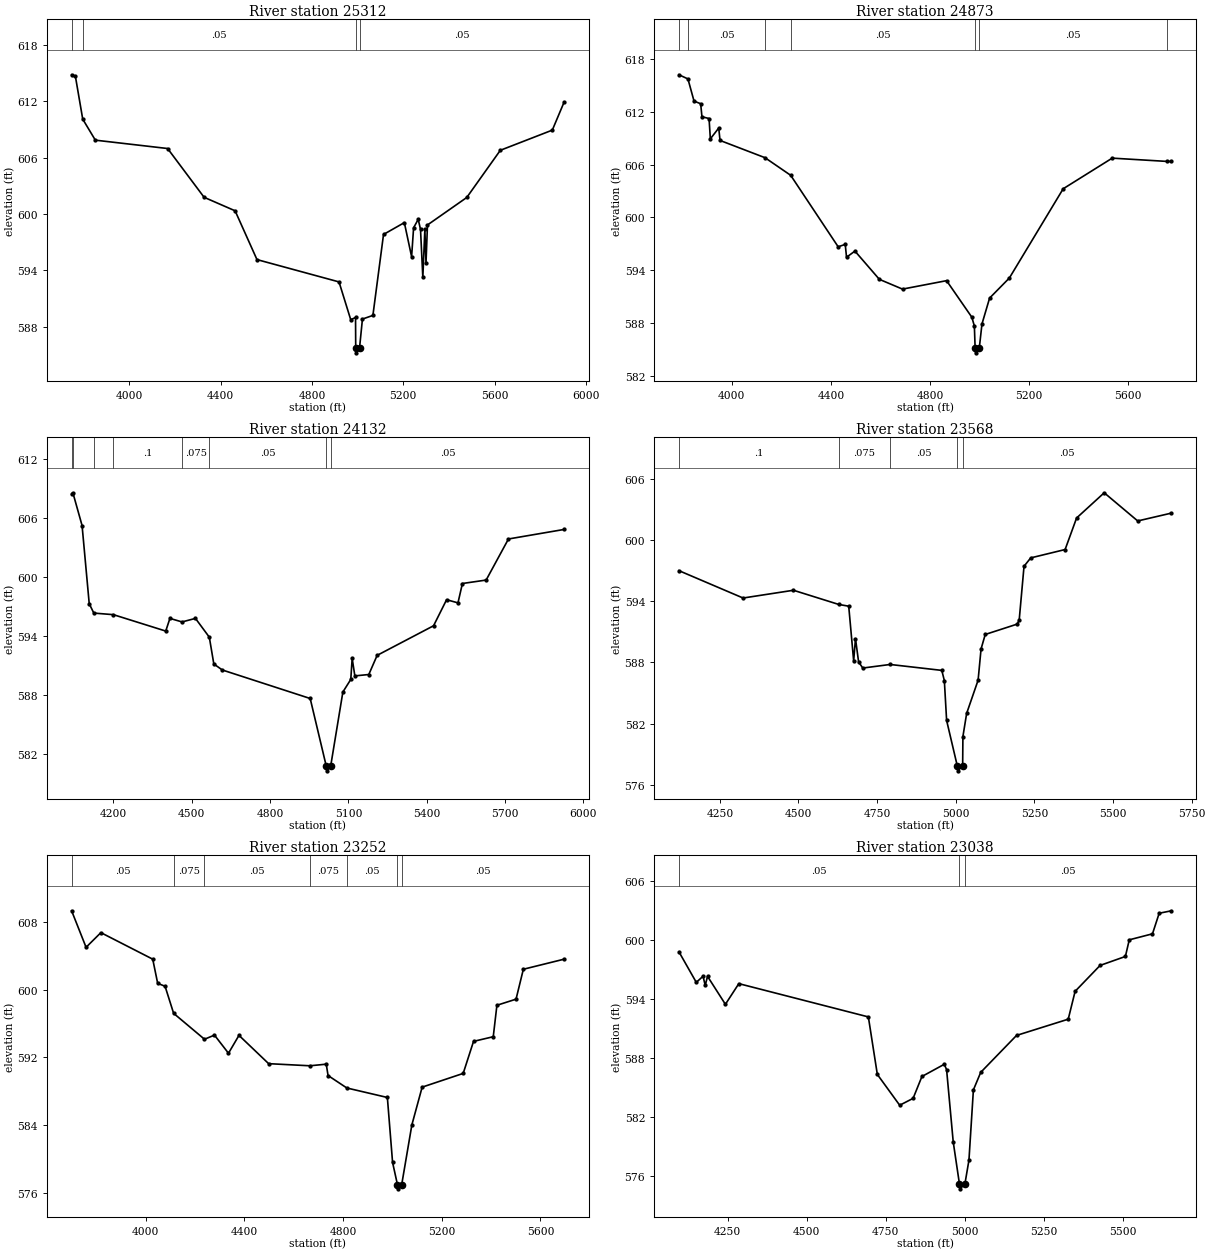
Type RM Length L Ch R = 1,25312,439,439,439
BEGIN DESCRIPTION:
Marshall Branch 33.0
END DESCRIPTION:
XS GIS Cut Line= 3
      2364550.99      7047964.56      2365653.00      7047240.38
      2366480.08      7047112.29
#Sta/Elev= 30
  3748.3  614.84  3764.8  614.69  3797.0  610.11  3852.2  607.87  4168.5  606.98
  4328.2  601.78  4463.9  600.34  4559.6  595.14  4918.7  592.76  4970.0  588.73
  4991.0  588.97  4991.8  585.70  4993.8  585.20  5008.4  585.70  5021.2  588.80
  5067.0  589.19  5113.5  597.82  5204.6  599.08  5236.4  595.45  5245.1  598.53
  5265.3  599.43  5275.4  598.36  5285.5  593.24  5294.4  598.35  5299.4  594.78
  5305.8  598.83  5477.8  601.76  5624.7  606.79  5852.2  608.94  5903.9  611.93
#Mann=4,-1,0
  3748.3   0.075       0  3797.0    0.05       0  4991.8    0.04       0
  5008.4    0.05       0
Bank Sta=4991.8,5008.4
Exp/Cntr=0.3,0.1

Type RM Length L Ch R = 1,24873,741,741,741
BEGIN DESCRIPTION:
Marshall Branch 32.0
END DESCRIPTION:
XS GIS Cut Line= 3
      2364560.45      7047999.20      2365646.70      7047690.64
      2366485.65      7047502.11
#Sta/Elev= 30
  3786.5  616.20  3822.8  615.73  3847.4  613.21  3874.2  612.91  3879.4  611.43
  3908.1  611.23  3913.3  608.92  3947.2  610.15  3952.4  608.74  4134.0  606.78
  4237.7  604.78  4429.5  596.66  4458.1  596.93  4463.3  595.47  4497.2  596.17
  4595.9  592.96  4689.4  591.85  4867.3  592.81  4969.3  588.66  4979.6  587.66
  4982.7  585.11  4984.7  584.61  4999.3  585.11  5010.3  587.89  5041.1  590.83
  5120.9  593.11  5338.3  603.25  5536.3  606.73  5756.1  606.36  5775.6  606.35
#Mann=7,-1,0
  3786.5   0.075       0  3822.8    0.05       0  4134.0   0.075       0
  4237.7    0.05       0  4982.7   0.033       0  4999.3    0.05       0
  5756.1   0.075       0
Bank Sta=4982.7,4999.3
Exp/Cntr=0.3,0.1

Type RM Length L Ch R = 1,24132,564,564,564
BEGIN DESCRIPTION:
Marshall Branch 31.0
END DESCRIPTION:
XS GIS Cut Line= 3
      2364774.57      7048556.51      2365709.67      7048266.85
      2366559.80      7047948.84
#Sta/Elev= 30
  4039.6  608.43  4044.5  608.56  4079.7  605.23  4107.1  597.27  4124.7  596.32
  4199.6  596.16  4400.2  594.49  4416.2  595.78  4462.6  595.42  4514.0  595.78
  4567.1  593.87  4584.4  591.14  4617.0  590.53  4953.5  587.63  5014.9  580.77
  5016.9  580.27  5032.1  580.77  5078.7  588.29  5109.0  589.57  5114.3  591.71
  5124.6  589.93  5178.0  590.07  5210.0  592.02  5426.1  595.03  5476.0  597.68
  5519.6  597.36  5536.6  599.33  5627.5  599.68  5713.0  603.86  5926.2  604.83
#Mann=8,-1,0
  4039.6   0.075       0  4044.5    0.05       0  4124.7   0.075       0
  4199.6     0.1       0  4462.6   0.075       0  4567.1    0.05       0
  5014.9   0.033       0  5032.1    0.05       0
Bank Sta=5014.9,5032.1
Exp/Cntr=0.3,0.1

Type RM Length L Ch R = 1,23568,316,316,316
BEGIN DESCRIPTION:
Marshall Branch 30.0
END DESCRIPTION:
XS GIS Cut Line= 3
      2365045.31      7048553.37      2365580.58      7048868.24
      2366379.90      7048364.73
#Sta/Elev= 30
  4120.1  596.99  4324.0  594.31  4484.1  595.07  4628.2  593.68  4659.8  593.51
  4675.5  588.15  4681.3  590.33  4691.2  588.05  4704.5  587.45  4791.4  587.80
  4955.7  587.22  4963.8  586.22  4971.0  582.32  5004.8  577.88  5006.8  577.38
  5022.0  577.88  5022.8  580.74  5034.7  583.01  5071.1  586.26  5080.5  589.32
  5093.8  590.74  5195.9  591.76  5201.8  592.17  5217.1  597.42  5238.3  598.24
  5347.7  599.06  5384.2  602.15  5472.0  604.62  5578.5  601.86  5685.8  602.63
#Mann=5,-1,0
  4120.1     0.1       0  4628.2   0.075       0  4791.4    0.05       0
  5004.8   0.033       0  5022.0    0.05       0
Bank Sta=5004.8,5022
Exp/Cntr=0.3,0.1

Type RM Length L Ch R = 1,23252,214,214,214
BEGIN DESCRIPTION:
Marshall Branch 29.6
END DESCRIPTION:
XS GIS Cut Line= 4
      2364730.40      7049472.78      2365362.86      7049488.03
      2365914.33      7048969.00      2366408.70      7048619.48
#Sta/Elev= 30
  3700.3  609.29  3758.9  604.98  3818.9  606.71  4029.0  603.58  4049.0  600.73
  4079.0  600.38  4113.6  597.19  4238.7  594.13  4279.1  594.62  4335.9  592.48
  4378.4  594.59  4498.6  591.25  4665.7  591.00  4732.0  591.19  4739.3  589.85
  4815.4  588.38  4979.6  587.26  5000.7  579.60  5020.4  576.98  5022.4  576.48
  5037.7  576.98  5078.8  584.02  5120.5  588.48  5286.8  590.10  5328.7  593.88
  5408.6  594.43  5423.4  598.14  5500.9  598.86  5530.5  602.39  5695.7  603.58
#Mann=7,-1,0
  3700.3    0.05       0  4113.6   0.075       0  4238.7    0.05       0
  4665.7   0.075       0  4815.4    0.05       0  5020.4    0.05       0
  5037.7    0.05       0
Bank Sta=5020.4,5037.7
Exp/Cntr=0.3,0.1

Type RM Length L Ch R = 1,23038,202,202,202
BEGIN DESCRIPTION:
Marshall Branch 29.4
END DESCRIPTION:
XS GIS Cut Line= 3
      2365379.04      7049727.85      2366074.92      7049072.90
      2366568.09      7048724.22
#Sta/Elev= 30
  4095.4  598.77  4150.3  595.67  4171.7  596.29  4178.6  595.36  4185.9  596.28
  4242.5  593.44  4285.0  595.54  4695.2  592.16  4723.6  586.32  4794.4  583.19
  4836.9  583.89  4864.8  586.11  4935.6  587.35  4942.9  586.81  4963.9  579.47
  4983.6  575.20  4985.6  574.70  5000.9  575.20  5013.7  577.61  5027.8  584.75
  5051.0  586.53  5164.4  590.28  5328.1  591.93  5349.9  594.76  5429.0  597.39
  5509.1  598.30  5521.4  599.99  5594.9  600.60  5616.1  602.69  5655.0  602.94
#Mann=3,-1,0
  4095.4    0.05       0  4983.6    0.05       0  5000.9    0.05       0
Bank Sta=4983.6,5000.9
Exp/Cntr=0.3,0.1

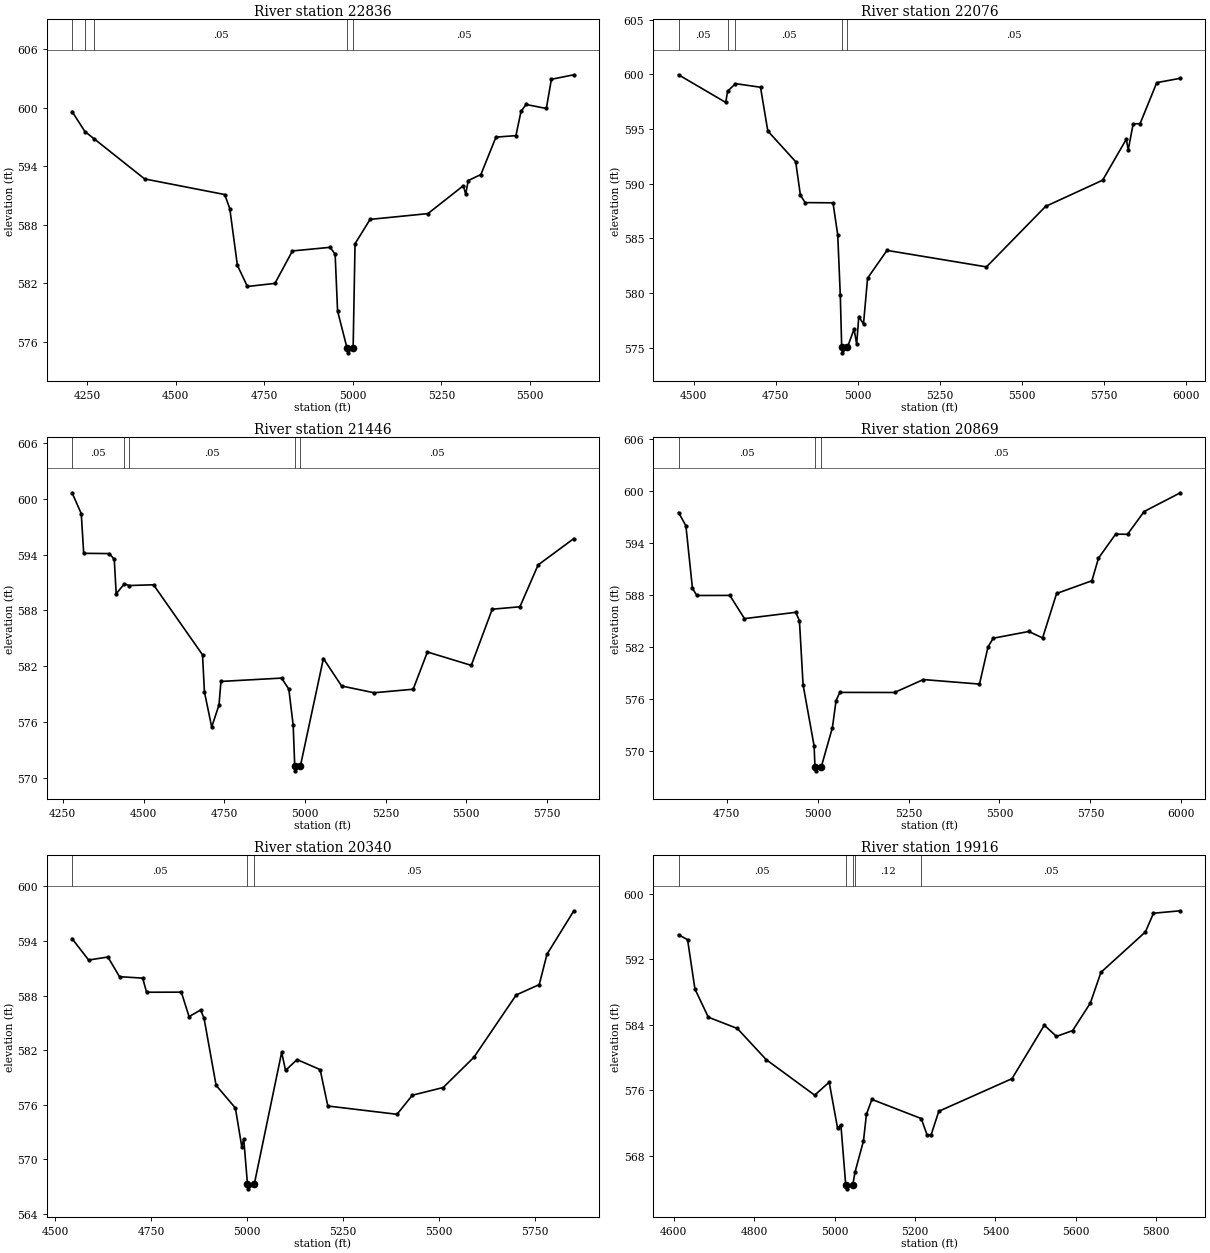
Type RM Length L Ch R = 1,22836,760,760,760
BEGIN DESCRIPTION:
Marshall Branch 29.0
END DESCRIPTION:
XS GIS Cut Line= 3
      2365618.36      7049768.75      2366235.50      7049186.25
      2366600.77      7048751.71
#Sta/Elev= 30
  4207.7  599.59  4244.0  597.54  4270.9  596.77  4412.5  592.69  4638.7  591.09
  4652.9  589.64  4674.3  583.85  4702.6  581.68  4780.3  582.00  4829.7  585.32
  4936.1  585.69  4950.2  584.98  4957.1  579.17  4983.7  575.39  4985.7  574.89
  5001.0  575.39  5006.4  586.06  5048.9  588.55  5212.1  589.14  5312.2  592.00
  5318.7  591.12  5325.8  592.52  5361.6  593.14  5404.1  596.97  5460.5  597.12
  5474.8  599.60  5489.1  600.31  5546.3  599.90  5560.6  602.89  5624.0  603.35
#Mann=5,-1,0
  4207.7    0.05       0  4244.0   0.075       0  4270.9    0.05       0
  4983.7   0.033       0  5001.0    0.05       0
Bank Sta=4983.7,5001
Exp/Cntr=0.3,0.1

Type RM Length L Ch R = 1,22076,630,630,630
BEGIN DESCRIPTION:
Marshall Branch 27.0
END DESCRIPTION:
XS GIS Cut Line= 3
      2365753.75      7050206.42      2366204.01      7049847.47
      2366994.17      7049315.45
#Sta/Elev= 30
  4453.8  599.95  4597.6  597.42  4603.2  598.45  4627.3  599.14  4703.5  598.81
  4725.7  594.81  4810.6  592.00  4825.0  588.94  4839.4  588.26  4924.3  588.24
  4938.7  585.31  4946.5  579.79  4950.8  575.02  4952.8  574.52  4968.2  575.02
  4988.4  576.69  4996.4  575.32  5002.8  577.82  5017.2  577.16  5029.6  581.35
  5088.8  583.89  5391.7  582.38  5571.7  587.91  5745.6  590.31  5817.5  594.05
  5823.6  593.10  5838.6  595.46  5859.6  595.48  5910.5  599.23  5982.2  599.63
#Mann=5,-1,0
  4453.8    0.05       0  4603.2   0.075       0  4627.3    0.05       0
  4950.8   0.033       0  4968.2    0.05       0
Bank Sta=4950.8,4968.2
Exp/Cntr=0.3,0.1

Type RM Length L Ch R = 1,21446,577,577,577
BEGIN DESCRIPTION:
Marshall Branch 26.0
END DESCRIPTION:
XS GIS Cut Line= 3
      2365979.04      7050709.98      2366579.00      7050310.00
      2367069.91      7049636.49
#Sta/Elev= 30
  4278.7  600.67  4307.2  598.42  4314.7  594.15  4394.3  594.12  4409.4  593.50
  4415.4  589.79  4440.4  590.85  4455.9  590.68  4531.0  590.76  4682.8  583.22
  4688.8  579.21  4711.3  575.44  4733.9  577.82  4739.9  580.35  4927.7  580.71
  4950.2  579.52  4963.7  575.63  4968.5  571.22  4970.5  570.72  4985.9  571.22
  5057.3  582.82  5113.7  579.86  5214.2  579.13  5335.4  579.51  5379.5  583.52
  5515.4  582.08  5580.3  588.13  5666.1  588.39  5722.5  592.90  5833.2  595.74
#Mann=5,-1,0
  4278.7    0.05       0  4440.4   0.075       0  4455.9    0.05       0
  4968.5   0.033       0  4985.9    0.05       0
Bank Sta=4968.5,4985.9
Exp/Cntr=0.3,0.1

Type RM Length L Ch R = 1,20869,529,529,529
BEGIN DESCRIPTION:
Marshall Branch 25.0
END DESCRIPTION:
XS GIS Cut Line= 3
      2366969.13      7050940.05      2367022.66      7050489.80
      2367296.58      7049605.06
#Sta/Elev= 30
  4617.7  597.47  4637.9  595.95  4656.0  588.71  4668.1  587.90  4758.7  587.91
  4799.0  585.23  4940.0  585.96  4950.1  584.99  4960.1  577.60  4990.4  570.55
  4992.8  568.17  4994.8  567.67  5010.4  568.17  5040.7  572.65  5050.8  575.76
  5060.9  576.72  5211.6  576.71  5290.8  578.20  5445.1  577.68  5468.7  581.98
  5482.9  582.97  5580.7  583.75  5618.6  583.00  5657.1  588.13  5754.2  589.60
  5772.3  592.21  5819.5  594.98  5852.1  594.96  5897.9  597.59  5997.3  599.75
#Mann=3,-1,0
  4617.7    0.05       0  4992.8   0.033       0  5010.4    0.05       0
Bank Sta=4992.8,5010.4
Exp/Cntr=0.3,0.1

Type RM Length L Ch R = 1,20340,424,424,424
BEGIN DESCRIPTION:
Marshall Branch 24.0
END DESCRIPTION:
XS GIS Cut Line= 3
      2367447.73      7051062.82      2367501.26      7050552.77
      2367529.00      7049760.00
#Sta/Elev= 30
  4544.7  594.26  4587.8  591.91  4638.0  592.24  4668.2  590.08  4728.5  589.92
  4738.6  588.37  4829.1  588.38  4849.2  585.69  4879.3  586.42  4888.3  585.50
  4919.6  578.14  4969.8  575.65  4986.5  571.38  4991.5  572.26  5001.3  567.27
  5003.3  566.77  5018.9  567.27  5090.3  581.77  5100.3  579.78  5130.4  580.97
  5190.4  579.87  5210.4  575.87  5390.5  574.96  5430.5  577.06  5510.6  577.90
  5590.6  581.22  5700.7  588.07  5760.7  589.21  5780.8  592.54  5850.8  597.32
#Mann=3,-1,0
  4544.7    0.05       0  5001.3   0.033       0  5018.9    0.05       0
Bank Sta=5001.3,5018.9
Exp/Cntr=0.3,0.1

Type RM Length L Ch R = 1,19916,722,722,722
BEGIN DESCRIPTION:
Marshall Branch 23.0
END DESCRIPTION:
XS GIS Cut Line= 4
      2367803.53      7050851.88      2367885.39      7050521.28
      2367778.34      7050379.59      2367699.77      7049653.60
#Sta/Elev= 30
  4611.6  595.03  4634.1  594.42  4652.4  588.39  4685.7  584.94  4757.8  583.56
  4829.9  579.74  4950.3  575.40  4986.4  576.99  5007.2  571.38  5015.5  571.77
  5027.5  564.44  5029.5  563.94  5045.1  564.44  5050.8  566.01  5071.7  569.80
  5079.1  573.06  5092.6  574.88  5215.4  572.54  5229.9  570.55  5240.0  570.55
  5259.1  573.43  5441.2  577.42  5521.6  583.96  5551.8  582.59  5592.0  583.30
  5636.1  586.66  5662.5  590.43  5773.1  595.37  5793.2  597.66  5860.0  597.96
#Mann=5,-1,0
  4611.6    0.05       0  5027.5   0.033       0  5045.1    0.05       0
  5050.8    0.12       0  5215.4    0.05       0
Bank Sta=5027.5,5045.1
Exp/Cntr=0.3,0.1

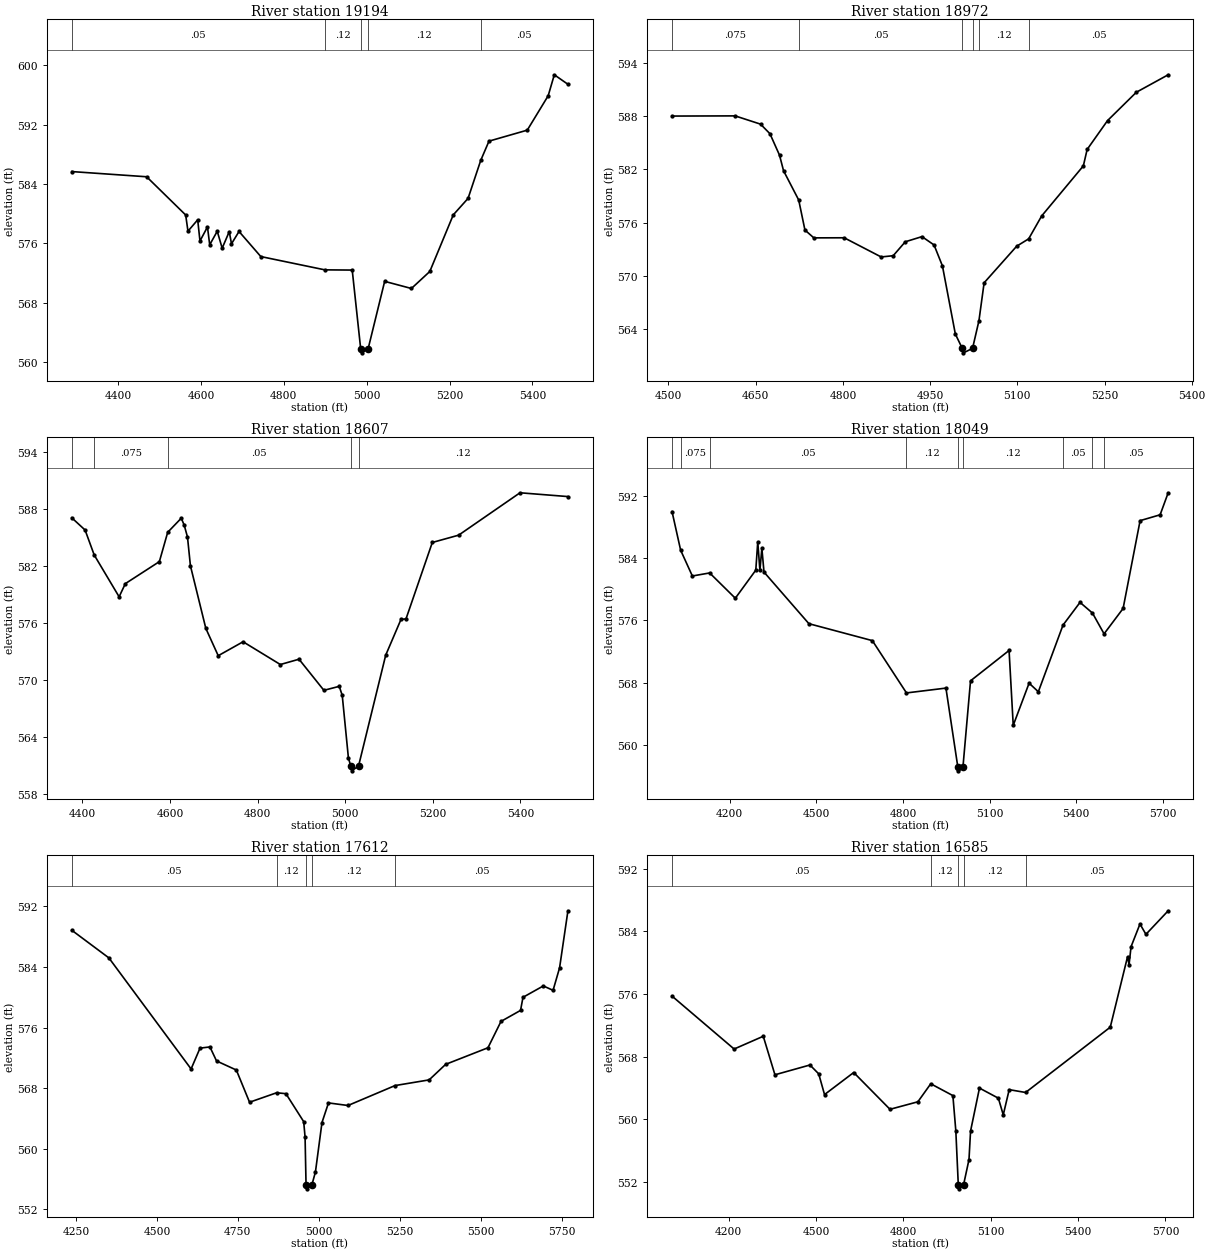
Type RM Length L Ch R = 1,19194,222,222,222
BEGIN DESCRIPTION:
Marshall Branch 22.6
END DESCRIPTION:
XS GIS Cut Line= 3
      2367853.92      7050933.72      2368071.16      7050426.82
      2368442.70      7049897.86
#Sta/Elev= 30
  4288.0  585.67  4468.7  584.97  4563.0  579.82  4568.5  577.64  4592.0  579.17
  4597.5  576.32  4615.6  578.21  4621.0  575.81  4639.2  577.63  4651.1  575.35
  4668.2  577.58  4673.6  575.94  4691.8  577.60  4744.4  574.22  4899.0  572.43
  4965.1  572.40  4985.6  561.75  4987.6  561.25  5003.3  561.75  5043.4  570.88
  5108.0  569.92  5152.4  572.21  5209.1  579.84  5244.8  582.06  5275.4  587.18
  5295.3  589.77  5387.7  591.25  5438.2  595.88  5453.0  598.71  5485.9  597.43
#Mann=5,-1,0
  4288.0    0.05       0  4899.0    0.12       0  4985.6    0.07       0
  5003.3    0.12       0  5275.4    0.05       0
Bank Sta=4985.6,5003.3
Exp/Cntr=0.3,0.1

Type RM Length L Ch R = 1,18972,365,365,365
BEGIN DESCRIPTION:
Marshall Branch 22.4
END DESCRIPTION:
XS GIS Cut Line= 3
      2368096.34      7050839.33      2368244.34      7050502.39
      2368552.91      7050127.71
#Sta/Elev= 30
  4506.1  587.99  4614.6  588.01  4658.3  587.08  4674.5  586.00  4691.0  583.58
  4697.9  581.83  4724.0  578.53  4734.7  575.15  4750.0  574.27  4802.2  574.28
  4865.8  572.12  4886.5  572.26  4907.3  573.83  4936.0  574.41  4956.8  573.47
  4971.2  571.11  4993.4  563.44  5005.3  561.82  5007.3  561.32  5023.0  561.82
  5034.0  564.94  5042.9  569.21  5098.9  573.33  5119.5  574.16  5141.9  576.74
  5213.6  582.38  5220.1  584.23  5255.2  587.48  5304.7  590.67  5359.5  592.64
#Mann=6,-1,0
  4506.1   0.075       0  4724.0    0.05       0  5005.3   0.033       0
  5023.0    0.05       0  5034.0    0.12       0  5119.5    0.05       0
Bank Sta=5005.3,5023
Exp/Cntr=0.3,0.1

Type RM Length L Ch R = 1,18607,558,558,558
BEGIN DESCRIPTION:
Marshall Branch 22.0
END DESCRIPTION:
XS GIS Cut Line= 3
      2368112.08      7051125.85      2368622.18      7050565.37
      2368641.07      7050190.69
#Sta/Elev= 30
  4375.6  587.07  4406.0  585.78  4426.8  583.15  4483.7  578.74  4497.9  580.13
  4575.6  582.45  4594.6  585.54  4625.6  587.03  4632.3  586.30  4639.8  585.05
  4646.5  582.02  4681.7  575.41  4710.0  572.53  4766.8  574.00  4851.9  571.60
  4894.5  572.16  4951.3  568.88  4986.4  569.30  4993.2  568.35  5007.3  561.75
  5012.7  560.89  5014.7  560.39  5030.4  560.89  5092.5  572.59  5127.4  576.36
  5138.8  576.41  5198.9  584.47  5259.0  585.24  5399.2  589.71  5508.6  589.31
#Mann=5,-1,0
  4375.6    0.05       0  4426.8   0.075       0  4594.6    0.05       0
  5012.7   0.033       0  5030.4    0.12       0
Bank Sta=5012.7,5030.4
Exp/Cntr=0.3,0.1

Type RM Length L Ch R = 1,18049,437,437,437
BEGIN DESCRIPTION:
Marshall Branch 21.0
END DESCRIPTION:
XS GIS Cut Line= 3
      2368250.62      7051491.08      2369028.36      7050782.62
      2369233.02      7050149.73
#Sta/Elev= 30
  4001.0  589.95  4030.8  585.00  4071.3  581.70  4131.2  582.09  4220.0  578.85
  4290.9  582.45  4297.7  586.09  4305.1  582.42  4311.9  585.24  4319.3  582.20
  4474.7  575.59  4694.3  573.42  4812.4  566.72  4949.0  567.34  4990.1  557.24
  4992.1  556.74  5007.9  557.24  5034.1  568.27  5167.5  572.16  5181.9  562.57
  5236.8  567.97  5268.8  566.87  5354.2  575.41  5413.1  578.32  5456.2  576.95
  5496.3  574.29  5562.2  577.54  5621.0  588.79  5690.3  589.54  5718.2  592.36
#Mann=9,-1,0
  4001.0    0.05       0  4030.8   0.075       0  4131.2    0.05       0
  4812.4    0.12       0  4990.1    0.07       0  5007.9    0.12       0
  5354.2    0.05       0  5456.2    0.12       0  5496.3    0.05       0
Bank Sta=4990.1,5007.9
Exp/Cntr=0.3,0.1

Type RM Length L Ch R = 1,17612,1027,1027,1027
BEGIN DESCRIPTION:
Marshall Branch 20.0
END DESCRIPTION:
XS GIS Cut Line= 3
      2369201.54      7051708.30      2369343.22      7051006.18
      2369428.18      7050194.38
#Sta/Elev= 30
  4237.1  588.85  4351.7  585.20  4605.6  570.54  4633.2  573.29  4663.8  573.45
  4684.2  571.60  4745.4  570.40  4786.2  566.15  4869.8  567.40  4898.5  567.28
  4953.4  563.59  4957.7  561.55  4960.7  555.22  4962.7  554.72  4978.6  555.22
  4989.7  556.95  5009.9  563.47  5030.0  566.06  5090.3  565.72  5235.6  568.35
  5340.9  569.10  5391.9  571.15  5522.6  573.34  5562.9  576.82  5623.2  578.27
  5630.8  580.00  5693.6  581.50  5723.7  580.92  5743.8  583.89  5769.6  591.42
#Mann=5,-1,0
  4237.1    0.05       0  4869.8    0.12       0  4960.7    0.07       0
  4978.6    0.12       0  5235.6    0.05       0
Bank Sta=4960.7,4978.6
Exp/Cntr=0.3,0.1

Type RM Length L Ch R = 1,16585,591,591,591
BEGIN DESCRIPTION:
Marshall Branch 19.0
END DESCRIPTION:
XS GIS Cut Line= 3
      2370218.55      7051802.76      2370279.00      7050810.00
      2370136.69      7050115.12
#Sta/Elev= 30
  4005.4  575.74  4218.6  568.98  4318.7  570.61  4358.8  565.69  4479.0  566.94
  4509.1  565.81  4529.1  563.16  4629.3  565.98  4753.9  561.28  4849.7  562.24
  4893.9  564.54  4969.9  563.03  4980.0  558.52  4988.5  551.62  4990.5  551.12
  5006.5  551.62  5025.2  554.86  5030.6  558.50  5061.2  563.99  5126.1  562.70
  5142.9  560.57  5163.3  563.79  5219.6  563.43  5510.4  571.77  5569.8  580.78
  5574.9  579.75  5581.8  582.05  5612.4  584.95  5632.9  583.63  5709.3  586.64
#Mann=5,-1,0
  4005.4    0.05       0  4893.9    0.12       0  4988.5    0.07       0
  5006.5    0.12       0  5219.6    0.05       0
Bank Sta=4988.5,5006.5
Exp/Cntr=0.3,0.1