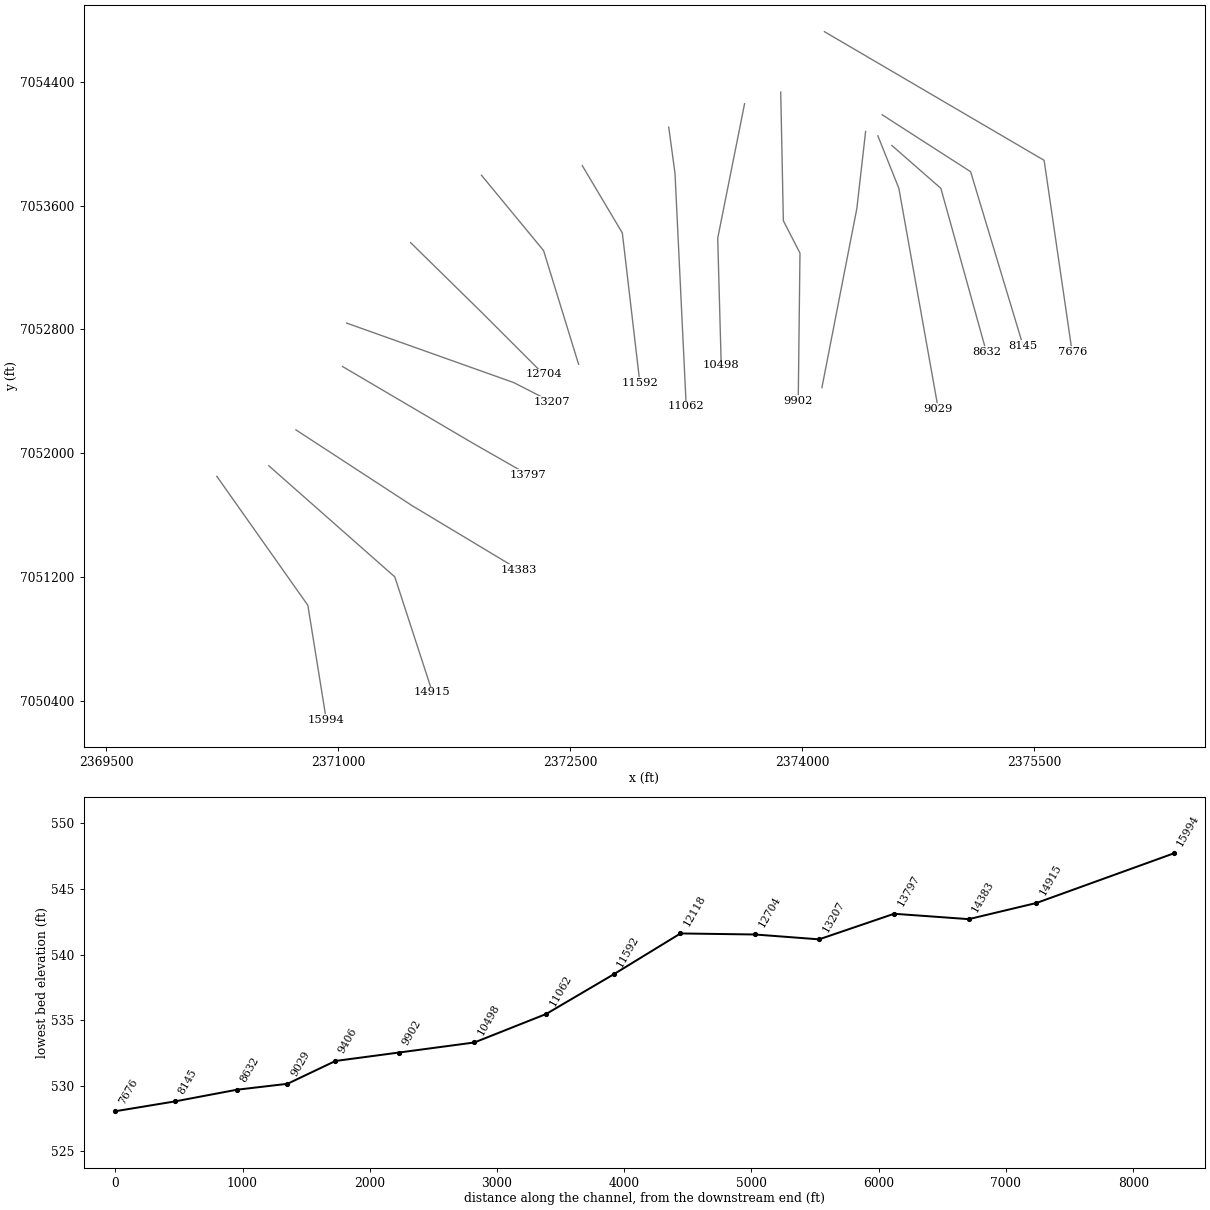
HEC-RAS study Marshall Branch.prj: Marshall Branch Base Level Engineering

--- Marshall Branch.g01 (geometry) --- (continued)

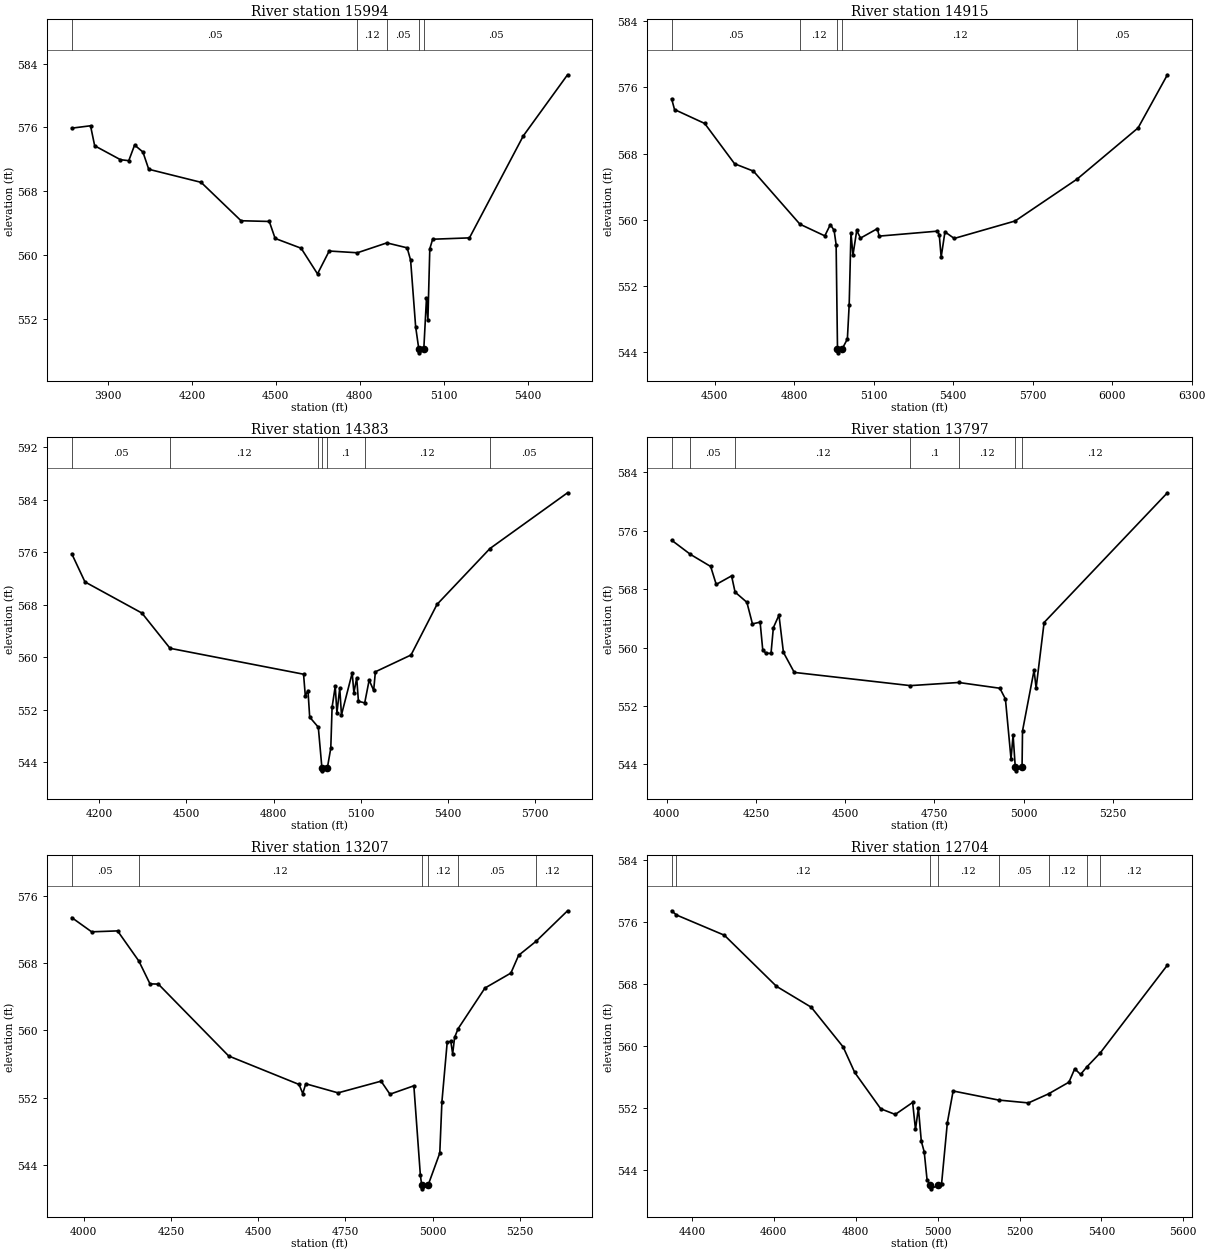
Type RM Length L Ch R = 1,15994,1079,1079,1079
BEGIN DESCRIPTION:
Marshall Branch 18.0
END DESCRIPTION:
XS GIS Cut Line= 3
      2370215.41      7051850.01      2370804.20      7051015.62
      2370923.65      7050273.79
#Sta/Elev= 30
  3770.4  575.91  3837.5  576.21  3852.3  573.70  3944.6  571.95  3974.2  571.83
  3995.1  573.79  4024.7  572.92  4045.6  570.75  4232.8  569.11  4375.6  564.29
  4476.6  564.20  4497.5  562.07  4590.4  560.84  4649.0  557.62  4690.8  560.49
  4791.5  560.27  4896.9  561.51  4969.5  560.89  4981.9  559.34  4999.9  550.98
  5011.1  548.21  5013.1  547.71  5029.1  548.21  5038.7  554.61  5043.7  551.83
  5050.5  560.77  5060.7  561.97  5192.3  562.14  5384.8  574.94  5543.0  582.61
#Mann=5,-1,0
  3770.4    0.05       0  4791.5    0.12       0  4896.9    0.05       0
  5011.1   0.033       0  5029.1    0.05       0
Bank Sta=5011.1,5029.1
Exp/Cntr=0.3,0.1

Type RM Length L Ch R = 1,14915,532,532,532
BEGIN DESCRIPTION:
Marshall Branch 17.0
END DESCRIPTION:
XS GIS Cut Line= 3
      2370551.47      7051918.44      2371366.59      7051199.55
      2371609.56      7050453.67
#Sta/Elev= 30
  4337.1  574.62  4348.1  573.32  4461.9  571.64  4574.8  566.77  4645.9  565.88
  4821.4  559.47  4915.3  558.06  4936.2  559.42  4950.4  558.72  4958.0  557.01
  4963.2  544.43  4965.2  543.93  4981.3  544.43  5000.5  545.60  5007.3  549.72
  5014.0  558.41  5021.6  555.75  5035.8  558.71  5050.0  557.79  5113.6  558.93
  5120.5  558.03  5340.3  558.63  5347.2  558.22  5354.5  555.50  5368.8  558.54
  5403.9  557.75  5633.8  559.86  5867.6  564.92  6097.7  571.10  6208.4  577.52
#Mann=5,-1,0
  4337.1    0.05       0  4821.4    0.12       0  4963.2    0.07       0
  4981.3    0.12       0  5867.6    0.05       0
Bank Sta=4963.2,4981.3
Exp/Cntr=0.3,0.1

Type RM Length L Ch R = 1,14383,586,586,586
BEGIN DESCRIPTION:
Marshall Branch 16.0
END DESCRIPTION:
XS GIS Cut Line= 3
      2370726.99      7052150.48      2371479.00      7051660.00
      2372170.22      7051244.92
#Sta/Elev= 30
  4106.6  575.79  4152.0  571.50  4347.8  566.75  4444.4  561.38  4903.3  557.43
  4909.3  554.15  4918.5  554.94  4924.4  550.89  4954.0  549.35  4966.3  543.20
  4968.3  542.70  4985.3  543.20  4996.9  546.16  5001.4  552.41  5012.2  555.58
  5018.0  551.54  5027.7  555.32  5033.6  551.23  5070.5  557.62  5076.3  554.61
  5086.0  556.85  5091.9  553.31  5113.5  553.06  5128.8  556.53  5144.3  554.96
  5150.2  557.80  5272.7  560.36  5362.0  568.07  5544.0  576.59  5810.7  585.09
#Mann=7,-1,0
  4106.6    0.05       0  4444.4    0.12       0  4954.0     0.1       0
  4966.3    0.07       0  4985.3     0.1       0  5113.5    0.12       0
  5544.0    0.05       0
Bank Sta=4966.3,4985.3
Exp/Cntr=0.3,0.1

Type RM Length L Ch R = 1,13797,590,590,590
BEGIN DESCRIPTION:
Marshall Branch 15.0
END DESCRIPTION:
XS GIS Cut Line= 3
      2371028.98      7052560.01      2371879.00      7052060.00
      2372229.01      7051859.99
#Sta/Elev= 30
  4013.8  574.72  4066.7  572.77  4123.2  571.12  4138.8  568.66  4181.8  569.83
  4191.6  567.61  4224.7  566.21  4240.3  563.25  4261.8  563.49  4269.1  559.72
  4277.5  559.24  4292.3  559.20  4298.9  562.73  4314.6  564.45  4327.1  559.35
  4357.5  556.60  4682.8  554.79  4818.1  555.22  4933.6  554.43  4949.2  552.96
  4964.9  544.75  4970.7  548.01  4976.8  543.61  4978.8  543.11  4995.8  543.61
  4997.1  548.58  5029.5  556.90  5035.2  554.46  5057.6  563.44  5403.1  581.22
#Mann=7,-1,0
  4013.8   0.075       0  4066.7    0.05       0  4191.6    0.12       0
  4682.8     0.1       0  4818.1    0.12       0  4976.8    0.07       0
  4995.8    0.12       0
Bank Sta=4976.8,4995.8
Exp/Cntr=0.3,0.1

Type RM Length L Ch R = 1,13207,503,503,503
BEGIN DESCRIPTION:
Marshall Branch 14.0
END DESCRIPTION:
XS GIS Cut Line= 3
      2371055.28      7052841.06      2372136.40      7052456.16
      2372379.81      7052331.63
#Sta/Elev= 30
  3965.9  573.38  4022.9  571.69  4097.2  571.80  4158.3  568.21  4190.1  565.51
  4214.0  565.48  4415.7  556.94  4617.3  553.56  4628.0  552.48  4636.6  553.64
  4729.1  552.56  4852.4  553.95  4877.9  552.40  4946.4  553.40  4965.1  542.75
  4968.8  541.66  4970.8  541.16  4987.8  541.66  5020.7  545.41  5026.8  551.50
  5041.9  558.55  5052.3  558.68  5057.6  557.19  5063.2  559.15  5073.2  560.18
  5150.1  565.01  5224.5  566.79  5246.7  568.90  5296.8  570.57  5386.9  574.19
#Mann=6,-1,0
  3965.9    0.05       0  4158.3    0.12       0  4968.8    0.07       0
  4987.8    0.12       0  5073.2    0.05       0  5296.8    0.12       0
Bank Sta=4968.8,4987.8
Exp/Cntr=0.3,0.1

Type RM Length L Ch R = 1,12704,586,586,586
BEGIN DESCRIPTION:
Marshall Branch 13.0
END DESCRIPTION:
XS GIS Cut Line= 3
      2371468.51      7053361.79      2371929.00      7052910.00
      2372329.00      7052510.00
#Sta/Elev= 30
  4350.3  577.45  4362.0  576.91  4479.2  574.29  4606.4  567.69  4691.3  564.99
  4769.2  559.86  4797.5  556.56  4861.0  551.87  4896.5  551.14  4938.9  552.69
  4945.9  549.20  4953.0  551.97  4960.1  547.68  4967.2  546.31  4974.2  542.67
  4982.4  542.03  4984.4  541.53  5001.4  542.03  5009.6  542.18  5023.7  550.08
  5037.8  554.17  5148.7  553.00  5221.7  552.63  5270.8  553.80  5320.7  555.31
  5334.8  557.04  5349.0  556.31  5364.4  557.28  5397.7  559.13  5561.1  570.43
#Mann=8,-1,0
  4350.3    0.05       0  4362.0    0.12       0  4982.4    0.07       0
  5001.4    0.12       0  5148.7    0.05       0  5270.8    0.12       0
  5364.4    0.05       0  5397.7    0.12       0
Bank Sta=4982.4,5001.4
Exp/Cntr=0.3,0.1

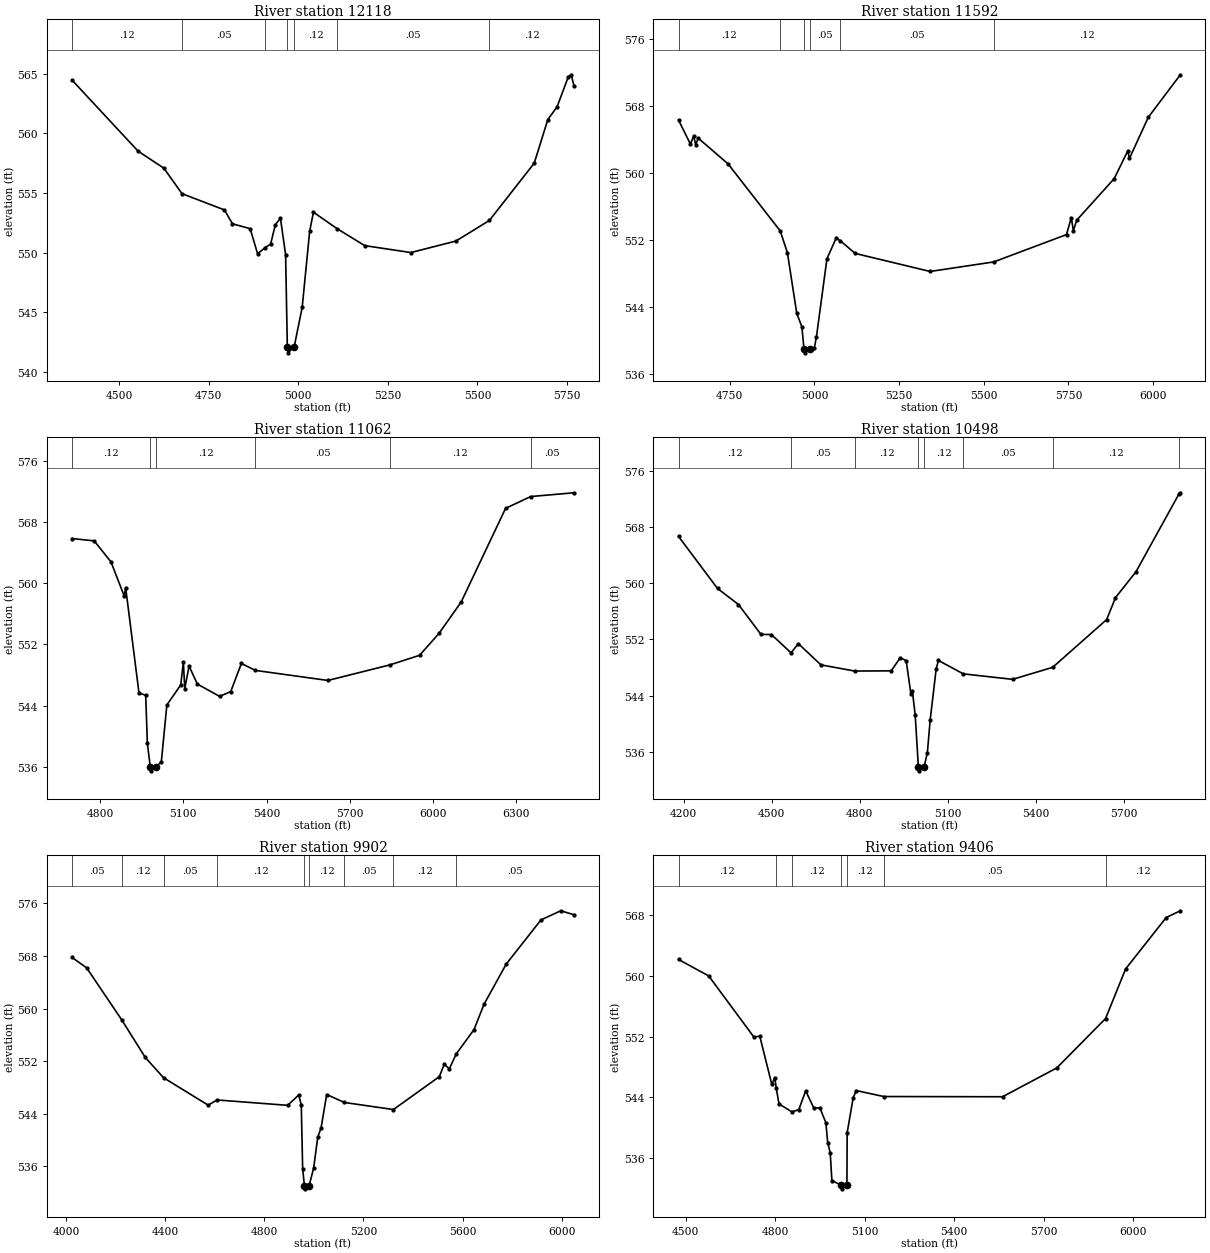
Type RM Length L Ch R = 1,12118,526,526,526
BEGIN DESCRIPTION:
Marshall Branch 12.0
END DESCRIPTION:
XS GIS Cut Line= 3
      2371926.97      7053797.68      2372329.00      7053310.00
      2372555.26      7052575.07
#Sta/Elev= 30
  4368.2  564.45  4552.6  558.50  4624.4  557.08  4675.2  554.94  4793.7  553.58
  4815.9  552.42  4865.4  552.01  4886.2  549.91  4906.9  550.42  4922.5  550.71
  4935.7  552.34  4950.0  552.88  4964.4  549.83  4969.2  542.11  4971.2  541.61
  4988.3  542.11  5010.7  545.42  5031.6  551.80  5042.1  553.39  5107.7  552.02
  5185.2  550.59  5314.1  550.01  5439.7  550.97  5533.4  552.70  5658.6  557.50
  5696.5  561.15  5722.2  562.21  5753.6  564.72  5761.9  564.90  5769.2  564.00
#Mann=7,-1,0
  4368.2    0.12       0  4675.2    0.05       0  4906.9    0.12       0
  4969.2    0.07       0  4988.3    0.12       0  5107.7    0.05       0
  5533.4    0.12       0
Bank Sta=4969.2,4988.3
Exp/Cntr=0.3,0.1

Type RM Length L Ch R = 1,11592,530,530,530
BEGIN DESCRIPTION:
Marshall Branch 11.0
END DESCRIPTION:
XS GIS Cut Line= 3
      2372578.99      7053860.01      2372838.29      7053424.09
      2372951.50      7052456.20
#Sta/Elev= 30
  4598.8  566.32  4633.8  563.46  4643.6  564.42  4649.4  563.36  4657.0  564.16
  4744.9  561.09  4899.1  553.07  4920.2  550.47  4947.9  543.21  4963.0  541.60
  4969.1  538.99  4971.1  538.49  4988.2  538.99  5000.0  539.11  5006.1  540.42
  5037.0  549.74  5064.3  552.22  5076.4  551.90  5120.2  550.38  5341.7  548.22
  5529.4  549.36  5744.4  552.63  5758.6  554.67  5764.6  553.09  5774.6  554.35
  5885.4  559.33  5925.2  562.63  5930.3  561.74  5986.1  566.67  6080.5  571.74
#Mann=6,-1,0
  4598.8    0.12       0  4899.1    0.05       0  4969.1    0.07       0
  4988.2    0.05       0  5076.4    0.05       0  5529.4    0.12       0
Bank Sta=4969.1,4988.2
Exp/Cntr=0.3,0.1

Type RM Length L Ch R = 1,11062,564,564,564
BEGIN DESCRIPTION:
Marshall Branch 10.0
END DESCRIPTION:
XS GIS Cut Line= 3
      2373138.30      7054108.99      2373179.00      7053810.00
      2373251.46      7052304.19
#Sta/Elev= 30
  4698.8  565.82  4778.5  565.52  4839.1  562.77  4886.9  558.30  4892.0  559.41
  4940.0  545.66  4964.3  545.33  4970.3  539.05  4980.9  535.97  4982.9  535.47
  5000.0  535.97  5020.6  536.63  5040.6  544.08  5090.6  546.69  5100.1  549.68
  5105.1  546.22  5120.7  549.15  5150.7  546.80  5230.8  545.20  5270.9  545.83
  5309.3  549.50  5360.0  548.59  5621.3  547.28  5845.2  549.32  5951.6  550.56
  6021.7  553.42  6101.8  557.53  6262.0  569.77  6352.8  571.31  6508.1  571.80
#Mann=6,-1,0
  4698.8    0.12       0  4980.9    0.07       0  5000.0    0.12       0
  5360.0    0.05       0  5845.2    0.12       0  6352.8    0.05       0
Bank Sta=4980.9,5000
Exp/Cntr=0.3,0.1

Type RM Length L Ch R = 1,10498,596,596,596
BEGIN DESCRIPTION:
Marshall Branch 9.0
END DESCRIPTION:
XS GIS Cut Line= 3
      2373629.00      7054260.01      2373455.28      7053390.13
      2373477.92      7052569.40
#Sta/Elev= 30
  4182.9  566.66  4315.6  559.25  4386.9  556.97  4463.5  552.71  4499.0  552.70
  4566.0  550.09  4590.8  551.40  4667.6  548.38  4782.5  547.50  4906.9  547.53
  4937.5  549.39  4957.9  548.98  4973.8  544.24  4978.9  544.62  4988.5  541.26
  4999.4  533.80  5001.4  533.30  5018.5  533.80  5029.9  535.88  5039.5  540.53
  5059.9  547.81  5067.5  549.01  5152.3  547.10  5320.2  546.32  5456.5  548.03
  5640.3  554.83  5670.3  557.95  5740.3  561.65  5887.0  572.75  5891.0  572.87
#Mann=8,-1,0
  4182.9    0.12       0  4566.0    0.05       0  4782.5    0.12       0
  4999.4    0.07       0  5018.5    0.12       0  5152.3    0.05       0
  5456.5    0.12       0  5887.0    0.05       0
Bank Sta=4999.4,5018.5
Exp/Cntr=0.3,0.1

Type RM Length L Ch R = 1,9902,496,496,496
BEGIN DESCRIPTION:
Marshall Branch 8.0
END DESCRIPTION:
XS GIS Cut Line= 4
      2373862.83      7054335.40      2373879.81      7053503.34
      2373987.36      7053293.90      2373976.04      7052337.34
#Sta/Elev= 30
  4024.8  567.78  4083.7  566.19  4224.6  558.30  4320.3  552.54  4393.7  549.46
  4573.8  545.28  4609.9  546.07  4894.5  545.25  4939.5  546.84  4949.4  545.30
  4955.1  535.53  4962.1  533.03  4964.1  532.53  4981.2  533.03  4999.4  535.70
  5016.0  540.41  5029.4  541.81  5051.9  546.90  5122.8  545.69  5321.1  544.61
  5506.4  549.62  5526.4  551.53  5546.4  550.80  5574.7  553.09  5646.4  556.79
  5686.4  560.63  5776.4  566.78  5916.4  573.50  5996.4  574.89  6049.1  574.29
#Mann=9,-1,0
  4024.8    0.05       0  4224.6    0.12       0  4393.7    0.05       0
  4609.9    0.12       0  4962.1    0.07       0  4981.2    0.12       0
  5122.8    0.05       0  5321.1    0.12       0  5574.7    0.05       0
Bank Sta=4962.1,4981.2
Exp/Cntr=0.3,0.1

Type RM Length L Ch R = 1,9406,377,377,377
BEGIN DESCRIPTION:
Marshall Branch 7.0
END DESCRIPTION:
XS GIS Cut Line= 3
      2374411.88      7054080.66      2374355.28      7053582.58
      2374129.14      7052423.62
#Sta/Elev= 30
  4476.0  562.18  4577.3  560.00  4728.3  551.95  4748.4  552.04  4788.7  545.67
  4798.7  546.58  4803.4  545.22  4812.7  543.11  4856.1  542.05  4879.2  542.35
  4902.2  544.83  4929.6  542.55  4949.7  542.59  4969.8  540.63  4976.1  538.00
  4984.5  536.64  4990.1  532.97  5021.3  532.39  5023.3  531.89  5040.5  532.39
  5041.2  539.29  5061.4  543.90  5071.6  544.87  5163.9  544.08  5562.1  544.05
  5744.1  547.86  5907.5  554.38  5974.7  560.93  6110.8  567.72  6158.1  568.61
#Mann=7,-1,0
  4476.0    0.12       0  4803.4    0.05       0  4856.1    0.12       0
  5021.3    0.07       0  5040.5    0.12       0  5163.9    0.05       0
  5907.5    0.12       0
Bank Sta=5021.3,5040.5
Exp/Cntr=0.3,0.1

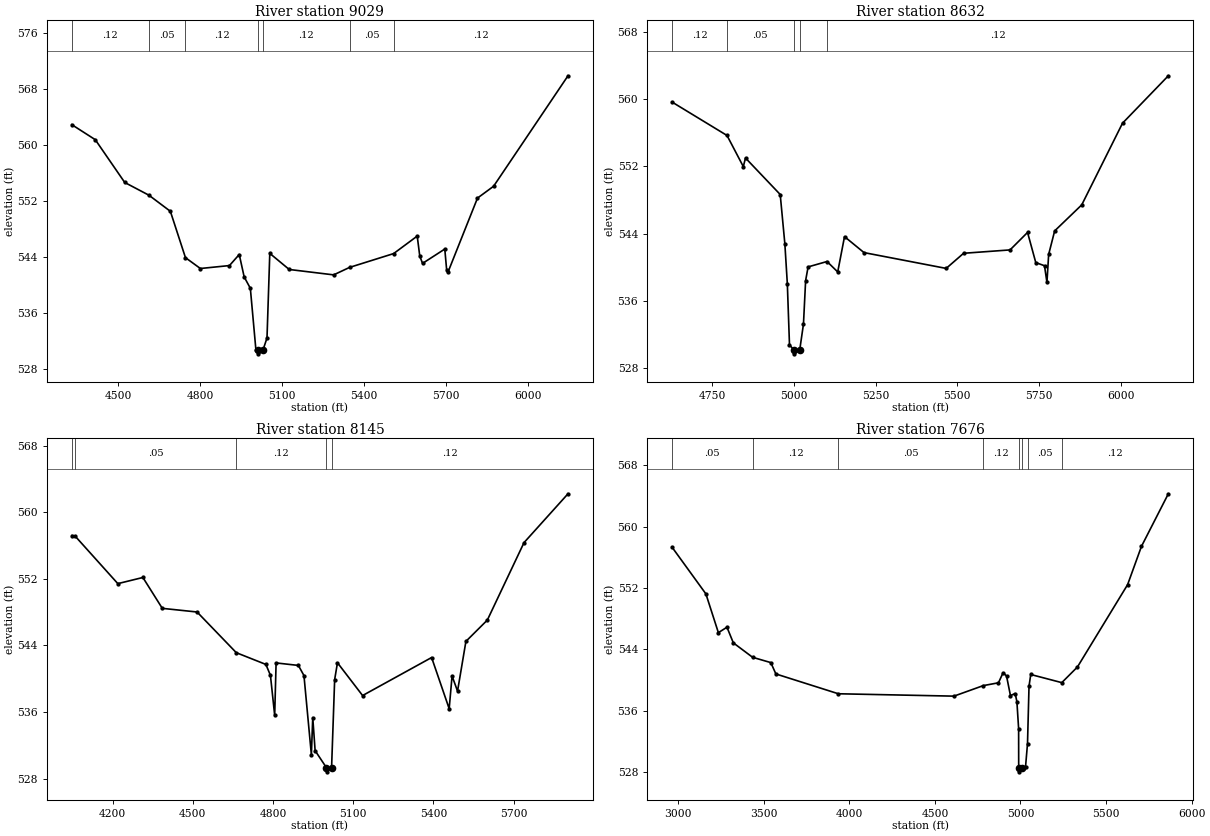
Type RM Length L Ch R = 1,9029,397,397,397
BEGIN DESCRIPTION:
Marshall Branch 6.5
END DESCRIPTION:
XS GIS Cut Line= 3
      2374491.14      7054052.37      2374626.98      7053712.77
      2374881.69      7052286.39
#Sta/Elev= 30
  4331.3  562.89  4417.2  560.74  4524.9  554.63  4613.4  552.81  4691.8  550.51
  4747.0  543.89  4801.5  542.34  4907.9  542.76  4943.7  544.34  4961.7  541.14
  4984.3  539.51  5004.6  530.73  5011.0  530.65  5013.0  530.15  5030.2  530.65
  5045.2  532.42  5055.4  544.50  5126.5  542.20  5289.0  541.43  5347.3  542.50
  5508.2  544.47  5594.6  546.97  5603.9  544.11  5614.1  543.07  5695.4  545.12
  5702.2  542.14  5707.3  541.84  5815.0  552.40  5873.9  554.09  6146.0  569.87
#Mann=7,-1,0
  4331.3    0.12       0  4613.4    0.05       0  4747.0    0.12       0
  5011.0    0.07       0  5030.2    0.12       0  5347.3    0.05       0
  5508.2    0.12       0
Bank Sta=5011,5030.2
Exp/Cntr=0.3,0.1

Type RM Length L Ch R = 1,8632,487,487,487
BEGIN DESCRIPTION:
Marshall Branch 6.0
END DESCRIPTION:
XS GIS Cut Line= 3
      2374581.70      7053990.13      2374898.68      7053712.77
      2375192.93      7052654.61
#Sta/Elev= 30
  4626.7  559.64  4794.8  555.67  4844.7  551.97  4851.4  552.99  4957.7  548.65
  4971.9  542.80  4979.5  538.04  4986.1  530.78  4998.4  530.20  5000.4  529.70
  5017.6  530.20  5028.9  533.24  5035.5  538.41  5043.1  540.04  5101.1  540.68
  5133.8  539.44  5154.6  543.64  5214.3  541.74  5465.9  539.86  5519.3  541.66
  5661.5  542.06  5715.1  544.14  5740.3  540.55  5767.0  540.18  5774.5  538.19
  5779.7  541.52  5798.1  544.32  5881.1  547.42  6005.9  557.13  6146.2  562.77
#Mann=5,-1,0
  4626.7    0.12       0  4794.8    0.05       0  4998.4   0.033       0
  5017.6    0.05       0  5101.1    0.12       0
Bank Sta=4998.4,5017.6
Exp/Cntr=0.3,0.1

Type RM Length L Ch R = 1,8145,469,469,469
BEGIN DESCRIPTION:
Marshall Branch 5.5
END DESCRIPTION:
XS GIS Cut Line= 3
      2374519.40      7054188.27      2375091.14      7053820.32
      2375430.58      7052694.49
#Sta/Elev= 30
  4047.7  557.20  4059.4  557.17  4219.9  551.43  4313.6  552.17  4386.2  548.46
  4516.3  548.02  4663.0  543.13  4773.6  541.72  4790.6  540.41  4806.5  535.61
  4811.8  541.90  4895.1  541.60  4916.0  540.38  4943.7  530.88  4948.9  535.33
  4957.7  531.36  5000.1  529.31  5002.1  528.81  5019.3  529.31  5030.8  539.90
  5041.3  541.92  5135.3  537.98  5393.4  542.55  5459.1  536.40  5469.9  540.33
  5490.4  538.51  5521.7  544.49  5601.8  547.05  5739.0  556.36  5903.5  562.23
#Mann=5,-1,0
  4047.7    0.12       0  4059.4    0.05       0  4663.0    0.12       0
  5000.1    0.07       0  5019.3    0.12       0
Bank Sta=5000.1,5019.3
Exp/Cntr=0.3,0.1

Type RM Length L Ch R = 1,7676,0,0,0
BEGIN DESCRIPTION:
Marshall Branch 5.0
END DESCRIPTION:
XS GIS Cut Line= 3
      2374145.88      7054725.97      2375566.61      7053893.90
      2375747.69      7052654.62
#Sta/Elev= 30
  2964.8  557.31  3162.1  551.24  3235.0  546.19  3285.2  546.90  3322.4  544.86
  3435.0  542.98  3541.3  542.29  3571.0  540.81  3936.0  538.23  4611.3  537.92
  4782.2  539.29  4871.4  539.66  4898.2  540.97  4918.4  540.55  4941.3  538.00
  4968.9  538.26  4979.0  537.20  4989.1  533.68  4989.5  528.56  4991.5  528.06
  5009.0  528.56  5029.6  528.75  5041.0  531.74  5049.8  539.21  5059.9  540.74
  5241.2  539.68  5332.7  541.72  5625.7  552.44  5706.7  557.43  5863.7  564.28
#Mann=8,-1,0
  2964.8    0.05       0  3435.0    0.12       0  3936.0    0.05       0
  4782.2    0.12       0  4989.5    0.07       0  5009.0    0.12       0
  5041.0    0.05       0  5241.2    0.12       0
Bank Sta=4989.5,5009
Exp/Cntr=0.3,0.1

Chan Stop Cuts=-1