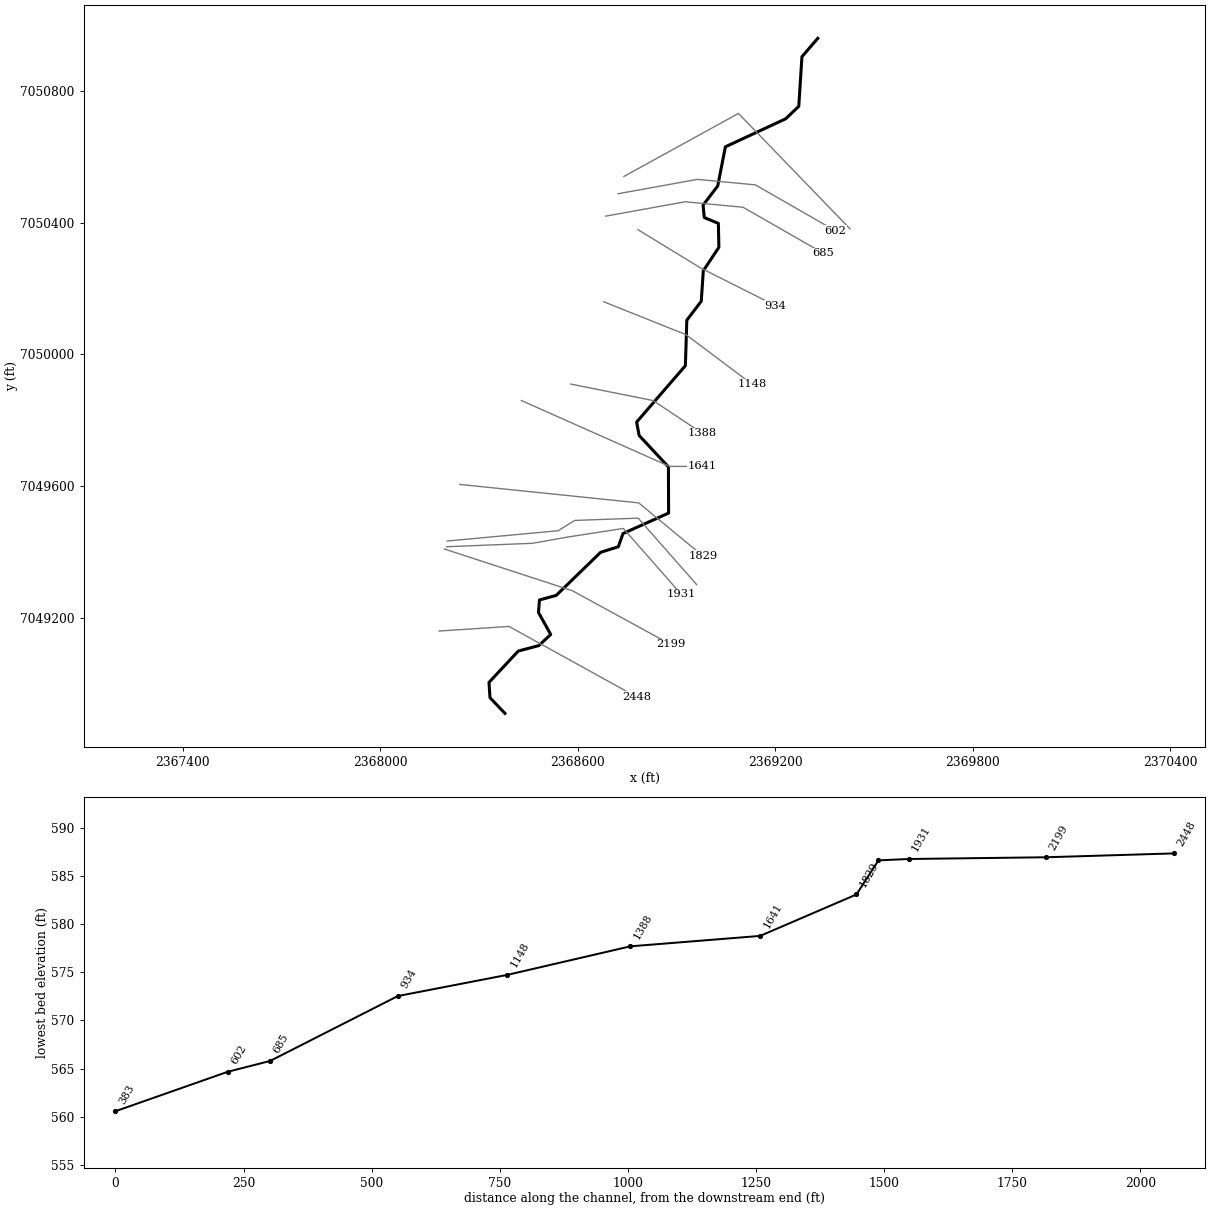
--- Marshall Branch Tr 2.prj (project) ---

Proj Title=Marshall Branch Tr 2 Base Level Engineering
Current Plan=p01
Default Exp/Contr=0.3,0.1
English Units
Geom File=g01
Flow File=f01
Plan File=p01
Y Axis Title=Elevation
X Axis Title(PF)=Main Channel Distance
X Axis Title(XS)=Station
BEGIN DESCRIPTION:
Marshall Branch Tr 2
END DESCRIPTION:
DSS Export Rating Curves= 0
DSS Export Rating Curve Sorted= 0
DSS Export Volume Flow Curves= 0
DXF OffsetX= 0
DXF OffsetY= 0
DXF ScaleX= 1
DXF ScaleY= 10

--- Marshall Branch Tr 2.p01 (plan) ---

Plan Title=Multiple Run
Program Version=4.10
Short Identifier=Multiple
Geom File=g01
Flow File=f01
Subcritical Flow
K Sum by GR= 0
Std Step Tol= 0.01
Critical Tol= 0.01
Num of Std Step Trials= 20
Max Error Tol= 0.3
Flow Tol Ratio= 0.001
Split Flow NTrial= 30
Split Flow Tol= 0.02
Split Flow Ratio= 0.02
Log Output Level= 0
Friction Slope Method= 1
Unsteady Friction Slope Method= 2
Unsteady Bridges Friction Slope Method= 1
Parabolic Critical Depth
Global Vel Dist= 1 , 1 , 1
Global Log Level= 0
CheckData=True
Encroach Param=-1 ,0,0, 0
BEGIN DESCRIPTION:
Multiple Run
END DESCRIPTION:
Computation Interval=1HOUR
Output Interval=1HOUR
Run HTab= 0
Run UNet= 0
Run PostProcess= 0
Run WQNet= 0
UNET Theta= 1
UNET Theta Warmup= 1
UNET ZTol= 0.02
UNET ZSATol= 0.05
UNET MxIter= 20
UNET MaxInSteps= 0
UNET DtIC= 0
UNET DtMin= 0
UNET MaxCRTS= 20
UNET WFStab= 2
UNET SFStab= 1
UNET WFX= 1
UNET SFX= 1
UNET DSS MLevel= 4
UNET DZMax Abort= 100
UNET Convert EG Bridges= 0
UNET Use Existing IB Tables=-1
UNET Froude Reduction=False
UNET Froude Limit= 1
UNET Froude Power= 10
UNET Time Slicing=0,0, 5
UNET Junction Losses=0
Instantaneous Interval=1HOUR
Write IC File= 0
Write IC File at Sim End=0
Echo Input=False
Echo Parameters=False
Echo Output=False
Write Detailed= 0
WQ AD Non Conservative
WQ ULTIMATE=-1
WQ Max Comp Step=1HOUR
WQ Output Interval=15MIN
WQ Output Selected Increments= 0
WQ Output face flow=0
WQ Output face velocity=0
WQ Output face area=0
WQ Output face dispersion=0
WQ Output cell volume=0
WQ Output cell surface area=0
WQ Output cell continuity=0
WQ Output cumulative cell continuity=0
WQ Output face conc=0
WQ Output face dconc_dx=0
WQ Output face courant=0
WQ Output face peclet=0
WQ Output face adv mass=0
WQ Output face disp mass=0
WQ Output cell mass=0
WQ Output cell source sink temp=0
WQ Output cell source sink nsm=0
WQ Output MaxMinRange=-1
WQ Daily Max Min Mean=-1
WQ Daily Range=0
WQ Daily Time=0
WQ Create Restart=0
WQ Fixed Restart=0
WQ System Summary=0
WQ Use Fixed Temperature=0
Sorting and Armoring Iterations= 10
XS Update Threshold= 0.02
Hydraulics Update Threshold= 0.02
Energy Slope Method= 1
Volume Change Method= 0
XS Weighting Method= 0
Number of US Weighted Cross Sections= 1
Number of DS Weighted Cross Sections= 1
Upstream XS Weight=0.25
Main XS Weight=0.5
Downstream XS Weight=0.25
Number of DS XS's Weighted with US Boundary= 1
Upstream Boundary Weight= 1
Weight of XSs Associated with US Boundary= 0
Number of US XS's Weighted with DS Boundary= 1
Downstream Boundary Weight= 0.5
Weight of XSs Associated with DS Boundary= 0.5
Sediment Output Level= 4
Mass or Volume Output= 0
Output Increment Type= 1
Profile and TS Output Increment= 10
XS Output Flag= 0
XS Output Increment= 10
Disregard all LS=0
Disregard all Conn=0
Disregard all Breaches=0
Disregard all Pumps=0

--- Marshall Branch Tr 2.f01 (steady flow) ---

Flow Title=Multiple
Number of Profiles=7
Profile Names=10-year,25-year,50-year,1pct_min,100-year,1pct_plu,500-year
River Rch & RM= Marshall Branch ,Reach-1,2448
     307     400     474     279     557    1111     766
Boundary for River Rch & Prof#=Marshall Branch ,Reach-1,1
Up Type=0
Dn Type=3
Dn Slope=0.005
Boundary for River Rch & Prof#=Marshall Branch ,Reach-1,2
Up Type=0
Dn Type=3
Dn Slope=0.005
Boundary for River Rch & Prof#=Marshall Branch ,Reach-1,3
Up Type=0
Dn Type=3
Dn Slope=0.005
Boundary for River Rch & Prof#=Marshall Branch ,Reach-1,4
Up Type=0
Dn Type=3
Dn Slope=0.005
Boundary for River Rch & Prof#=Marshall Branch ,Reach-1,5
Up Type=0
Dn Type=3
Dn Slope=0.005
Boundary for River Rch & Prof#=Marshall Branch ,Reach-1,6
Up Type=0
Dn Type=3
Dn Slope=0.005
Boundary for River Rch & Prof#=Marshall Branch ,Reach-1,7
Up Type=0
Dn Type=3
Dn Slope=0.005

--- Marshall Branch Tr 2.g01 (geometry) ---

Geom Title=Existing Conditions

River Reach=Marshall Branch ,Reach-1
Reach XY= 30
      2368379.00      7048910.00      2368333.57      7048957.65
      2368330.53      7049004.04      2368419.33      7049099.23
      2368481.84      7049115.85      2368518.01      7049149.64
      2368480.83      7049216.42      2368483.81      7049254.38
      2368534.65      7049268.28      2368669.57      7049399.15
      2368723.23      7049415.99      2368737.62      7049456.16
      2368875.95      7049518.28      2368875.46      7049658.52
      2368786.48      7049753.96      2368778.89      7049794.64
      2368926.93      7049965.86      2368931.27      7050104.06
      2368975.14      7050161.60      2368981.36      7050254.03
      2369028.66      7050325.40      2369027.10      7050398.00
      2368984.22      7050415.79      2368980.72      7050453.52
      2369025.10      7050511.56      2369048.46      7050630.54
      2369231.58      7050715.71      2369271.30      7050753.52
      2369280.91      7050904.21      2369329.00      7050960.00

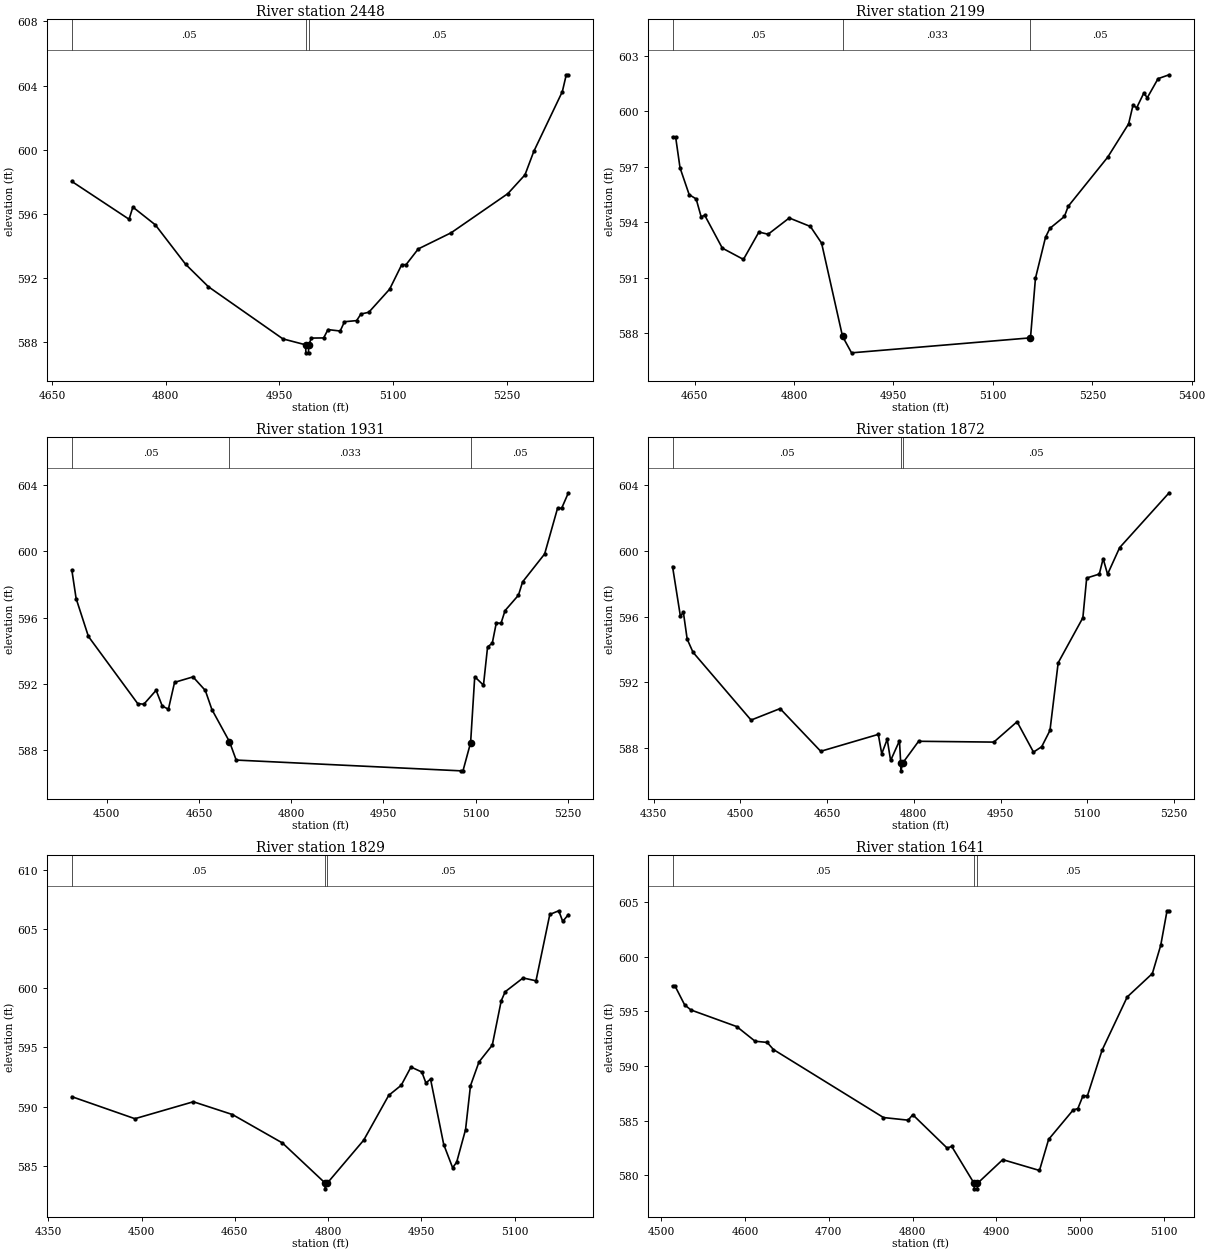
Type RM Length L Ch R = 1,2448,249,249,249
BEGIN DESCRIPTION:
Marshall Branch Tr 2 7.0
END DESCRIPTION:
XS GIS Cut Line= 3
      2368178.99      7049160.00      2368391.36      7049173.99
      2368778.99      7048960.01
#Sta/Elev= 30
  4676.0  598.02  4751.6  595.66  4756.6  596.42  4786.3  595.31  4826.3  592.85
  4856.4  591.45  4954.7  588.20  4984.7  587.83  4985.0  587.33  4988.5  587.33
  4988.7  587.83  4992.4  588.25  5008.5  588.26  5014.2  588.78  5030.3  588.69
  5036.0  589.27  5052.0  589.34  5057.7  589.75  5068.1  589.86  5095.6  591.30
  5111.6  592.83  5117.3  592.83  5133.4  593.81  5176.9  594.82  5251.7  597.26
  5274.3  598.43  5285.9  599.89  5323.6  603.62  5328.8  604.67  5331.6  604.67
#Mann=3,-1,0
  4676.0    0.05       0  4984.7   0.033       0  4988.7    0.05       0
Bank Sta=4984.7,4988.7
Exp/Cntr=0.3,0.1

Type RM Length L Ch R = 1,2199,268,268,268
BEGIN DESCRIPTION:
Marshall Branch Tr 2 6.0
END DESCRIPTION:
XS GIS Cut Line= 3
      2368195.13      7049409.11      2368583.97      7049282.39
      2368882.61      7049119.18
#Sta/Elev= 30
  4616.6  598.61  4621.2  598.61  4627.9  596.93  4641.7  595.48  4652.2  595.25
  4659.8  594.28  4665.1  594.37  4691.7  592.59  4723.6  591.98  4746.9  593.46
  4760.8  593.34  4792.7  594.22  4824.6  593.76  4841.5  592.86  4873.1  587.82
  4886.7  586.93  5156.7  587.74  5164.2  590.96  5179.4  593.18  5186.0  593.66
  5207.9  594.30  5213.6  594.85  5273.3  597.51  5304.8  599.31  5311.3  600.30
  5317.0  600.18  5327.4  600.95  5333.1  600.73  5349.2  601.75  5365.9  601.96
#Mann=3,-1,0
  4616.6    0.05       0  4873.1   0.033       0  5156.7    0.05       0
Bank Sta=4873.1,5156.7
Exp/Cntr=0.3,0.1

Type RM Length L Ch R = 1,1931,59,59,59
BEGIN DESCRIPTION:
Marshall Branch Tr 2 5.1
END DESCRIPTION:
XS GIS Cut Line= 5
      2368202.03      7049416.07      2368462.45      7049426.48
      2368570.09      7049445.58      2368738.49      7049471.62
      2368914.95      7049271.05
#Sta/Elev= 30
  4443.3  598.88  4450.3  597.15  4470.3  594.86  4550.4  590.81  4560.4  590.77
  4580.4  591.61  4590.4  590.66  4600.4  590.47  4610.4  592.09  4640.4  592.42
  4660.4  591.60  4671.1  590.45  4699.7  588.51  4710.6  587.40  5075.9  586.75
  5079.4  586.75  5091.8  588.45  5098.5  592.43  5112.7  591.92  5119.4  594.23
  5127.0  594.45  5133.6  595.68  5141.2  595.65  5147.8  596.42  5169.6  597.35
  5176.3  598.15  5212.2  599.84  5233.2  602.60  5239.9  602.60  5250.8  603.53
#Mann=3,-1,0
  4443.3    0.05       0  4699.7   0.033       0  5091.8    0.05       0
Bank Sta=4699.7,5091.8
Exp/Cntr=0.3,0.1

Type RM Length L Ch R = 1,1872,43,43,43
BEGIN DESCRIPTION:
Marshall Branch Tr 2 5.0
END DESCRIPTION:
XS GIS Cut Line= 5
      2368203.78      7049433.43      2368540.57      7049464.68
      2368590.92      7049495.93      2368783.63      7049502.87
      2368961.03      7049301.23
#Sta/Elev= 30
  4382.7  599.05  4396.3  596.02  4401.4  596.27  4408.0  594.63  4418.1  593.83
  4518.5  589.70  4568.7  590.40  4639.0  587.80  4738.6  588.83  4744.5  587.65
  4754.0  588.53  4759.9  587.24  4775.2  588.44  4777.3  587.11  4777.6  586.61
  4781.3  587.11  4808.3  588.41  4938.4  588.36  4978.6  589.60  5007.0  587.75
  5021.2  588.08  5035.5  589.07  5049.7  593.19  5092.4  595.93  5099.0  598.35
  5120.8  598.59  5127.5  599.53  5135.1  598.58  5156.0  600.20  5241.6  603.54
#Mann=3,-1,0
  4382.7    0.05       0  4777.3   0.033       0  4781.3    0.05       0
Bank Sta=4777.3,4781.3
Exp/Cntr=0.3,0.1

Type RM Length L Ch R = 1,1829,188,188,188
BEGIN DESCRIPTION:
Marshall Branch Tr 2 4.9
END DESCRIPTION:
XS GIS Cut Line= 3
      2368241.96      7049605.30      2368785.12      7049549.29
      2368979.83      7049388.27
#Sta/Elev= 30
  4387.9  590.85  4489.4  588.99  4583.4  590.42  4646.3  589.34  4726.7  586.94
  4795.1  583.57  4795.3  583.07  4799.1  583.57  4857.4  587.18  4897.6  590.96
  4917.7  591.81  4933.4  593.35  4950.9  592.93  4957.4  592.01  4964.9  592.33
  4986.1  586.81  5000.4  584.85  5006.9  585.32  5021.2  588.07  5029.1  591.77
  5042.8  593.78  5064.2  595.20  5078.6  598.95  5085.0  599.71  5113.7  600.87
  5134.5  600.63  5156.7  606.23  5171.1  606.54  5177.5  605.64  5186.6  606.22
#Mann=3,-1,0
  4387.9    0.05       0  4795.1   0.033       0  4799.1    0.05       0
Bank Sta=4795.1,4799.1
Exp/Cntr=0.3,0.1

Type RM Length L Ch R = 1,1641,253,253,253
BEGIN DESCRIPTION:
Marshall Branch Tr 2 4.0
END DESCRIPTION:
XS GIS Cut Line= 3
      2368428.97      7049860.01      2368879.00      7049660.00
      2368979.02      7049660.00
#Sta/Elev= 30
  4513.5  597.34  4516.3  597.34  4527.9  595.60  4535.4  595.13  4590.1  593.61
  4612.0  592.27  4626.4  592.16  4633.9  591.51  4765.2  585.29  4794.6  585.05
  4800.1  585.55  4841.1  582.50  4846.6  582.65  4873.3  579.27  4873.6  578.77
  4877.1  578.77  4877.3  579.27  4907.5  581.44  4951.3  580.45  4962.2  583.29
  4991.6  585.99  4997.1  586.11  5003.2  587.28  5008.5  587.28  5026.0  591.45
  5056.0  596.32  5086.0  598.46  5096.0  601.05  5103.5  604.20  5106.0  604.20
#Mann=3,-1,0
  4513.5    0.05       0  4873.3   0.033       0  4877.3    0.05       0
Bank Sta=4873.3,4877.3
Exp/Cntr=0.3,0.1

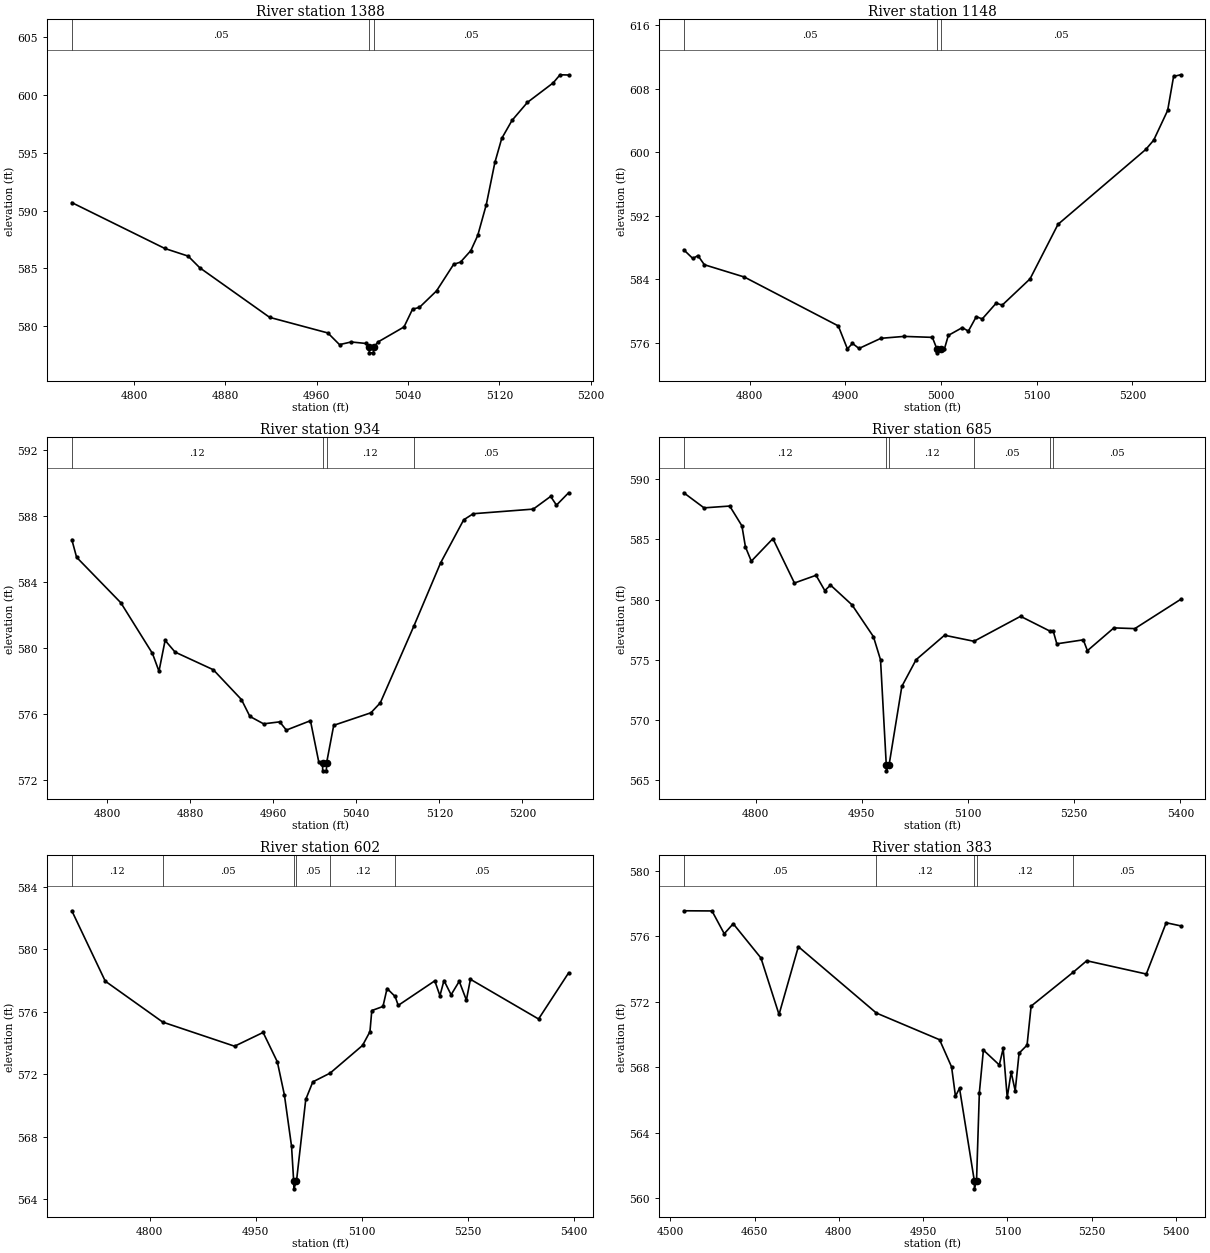
Type RM Length L Ch R = 1,1388,240,240,240
BEGIN DESCRIPTION:
Marshall Branch Tr 2 3.0
END DESCRIPTION:
XS GIS Cut Line= 3
      2368579.05      7049909.99      2368829.00      7049860.00
      2368979.02      7049759.99
#Sta/Elev= 30
  4745.4  590.69  4826.9  586.72  4847.3  586.06  4857.5  585.05  4918.7  580.76
  4969.7  579.41  4979.9  578.40  4990.1  578.63  5003.3  578.50  5005.8  578.19
  5006.1  577.69  5009.6  577.69  5009.8  578.19  5013.8  578.64  5036.4  579.93
  5043.9  581.47  5049.9  581.62  5064.9  583.05  5079.9  585.35  5085.9  585.54
  5094.9  586.53  5101.0  587.85  5108.5  590.52  5116.0  594.16  5122.0  596.24
  5131.0  597.80  5144.5  599.36  5167.1  601.05  5173.1  601.75  5180.6  601.73
#Mann=3,-1,0
  4745.4    0.05       0  5005.8   0.033       0  5009.8    0.05       0
Bank Sta=5005.8,5009.8
Exp/Cntr=0.3,0.1

Type RM Length L Ch R = 1,1148,214,214,214
BEGIN DESCRIPTION:
Marshall Branch Tr 2 2.0
END DESCRIPTION:
XS GIS Cut Line= 3
      2368679.02      7050159.99      2368929.00      7050060.00
      2369128.97      7049910.02
#Sta/Elev= 30
  4731.1  587.71  4740.5  586.62  4745.9  586.98  4752.6  585.83  4794.4  584.28
  4892.6  578.12  4902.1  575.23  4907.4  575.92  4914.2  575.28  4937.1  576.56
  4961.3  576.80  4990.9  576.68  4995.6  575.23  4995.9  574.73  4999.6  575.23
  5003.5  575.23  5007.6  576.93  5022.2  577.91  5028.5  577.46  5036.8  579.29
  5043.0  579.00  5057.6  580.99  5063.9  580.74  5093.0  584.05  5122.2  590.92
  5213.9  600.35  5222.2  601.52  5236.8  605.27  5243.0  609.55  5250.3  609.76
#Mann=3,-1,0
  4731.1    0.05       0  4995.6   0.033       0  4999.6    0.05       0
Bank Sta=4995.6,4999.6
Exp/Cntr=0.3,0.1

Type RM Length L Ch R = 1,934,249,249,249
BEGIN DESCRIPTION:
Marshall Branch Tr 2 1.0
END DESCRIPTION:
XS GIS Cut Line= 3
      2368782.74      7050378.98      2368973.89      7050262.23
      2369201.01      7050148.03
#Sta/Elev= 30
  4766.2  586.55  4770.8  585.48  4813.4  582.72  4843.8  579.65  4850.1  578.57
  4856.0  580.44  4865.6  579.73  4902.4  578.66  4929.5  576.85  4937.6  575.83
  4950.8  575.38  4966.3  575.50  4972.7  575.00  4995.9  575.57  5003.9  573.07
  5007.5  573.03  5007.7  572.53  5011.2  572.53  5011.5  573.03  5018.3  575.29
  5054.1  576.05  5063.1  576.65  5095.6  581.33  5121.1  585.13  5143.4  587.75
  5152.6  588.12  5210.4  588.40  5227.1  589.17  5232.7  588.64  5244.4  589.39
#Mann=4,-1,0
  4766.2    0.12       0  5007.5    0.07       0  5011.5    0.12       0
  5095.6    0.05       0
Bank Sta=5007.5,5011.5
Exp/Cntr=0.3,0.1

Type RM Length L Ch R = 1,685,83,83,83
BEGIN DESCRIPTION:
Marshall Branch Tr 2 0.8
END DESCRIPTION:
XS GIS Cut Line= 4
      2368685.16      7050420.05      2368926.41      7050463.68
      2369102.20      7050447.00      2369345.03      7050307.69
#Sta/Elev= 30
  4698.5  588.85  4727.1  587.60  4763.4  587.75  4780.6  586.11  4785.6  584.36
  4793.9  583.18  4824.4  585.05  4854.8  581.37  4885.3  582.01  4897.7  580.74
  4905.7  581.20  4936.1  579.56  4966.4  576.92  4976.4  575.00  4984.5  566.30
  4984.7  565.80  4988.5  566.30  5006.5  572.80  5026.6  575.01  5066.8  577.04
  5108.4  576.54  5174.2  578.61  5215.1  577.40  5220.2  577.41  5225.4  576.33
  5262.8  576.66  5268.6  575.76  5306.0  577.65  5335.6  577.59  5400.2  580.01
#Mann=6,-1,0
  4698.5    0.12       0  4984.5    0.07       0  4988.5    0.12       0
  5108.4    0.05       0  5215.1    0.12       0  5220.2    0.05       0
Bank Sta=4984.5,4988.5
Exp/Cntr=0.3,0.1

Type RM Length L Ch R = 1,602,219,219,219
BEGIN DESCRIPTION:
Marshall Branch Tr 2 0.6
END DESCRIPTION:
XS GIS Cut Line= 4
      2368722.44      7050488.07      2368963.62      7050531.69
      2369139.41      7050515.00      2369383.17      7050375.16
#Sta/Elev= 30
  4689.9  582.45  4737.2  577.95  4818.6  575.33  4920.1  573.79  4960.5  574.67
  4980.6  572.79  4990.6  570.67  5000.7  567.39  5003.7  565.17  5004.0  564.67
  5007.7  565.17  5020.8  570.39  5030.8  571.51  5055.3  572.07  5101.1  573.84
  5111.6  574.72  5114.2  576.07  5130.0  576.33  5135.8  577.48  5147.2  576.97
  5151.6  576.40  5203.3  577.97  5210.6  577.02  5216.3  577.99  5226.4  577.08
  5237.9  577.94  5248.0  576.74  5253.7  578.07  5350.1  575.53  5392.6  578.48
#Mann=6,-1,0
  4689.9    0.12       0  4818.6    0.05       0  5003.7   0.033       0
  5007.7    0.05       0  5055.3    0.12       0  5147.2    0.05       0
Bank Sta=5003.7,5007.7
Exp/Cntr=0.3,0.1

Type RM Length L Ch R = 1,383,0,0,0
BEGIN DESCRIPTION:
Marshall Branch Tr 2 0.3
END DESCRIPTION:
XS GIS Cut Line= 3
      2368740.36      7050540.66      2369088.08      7050731.85
      2369426.82      7050381.56
#Sta/Elev= 30
  4524.0  577.55  4574.2  577.54  4596.0  576.15  4612.0  576.76  4661.3  574.67
  4693.5  571.22  4727.9  575.36  4866.7  571.31  4979.2  569.68  5000.6  568.02
  5007.5  566.23  5014.7  566.72  5041.0  561.08  5041.3  560.58  5045.0  561.08
  5050.0  566.45  5057.2  569.05  5085.5  568.14  5092.4  569.15  5099.6  566.16
  5106.6  567.70  5113.8  566.56  5120.7  568.86  5134.9  569.35  5142.1  571.73
  5217.4  573.81  5241.1  574.50  5347.1  573.69  5382.5  576.82  5408.1  576.63
#Mann=5,-1,0
  4524.0    0.05       0  4866.7    0.12       0  5041.0    0.07       0
  5045.0    0.12       0  5217.4    0.05       0
Bank Sta=5041,5045
Exp/Cntr=0.3,0.1

Chan Stop Cuts=-1