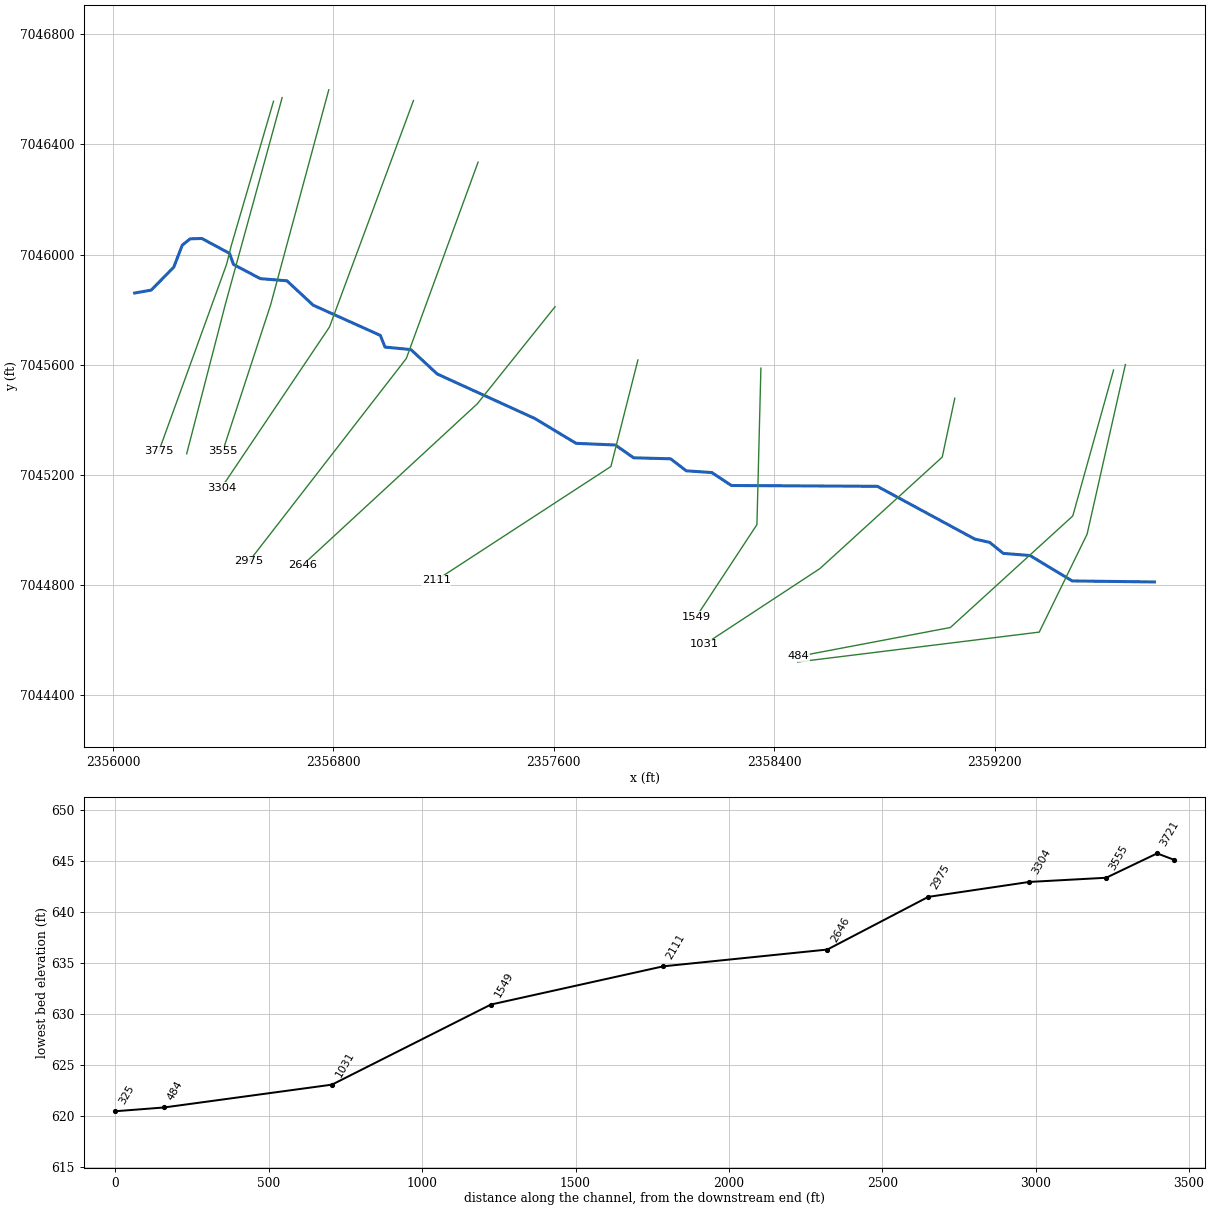
--- Marshall Branch Tr 7.prj (project) ---

Proj Title=Marshall Branch Tr 7 Base Level Engineering
Current Plan=p01
Default Exp/Contr=0.3,0.1
English Units
Geom File=g01
Flow File=f01
Plan File=p01
BEGIN DESCRIPTION:
Marshall Branch Tr 7
END DESCRIPTION:

--- Marshall Branch Tr 7.p01 (plan) ---

Plan Title=Multiple Run
Short Identifier=Multiple
Geom File=g01
Flow File=f01
Subcritical Flow
K Sum by GR= 0
Std Step Tol= 0.01
Critical Tol= 0.01
Num of Std Step Trials= 20
Max Error Tol= 0.3
Flow Tol Ratio= 0.001
Split Flow NTrial= 30
Split Flow Tol= 0.02
Split Flow Ratio= 0.02
Log Output Level= 0
Friction Slope Method= 1
Unsteady Friction Slope Method= 2
Unsteady Bridges Friction Slope Method= 1
Parabolic Critical Depth
Global Vel Dist=  1 , 1 , 1
Global Log Level= 0
CheckData=True
Encroach Param= -1, 0, 0, 0
BEGIN DESCRIPTION:
Multiple Run
END DESCRIPTION:

--- Marshall Branch Tr 7.f01 (steady flow) ---

Flow Title=Multiple
Number of Profiles=7
Profile Names=10-year,25-year,50-year,1pct_min,100-year,1pct_plu,500-year
River Rch & RM= Marshall Branch ,Reach-1,3775
     476     636     765     457     911    1818    1291
River Rch & RM= Marshall Branch ,Reach-1,1549
     516     693     836     501     999    1993    1424
Boundary for River Rch & Prof#=Marshall Branch ,Reach-1,1
Up Type=0
Dn Type=3
Dn Slope=0.005
Boundary for River Rch & Prof#=Marshall Branch ,Reach-1,2
Up Type=0
Dn Type=3
Dn Slope=0.005
Boundary for River Rch & Prof#=Marshall Branch ,Reach-1,3
Up Type=0
Dn Type=3
Dn Slope=0.005
Boundary for River Rch & Prof#=Marshall Branch ,Reach-1,4
Up Type=0
Dn Type=3
Dn Slope=0.005
Boundary for River Rch & Prof#=Marshall Branch ,Reach-1,5
Up Type=0
Dn Type=3
Dn Slope=0.005
Boundary for River Rch & Prof#=Marshall Branch ,Reach-1,6
Up Type=0
Dn Type=3
Dn Slope=0.005
Boundary for River Rch & Prof#=Marshall Branch ,Reach-1,7
Up Type=0
Dn Type=3
Dn Slope=0.005

--- Marshall Branch Tr 7.g01 (geometry) ---

Geom Title=Existing Conditions

River Reach=Marshall Branch ,Reach-1
Reach XY= 30
      2356079.00      7045860.00      2356138.82      7045870.50
      2356220.85      7045953.96      2356251.86      7046034.09
      2356280.42      7046056.97      2356322.86      7046058.26
      2356423.24      7046004.05      2356437.62      7045963.84
      2356534.94      7045912.33      2356631.42      7045904.46
      2356726.71      7045815.85      2356970.36      7045706.10
      2356987.19      7045663.66      2357081.36      7045654.44
      2357176.71      7045565.85      2357531.20      7045403.92
      2357680.56      7045313.76      2357823.06      7045307.73
      2357889.51      7045261.23      2358023.47      7045257.61
      2358080.60      7045213.86      2358173.02      7045207.64
      2358244.22      7045160.52      2358773.48      7045157.65
      2359126.80      7044966.08      2359181.18      7044953.88
      2359230.58      7044913.83      2359327.42      7044906.17
      2359480.55      7044813.75      2359779.00      7044810.00

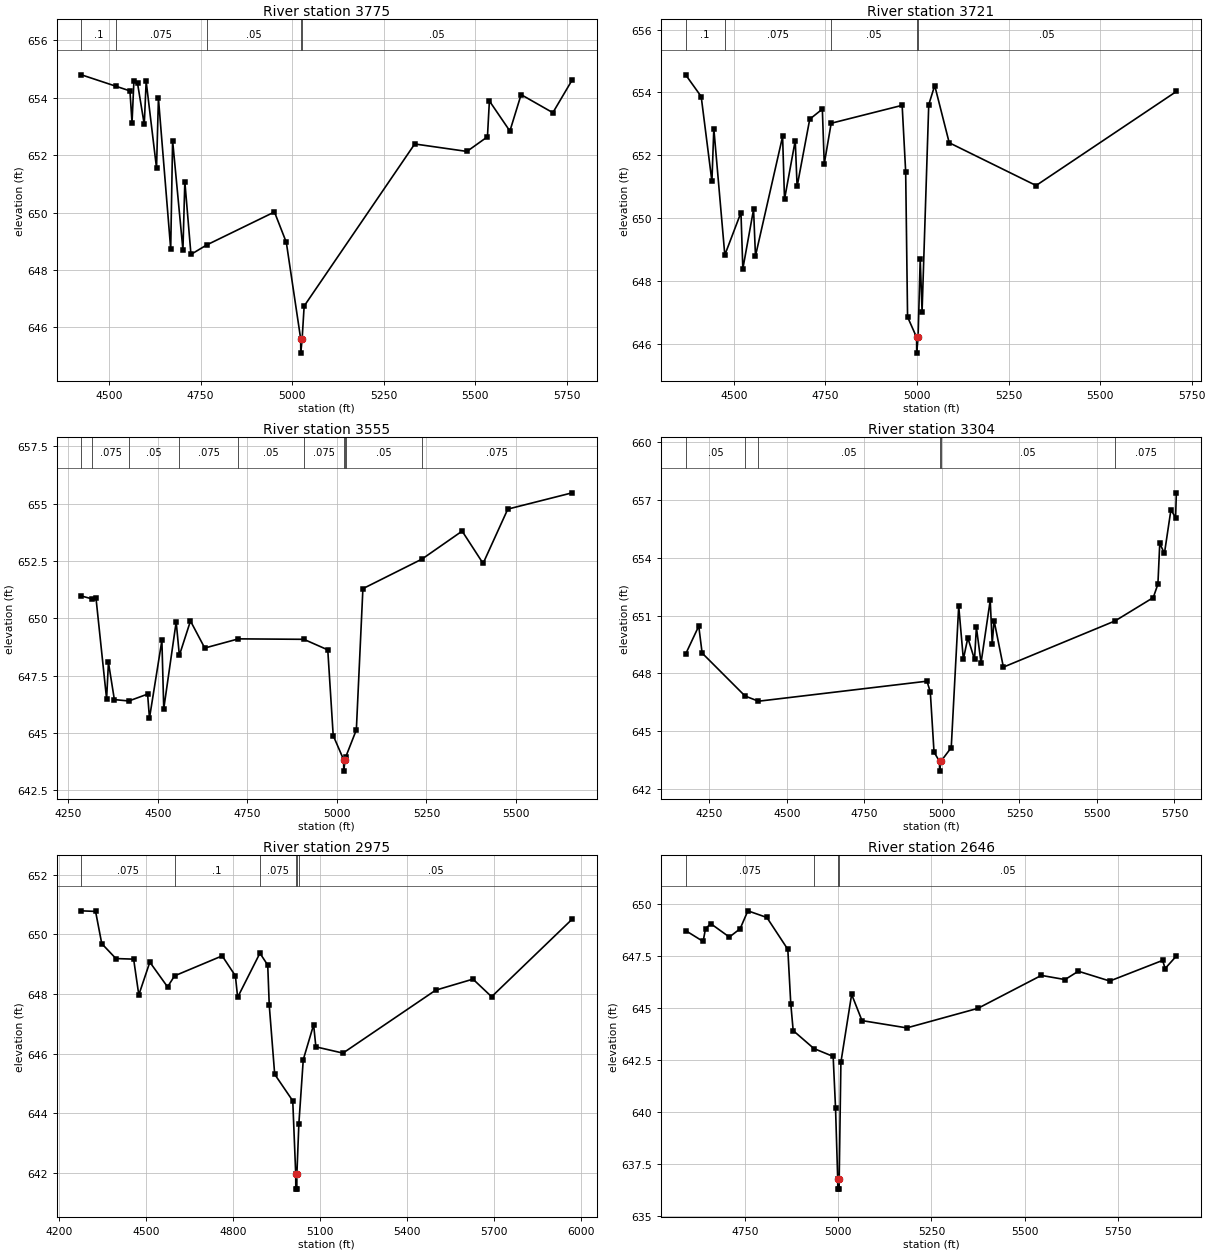
Type RM Length L Ch R = 1,3775,54,54,54
BEGIN DESCRIPTION:
Marshall Branch Tr 7 9.0
END DESCRIPTION:
XS GIS Cut Line= 4
      2356582.85      7046557.05      2356429.20      7046031.01
      2356412.45      7045964.23      2356166.44      7045284.33
#Sta/Elev= 30
  4424.7  654.80  4519.4  654.40  4557.1  654.24  4562.8  653.13  4568.0  654.60
  4577.9  654.50  4596.2  653.07  4601.4  654.57  4629.7  651.55  4634.9  653.98
  4668.4  648.73  4673.6  652.51  4701.8  648.70  4707.0  651.08  4723.7  648.54
  4766.7  648.87  4951.7  650.02  4984.1  648.96  5023.3  645.60  5023.6  645.10
  5027.3  645.60  5032.8  646.74  5334.7  652.39  5477.3  652.13  5533.3  652.64
  5538.6  653.89  5594.6  652.84  5625.2  654.11  5711.9  653.48  5764.6  654.62
#Mann=5,-1,0
  4424.7     0.1       0  4519.4   0.075       0  4766.7    0.05       0
  5023.3    0.05       0  5027.3    0.05       0
Bank Sta=5023.3,5027.3
Exp/Cntr=0.3,0.1

Type RM Length L Ch R = 1,3721,166,166,166
BEGIN DESCRIPTION:
Marshall Branch Tr 7 8.0
END DESCRIPTION:
XS GIS Cut Line= 3
      2356614.09      7046570.03      2356408.37      7045820.07
      2356267.75      7045275.80
#Sta/Elev= 30
  4368.5  654.56  4410.9  653.87  4440.2  651.17  4445.4  652.85  4475.4  648.83
  4519.5  650.18  4524.6  648.39  4553.9  650.28  4559.1  648.80  4633.2  652.60
  4638.4  650.60  4667.7  652.47  4672.8  651.01  4707.3  653.15  4741.7  653.47
  4746.9  651.73  4765.8  653.02  4959.6  653.59  4969.2  651.48  4974.4  646.86
  4999.1  646.21  4999.3  645.71  5003.1  646.21  5008.9  648.70  5014.0  647.03
  5032.2  653.61  5048.5  654.22  5088.1  652.40  5325.3  651.04  5708.3  654.03
#Mann=5,-1,0
  4368.5     0.1       0  4475.4   0.075       0  4765.8    0.05       0
  4999.1    0.05       0  5003.1    0.05       0
Bank Sta=4999.1,5003.1
Exp/Cntr=0.3,0.1

Type RM Length L Ch R = 1,3555,251,251,251
BEGIN DESCRIPTION:
Marshall Branch Tr 7 7.0
END DESCRIPTION:
XS GIS Cut Line= 3
      2356783.38      7046598.74      2356572.43      7045817.47
      2356398.17      7045284.27
#Sta/Elev= 30
  4286.8  650.97  4317.1  650.84  4327.4  650.88  4357.0  646.48  4362.2  648.07
  4378.7  646.45  4419.1  646.39  4471.5  646.69  4476.7  645.64  4511.4  649.03
  4516.6  646.05  4551.3  649.84  4560.2  648.38  4591.2  649.88  4631.1  648.70
  4725.2  649.10  4907.8  649.08  4974.6  648.62  4989.8  644.88  5018.9  643.83
  5019.2  643.33  5022.9  643.83  5024.3  643.93  5054.4  645.13  5072.7  651.29
  5237.7  652.58  5349.8  653.80  5408.3  652.39  5477.3  654.76  5657.0  655.47
#Mann=10,-1,0
  4286.8     0.1       0  4317.1   0.075       0  4419.1    0.05       0
  4560.2   0.075       0  4725.2    0.05       0  4907.8   0.075       0
  5018.9    0.07       0  5022.9   0.075       0  5024.3    0.05       0
  5237.7   0.075       0
Bank Sta=5018.9,5022.9
Exp/Cntr=0.3,0.1

Type RM Length L Ch R = 1,3304,329,329,329
BEGIN DESCRIPTION:
Marshall Branch Tr 7 6.0
END DESCRIPTION:
XS GIS Cut Line= 3
      2357090.65      7046559.62      2356785.97      7045736.74
      2356393.38      7045151.74
#Sta/Elev= 30
  4174.1  649.00  4216.3  650.45  4227.2  649.05  4365.6  646.82  4408.8  646.55
  4952.1  647.59  4962.8  647.03  4974.8  643.91  4992.6  643.42  4992.8  642.92
  4996.6  643.42  5030.3  644.14  5054.4  651.49  5069.4  648.73  5083.8  649.84
  5105.4  648.72  5111.4  650.39  5126.4  648.54  5156.0  651.79  5162.4  649.53
  5168.4  650.74  5198.4  648.32  5558.6  650.72  5681.6  651.93  5696.6  652.63
  5702.6  654.75  5717.6  654.22  5738.6  656.49  5753.6  656.08  5756.1  657.37
#Mann=6,-1,0
  4174.1    0.05       0  4365.6   0.075       0  4408.8    0.05       0
  4992.6   0.033       0  4996.6    0.05       0  5558.6   0.075       0
Bank Sta=4992.6,4996.6
Exp/Cntr=0.3,0.1

Type RM Length L Ch R = 1,2975,329,329,329
BEGIN DESCRIPTION:
Marshall Branch Tr 7 5.0
END DESCRIPTION:
XS GIS Cut Line= 3
      2357325.05      7046335.72      2357064.62      7045622.15
      2356494.30      7044885.16
#Sta/Elev= 30
  4276.9  650.79  4325.6  650.77  4346.9  649.69  4395.7  649.19  4456.8  649.17
  4474.6  647.97  4512.6  649.07  4573.7  648.24  4597.9  648.61  4762.0  649.28
  4807.5  648.61  4815.3  647.89  4892.1  649.37  4919.0  648.97  4924.3  647.62
  4943.0  645.31  5005.3  644.42  5015.5  641.96  5015.8  641.46  5019.3  641.46
  5019.5  641.96  5026.4  643.66  5041.5  645.80  5077.2  646.97  5085.0  646.23
  5178.3  646.02  5497.9  648.13  5626.5  648.50  5690.8  647.91  5968.4  650.51
#Mann=6,-1,0
  4276.9   0.075       0  4597.9     0.1       0  4892.1   0.075       0
  5015.5    0.07       0  5019.5   0.075       0  5026.4    0.05       0
Bank Sta=5015.5,5019.5
Exp/Cntr=0.3,0.1

Type RM Length L Ch R = 1,2646,535,535,535
BEGIN DESCRIPTION:
Marshall Branch Tr 7 4.0
END DESCRIPTION:
XS GIS Cut Line= 3
      2357604.40      7045810.26      2357322.08      7045457.36
      2356686.87      7044869.97
#Sta/Elev= 30
  4590.2  648.72  4637.1  648.20  4643.5  648.82  4657.9  649.05  4707.5  648.41
  4736.4  648.81  4757.2  649.67  4808.2  649.35  4864.4  647.82  4872.3  645.22
  4878.8  643.92  4934.3  643.06  4986.1  642.68  4992.5  640.19  4998.3  636.81
  4998.6  636.31  5002.1  636.31  5002.3  636.81  5006.9  642.40  5035.7  645.66
  5063.5  644.40  5183.8  644.05  5374.8  644.99  5544.9  646.57  5608.4  646.37
  5644.2  646.77  5728.6  646.30  5870.4  647.29  5877.2  646.90  5907.3  647.50
#Mann=4,-1,0
  4590.2   0.075       0  4934.3    0.05       0  4998.3   0.033       0
  5002.3    0.05       0
Bank Sta=4998.3,5002.3
Exp/Cntr=0.3,0.1

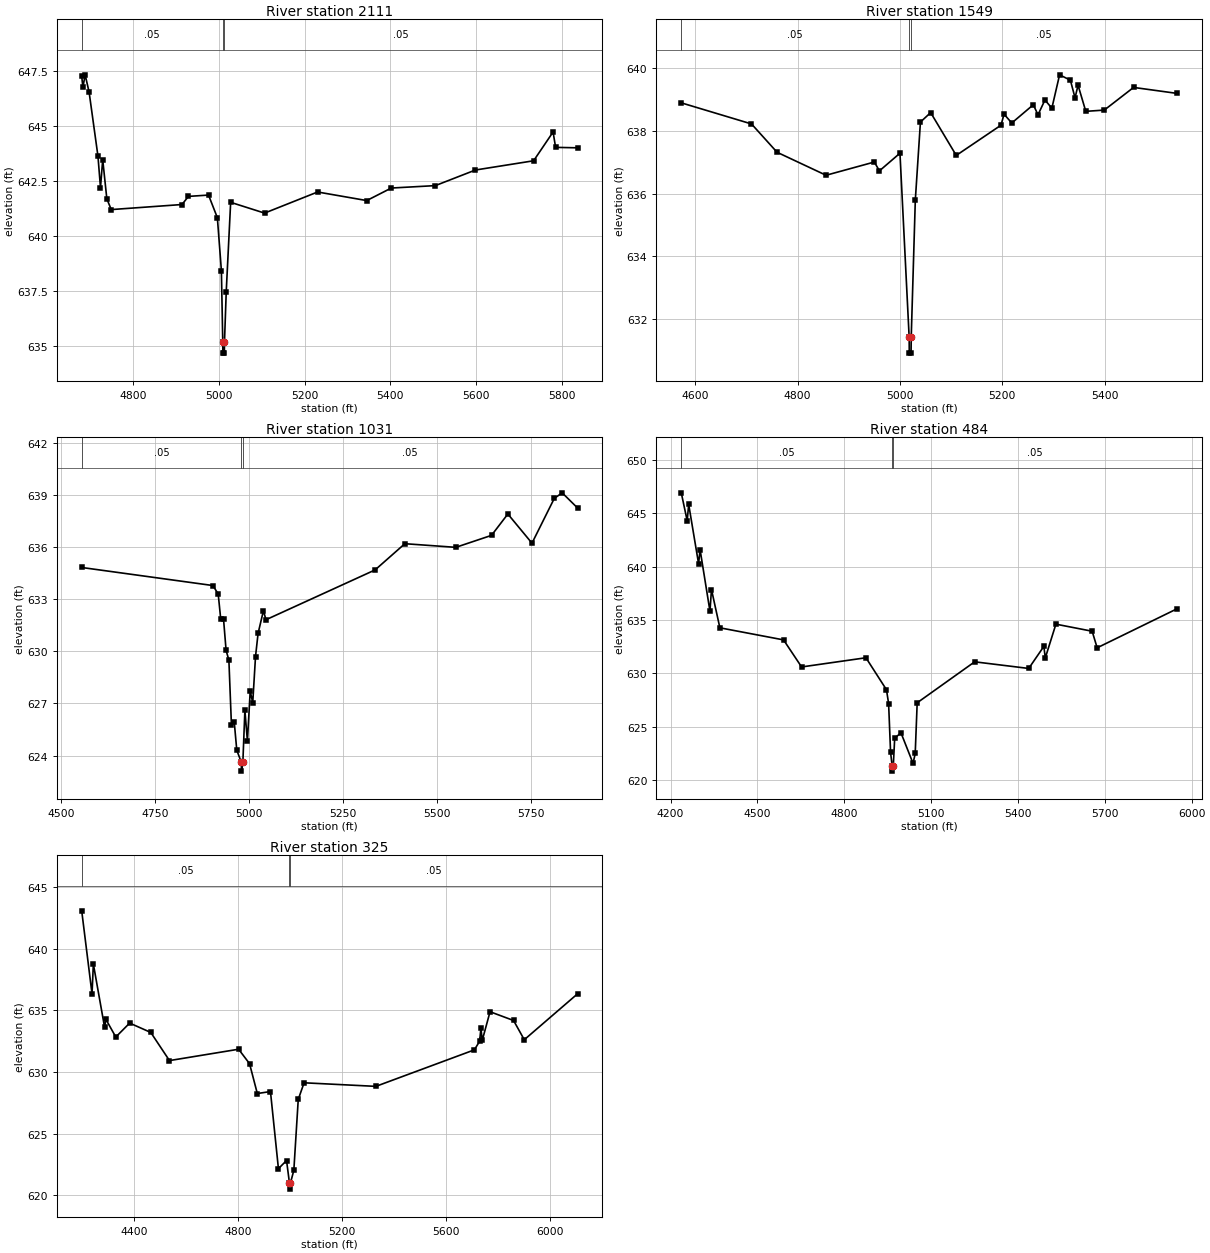
Type RM Length L Ch R = 1,2111,562,562,562
BEGIN DESCRIPTION:
Marshall Branch Tr 7 3.0
END DESCRIPTION:
XS GIS Cut Line= 3
      2357904.93      7045616.78      2357807.02      7045229.69
      2357172.90      7044816.03
#Sta/Elev= 30
  4680.0  647.26  4682.8  646.76  4688.0  647.33  4697.3  646.54  4717.9  643.63
  4723.8  642.20  4729.0  643.47  4738.6  641.69  4748.9  641.20  4913.9  641.43
  4928.9  641.80  4975.8  641.86  4996.4  640.83  5005.8  638.42  5009.0  635.17
  5009.2  634.67  5012.7  634.67  5013.0  635.17  5017.1  637.47  5027.4  641.53
  5106.5  641.04  5230.2  642.00  5344.8  641.61  5402.1  642.18  5504.8  642.29
  5598.3  643.00  5734.0  643.42  5779.4  644.73  5785.3  644.03  5836.4  644.01
#Mann=3,-1,0
  4680.0    0.05       0  5009.0   0.033       0  5013.0    0.05       0
Bank Sta=5009,5013
Exp/Cntr=0.3,0.1

Type RM Length L Ch R = 1,1549,518,518,518
BEGIN DESCRIPTION:
Marshall Branch Tr 7 2.0
END DESCRIPTION:
XS GIS Cut Line= 3
      2358351.17      7045587.11      2358336.79      7045018.44
      2358117.24      7044684.15
#Sta/Elev= 30
  4572.7  638.88  4709.9  638.21  4759.9  637.31  4855.6  636.58  4949.9  637.00
  4959.9  636.72  5000.0  637.28  5018.0  631.43  5018.2  630.93  5021.7  630.93
  5022.0  631.43  5030.0  635.79  5040.0  638.27  5060.0  638.57  5110.0  637.21
  5197.4  638.17  5203.4  638.52  5218.5  638.24  5260.6  638.82  5269.7  638.50
  5283.3  638.97  5296.8  638.71  5311.9  639.77  5333.0  639.60  5342.1  639.04
  5348.0  639.44  5363.1  638.61  5399.3  638.65  5456.5  639.37  5541.5  639.18
#Mann=3,-1,0
  4572.7    0.05       0  5018.0   0.033       0  5022.0    0.05       0
Bank Sta=5018,5022
Exp/Cntr=0.3,0.1

Type RM Length L Ch R = 1,1031,547,547,547
BEGIN DESCRIPTION:
Marshall Branch Tr 7 1.4
END DESCRIPTION:
XS GIS Cut Line= 4
      2359054.69      7045477.90      2359009.15      7045263.84
      2358565.18      7044858.57      2358147.73      7044584.05
#Sta/Elev= 30
  4554.9  634.83  4904.1  633.79  4918.2  633.30  4925.0  631.84  4932.4  631.85
  4939.2  630.05  4946.6  629.50  4953.4  625.76  4960.8  625.95  4967.6  624.31
  4979.8  623.60  4980.0  623.10  4983.8  623.60  4989.2  626.60  4995.9  624.84
  5003.4  627.71  5010.1  627.04  5017.5  629.70  5024.3  631.03  5038.5  632.34
  5045.3  631.82  5335.8  634.69  5415.0  636.20  5550.5  635.99  5645.6  636.68
  5689.1  637.91  5753.3  636.23  5812.7  638.81  5833.7  639.13  5874.5  638.26
#Mann=3,-1,0
  4554.9    0.05       0  4979.8    0.05       0  4983.8    0.05       0
Bank Sta=4979.8,4983.8
Exp/Cntr=0.3,0.1

Type RM Length L Ch R = 1,484,159,159,159
BEGIN DESCRIPTION:
Marshall Branch Tr 7 1.2
END DESCRIPTION:
XS GIS Cut Line= 4
      2359630.69      7045580.27      2359482.71      7045049.82
      2359038.75      7044644.56      2358487.73      7044539.82
#Sta/Elev= 30
  4237.0  646.89  4257.4  644.28  4262.6  645.81  4296.8  640.26  4301.9  641.59
  4336.1  635.82  4341.3  637.85  4370.3  634.27  4590.3  633.14  4652.6  630.61
  4874.9  631.47  4945.8  628.48  4953.2  627.19  4960.0  622.63  4965.4  621.37
  4965.7  620.87  4969.4  621.37  4974.2  623.94  4995.8  624.46  5037.7  621.59
  5045.1  622.52  5051.9  627.26  5250.5  631.09  5437.2  630.47  5489.4  632.53
  5494.5  631.46  5531.1  634.61  5656.3  633.95  5673.6  632.40  5949.7  636.05
#Mann=3,-1,0
  4237.0    0.05       0  4965.4    0.04       0  4969.4    0.05       0
Bank Sta=4965.4,4969.4
Exp/Cntr=0.3,0.1

Type RM Length L Ch R = 1,325,0,0,0
BEGIN DESCRIPTION:
Marshall Branch Tr 7 1.0
END DESCRIPTION:
XS GIS Cut Line= 4
      2359673.60      7045600.04      2359534.71      7044983.71
      2359361.10      7044627.81      2358484.36      7044519.30
#Sta/Elev= 30
  4196.7  643.06  4236.5  636.32  4241.6  638.75  4284.9  633.62  4290.0  634.26
  4328.1  632.83  4381.6  633.96  4463.0  633.20  4535.0  630.92  4801.5  631.84
  4843.7  630.67  4873.6  628.25  4924.3  628.41  4955.0  622.16  4986.3  622.82
  4997.5  621.00  4997.8  620.50  5001.5  621.00  5014.4  622.03  5031.4  627.77
  5053.9  629.12  5330.6  628.83  5710.3  631.79  5730.4  632.48  5735.6  633.53
  5740.7  632.56  5770.7  634.88  5861.4  634.17  5902.7  632.61  6107.9  636.33
#Mann=3,-1,0
  4196.7    0.05       0  4997.5    0.04       0  5001.5    0.05       0
Bank Sta=4997.5,5001.5
Exp/Cntr=0.3,0.1

Chan Stop Cuts=-1