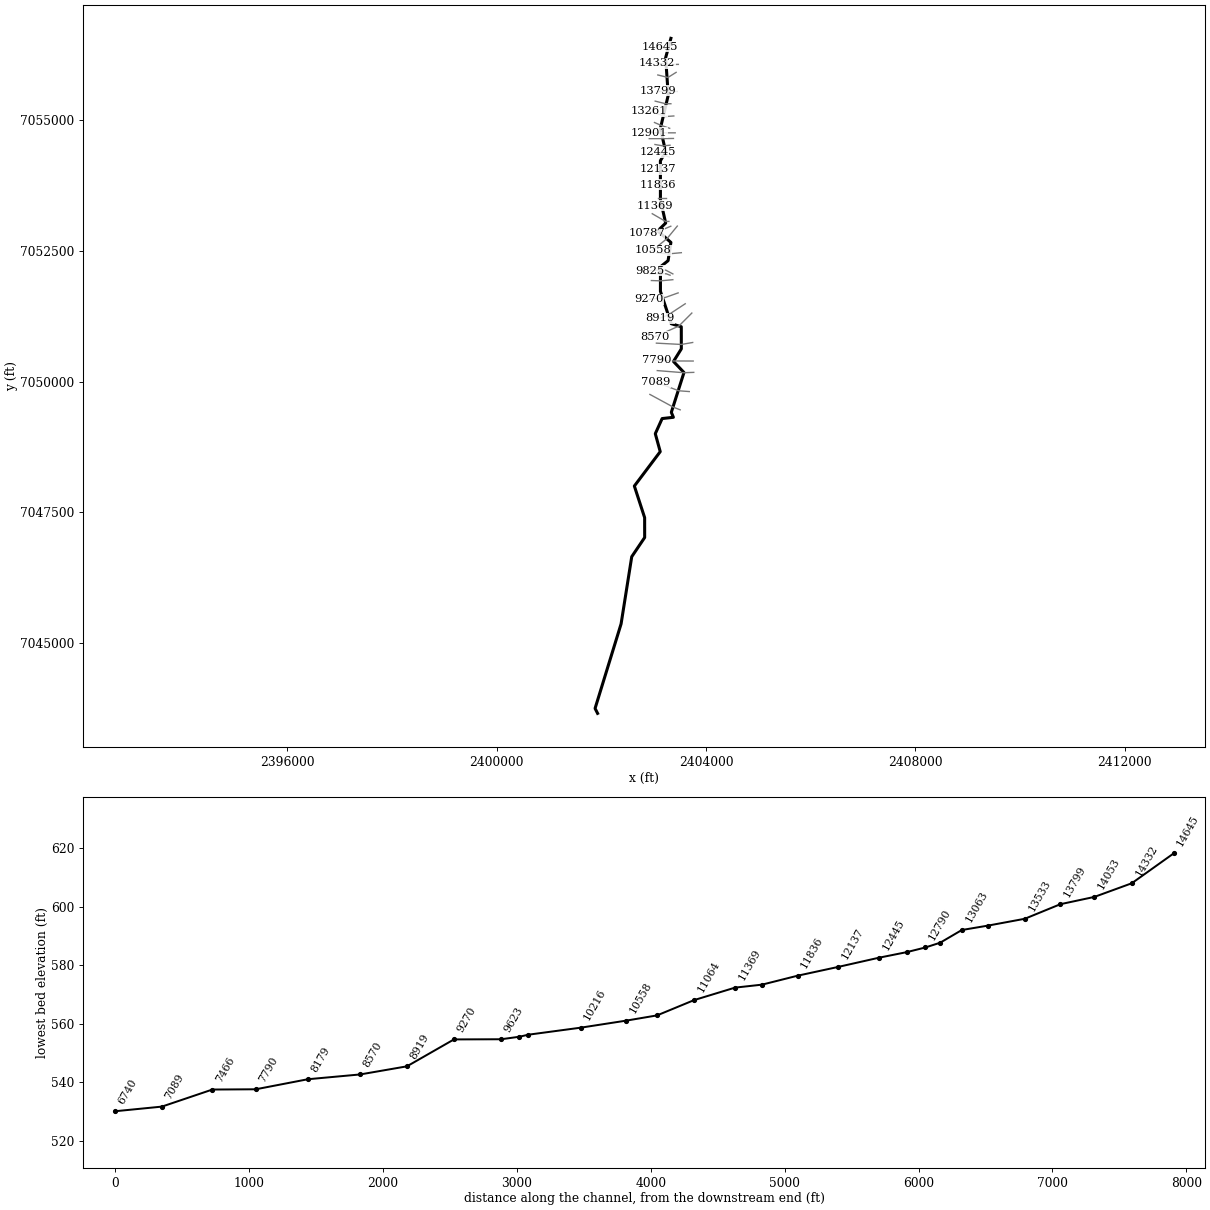
--- McKamy Creek.prj (project) ---

Proj Title=McKamy Creek Base Level Engineering
Current Plan=p01
Default Exp/Contr=0.3,0.1
English Units
Geom File=g01
Flow File=f01
Plan File=p01
BEGIN DESCRIPTION:
McKamy Creek
END DESCRIPTION:

--- McKamy Creek.p01 (plan) ---

Plan Title=Multiple Run
Short Identifier=Multiple
Geom File=g01
Flow File=f01
Subcritical Flow
K Sum by GR= 0
Std Step Tol= 0.01
Critical Tol= 0.01
Num of Std Step Trials= 20
Max Error Tol= 0.3
Flow Tol Ratio= 0.001
Split Flow NTrial= 30
Split Flow Tol= 0.02
Split Flow Ratio= 0.02
Log Output Level= 0
Friction Slope Method= 1
Unsteady Friction Slope Method= 2
Unsteady Bridges Friction Slope Method= 1
Parabolic Critical Depth
Global Vel Dist=  1 , 1 , 1
Global Log Level= 0
CheckData=True
Encroach Param= -1, 0, 0, 0
BEGIN DESCRIPTION:
Multiple Run
END DESCRIPTION:

--- McKamy Creek.f01 (steady flow) ---

Flow Title=Multiple
Number of Profiles=7
Profile Names=10-year,25-year,50-year,1pct_min,100-year,1pct_plu,500-year
River Rch & RM= McKamy Creek,Reach-1,14645
     304     401     479     284     568    1133     798
River Rch & RM= McKamy Creek,Reach-1,10216
     529     721     878     532    1061    2116    1551
River Rch & RM= McKamy Creek,Reach-1,4748
    1283    1827    2291    1422    2837    5661    4354
River Rch & RM= McKamy Creek,Reach-1,3784
    1767    2547    3220    2011    4012    8005    6236
Boundary for River Rch & Prof#=McKamy Creek,Reach-1,1
Up Type=0
Dn Type=3
Dn Slope=0.005
Boundary for River Rch & Prof#=McKamy Creek,Reach-1,2
Up Type=0
Dn Type=3
Dn Slope=0.005
Boundary for River Rch & Prof#=McKamy Creek,Reach-1,3
Up Type=0
Dn Type=3
Dn Slope=0.005
Boundary for River Rch & Prof#=McKamy Creek,Reach-1,4
Up Type=0
Dn Type=3
Dn Slope=0.005
Boundary for River Rch & Prof#=McKamy Creek,Reach-1,5
Up Type=0
Dn Type=3
Dn Slope=0.005
Boundary for River Rch & Prof#=McKamy Creek,Reach-1,6
Up Type=0
Dn Type=3
Dn Slope=0.005
Boundary for River Rch & Prof#=McKamy Creek,Reach-1,7
Up Type=0
Dn Type=3
Dn Slope=0.005

--- McKamy Creek.g01 (geometry) ---

Geom Title=Existing Conditions

River Reach=McKamy Creek,Reach-1
Reach XY= 30
      2403329.00      7056560.00      2403228.72      7056189.82
      2403278.48      7055475.22      2403128.72      7054839.82
      2403229.36      7054389.79      2403128.45      7054220.19
      2403129.09      7053475.39      2403229.10      7053029.89
      2403078.45      7052880.13      2403329.00      7052660.00
      2403275.47      7052311.45      2403129.66      7052194.17
      2403129.39      7051725.16      2403334.40      7051107.29
      2403527.52      7051048.51      2403528.32      7050625.84
      2403378.47      7050384.88      2403578.81      7050174.13
      2403337.08      7049413.28      2403376.49      7049318.11
      2403161.77      7049293.76      2403031.09      7049004.51
      2403125.33      7048661.58      2402631.17      7048004.55
      2402827.64      7047400.35      2402827.95      7047020.44
      2402581.07      7046654.14      2402377.78      7045370.50
      2401880.88      7043754.35      2401929.00      7043660.00

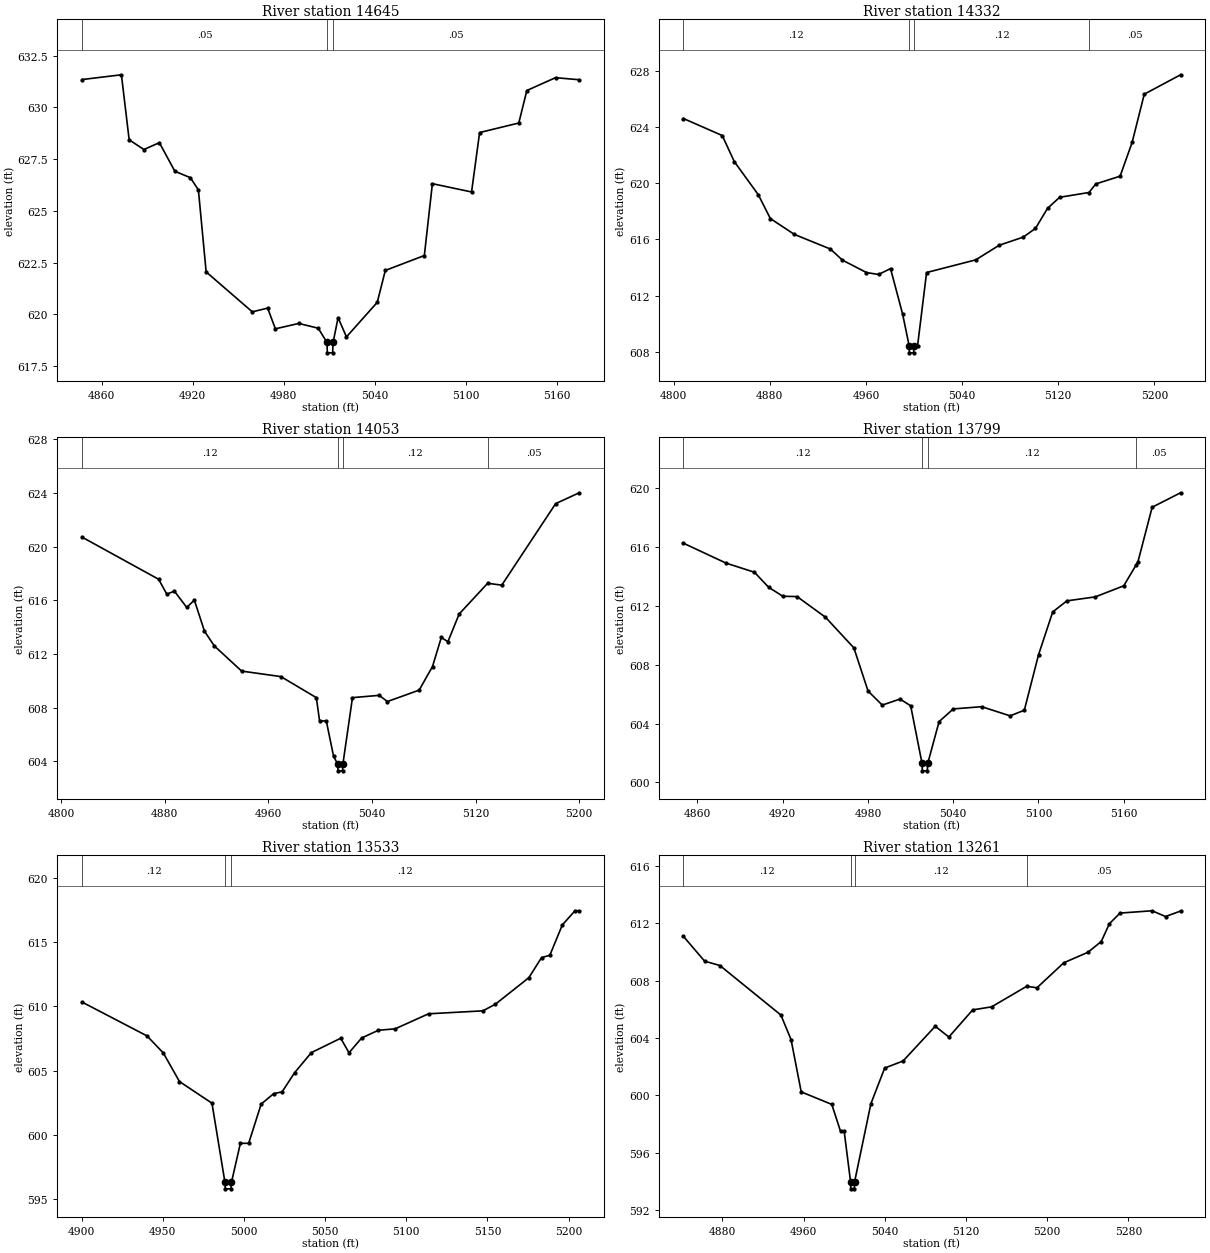
Type RM Length L Ch R = 1,14645,313,313,313
BEGIN DESCRIPTION:
McKamy Creek 41.0
END DESCRIPTION:
XS GIS Cut Line= 3
      2403428.90      7056370.25      2403279.14      7056339.89
      2403114.28      7056397.37
#Sta/Elev= 30
  4847.2  631.34  4873.1  631.57  4878.2  628.43  4887.9  627.96  4898.1  628.29
  4908.3  626.91  4918.5  626.60  4923.8  626.01  4928.9  622.05  4959.3  620.12
  4969.4  620.30  4974.5  619.30  4989.9  619.56  5002.7  619.33  5008.5  618.64
  5008.7  618.14  5012.2  618.14  5012.5  618.64  5015.8  619.84  5021.3  618.91
  5041.6  620.58  5046.9  622.12  5072.6  622.84  5077.9  626.31  5103.7  625.91
  5109.0  628.78  5134.8  629.24  5140.1  630.81  5159.0  631.43  5174.6  631.33
#Mann=3,-1,0
  4847.2    0.05       0  5008.5   0.033       0  5012.5    0.05       0
Bank Sta=5008.5,5012.5
Exp/Cntr=0.3,0.1

Type RM Length L Ch R = 1,14332,279,279,279
BEGIN DESCRIPTION:
McKamy Creek 40.0
END DESCRIPTION:
XS GIS Cut Line= 3
      2403471.26      7056062.09      2403279.00      7056060.00
      2403058.95      7056083.79
#Sta/Elev= 30
  4808.2  624.60  4840.5  623.39  4850.5  621.54  4870.5  619.18  4880.5  617.49
  4900.5  616.36  4930.5  615.32  4940.5  614.53  4960.5  613.65  4970.5  613.51
  4980.5  613.93  4990.5  610.72  4996.0  608.44  4996.2  607.94  4999.7  607.94
  5000.0  608.44  5003.0  608.44  5010.5  613.65  5051.4  614.55  5070.9  615.59
  5091.0  616.17  5101.1  616.79  5111.1  618.21  5121.2  619.00  5145.6  619.34
  5151.3  619.95  5171.5  620.50  5181.5  622.90  5191.6  626.33  5221.8  627.71
#Mann=4,-1,0
  4808.2    0.12       0  4996.0    0.07       0  5000.0    0.12       0
  5145.6    0.05       0
Bank Sta=4996,5000
Exp/Cntr=0.3,0.1

Type RM Length L Ch R = 1,14053,254,254,254
BEGIN DESCRIPTION:
McKamy Creek 39.0
END DESCRIPTION:
XS GIS Cut Line= 3
      2403429.03      7055910.02      2403273.22      7055812.35
      2403078.98      7055860.01
#Sta/Elev= 30
  4816.1  620.71  4875.2  617.57  4881.5  616.46  4887.4  616.68  4896.9  615.47
  4902.8  616.01  4910.6  613.70  4918.1  612.61  4939.3  610.72  4969.6  610.31
  4997.0  608.74  4999.5  607.00  5004.7  607.00  5010.3  604.37  5013.5  603.78
  5013.7  603.28  5017.2  603.28  5017.5  603.78  5024.9  608.74  5045.5  608.91
  5051.9  608.45  5076.4  609.30  5086.7  611.06  5093.5  613.23  5098.6  612.91
  5107.3  614.98  5129.3  617.27  5140.2  617.13  5181.8  623.21  5200.0  624.02
#Mann=4,-1,0
  4816.1    0.12       0  5013.5    0.07       0  5017.5    0.12       0
  5129.3    0.05       0
Bank Sta=5013.5,5017.5
Exp/Cntr=0.3,0.1

Type RM Length L Ch R = 1,13799,266,266,266
BEGIN DESCRIPTION:
McKamy Creek 38.0
END DESCRIPTION:
XS GIS Cut Line= 3
      2403428.98      7055560.00      2403279.00      7055560.00
      2403078.98      7055560.00
#Sta/Elev= 30
  4850.1  616.23  4880.1  614.88  4900.1  614.26  4910.1  613.24  4920.1  612.63
  4930.1  612.61  4950.1  611.21  4970.1  609.13  4980.1  606.20  4990.1  605.25
  5002.6  605.66  5010.1  605.20  5018.1  601.29  5018.3  600.79  5021.8  600.79
  5022.1  601.29  5030.1  604.13  5040.1  604.99  5060.1  605.14  5080.1  604.52
  5090.1  604.90  5100.1  608.66  5110.1  611.57  5120.1  612.32  5140.1  612.59
  5160.1  613.34  5168.9  614.77  5170.1  614.97  5180.1  618.67  5200.1  619.65
#Mann=4,-1,0
  4850.1    0.12       0  5018.1    0.07       0  5022.1    0.12       0
  5168.9    0.05       0
Bank Sta=5018.1,5022.1
Exp/Cntr=0.3,0.1

Type RM Length L Ch R = 1,13533,272,272,272
BEGIN DESCRIPTION:
McKamy Creek 37.0
END DESCRIPTION:
XS GIS Cut Line= 3
      2403329.00      7055310.00      2403229.00      7055310.00
      2403028.96      7055360.01
#Sta/Elev= 30
  4900.3  610.33  4940.3  607.70  4950.3  606.38  4960.3  604.15  4980.3  602.47
  4988.3  596.31  4988.5  595.81  4992.0  595.81  4992.3  596.31  4997.8  599.35
  5002.9  599.35  5010.6  602.40  5018.3  603.21  5023.5  603.35  5031.2  604.84
  5041.5  606.40  5059.6  607.52  5064.7  606.39  5072.5  607.54  5082.8  608.14
  5093.1  608.25  5113.7  609.42  5147.2  609.65  5154.9  610.17  5175.5  612.23
  5183.3  613.79  5188.4  613.97  5196.1  616.33  5203.9  617.43  5206.5  617.43
#Mann=3,-1,0
  4900.3    0.12       0  4988.3    0.07       0  4992.3    0.12       0
Bank Sta=4988.3,4992.3
Exp/Cntr=0.3,0.1

Type RM Length L Ch R = 1,13261,198,198,198
BEGIN DESCRIPTION:
McKamy Creek 36.0
END DESCRIPTION:
XS GIS Cut Line= 3
      2403384.79      7055076.37      2403226.83      7055065.98
      2402912.44      7055170.47
#Sta/Elev= 30
  4841.7  611.08  4862.6  609.35  4877.6  609.05  4937.7  605.60  4947.7  603.89
  4957.7  600.25  4987.8  599.38  4996.4  597.51  5000.0  597.51  5006.3  594.00
  5006.5  593.50  5010.0  593.50  5010.3  594.00  5026.3  599.42  5039.9  601.91
  5058.0  602.40  5089.7  604.82  5103.1  604.07  5126.6  605.96  5145.2  606.17
  5179.7  607.60  5189.9  607.50  5216.3  609.24  5240.1  609.97  5253.2  610.72
  5261.2  611.96  5271.7  612.70  5303.3  612.86  5316.5  612.46  5331.3  612.84
#Mann=4,-1,0
  4841.7    0.12       0  5006.3    0.07       0  5010.3    0.12       0
  5179.7    0.05       0
Bank Sta=5006.3,5010.3
Exp/Cntr=0.3,0.1

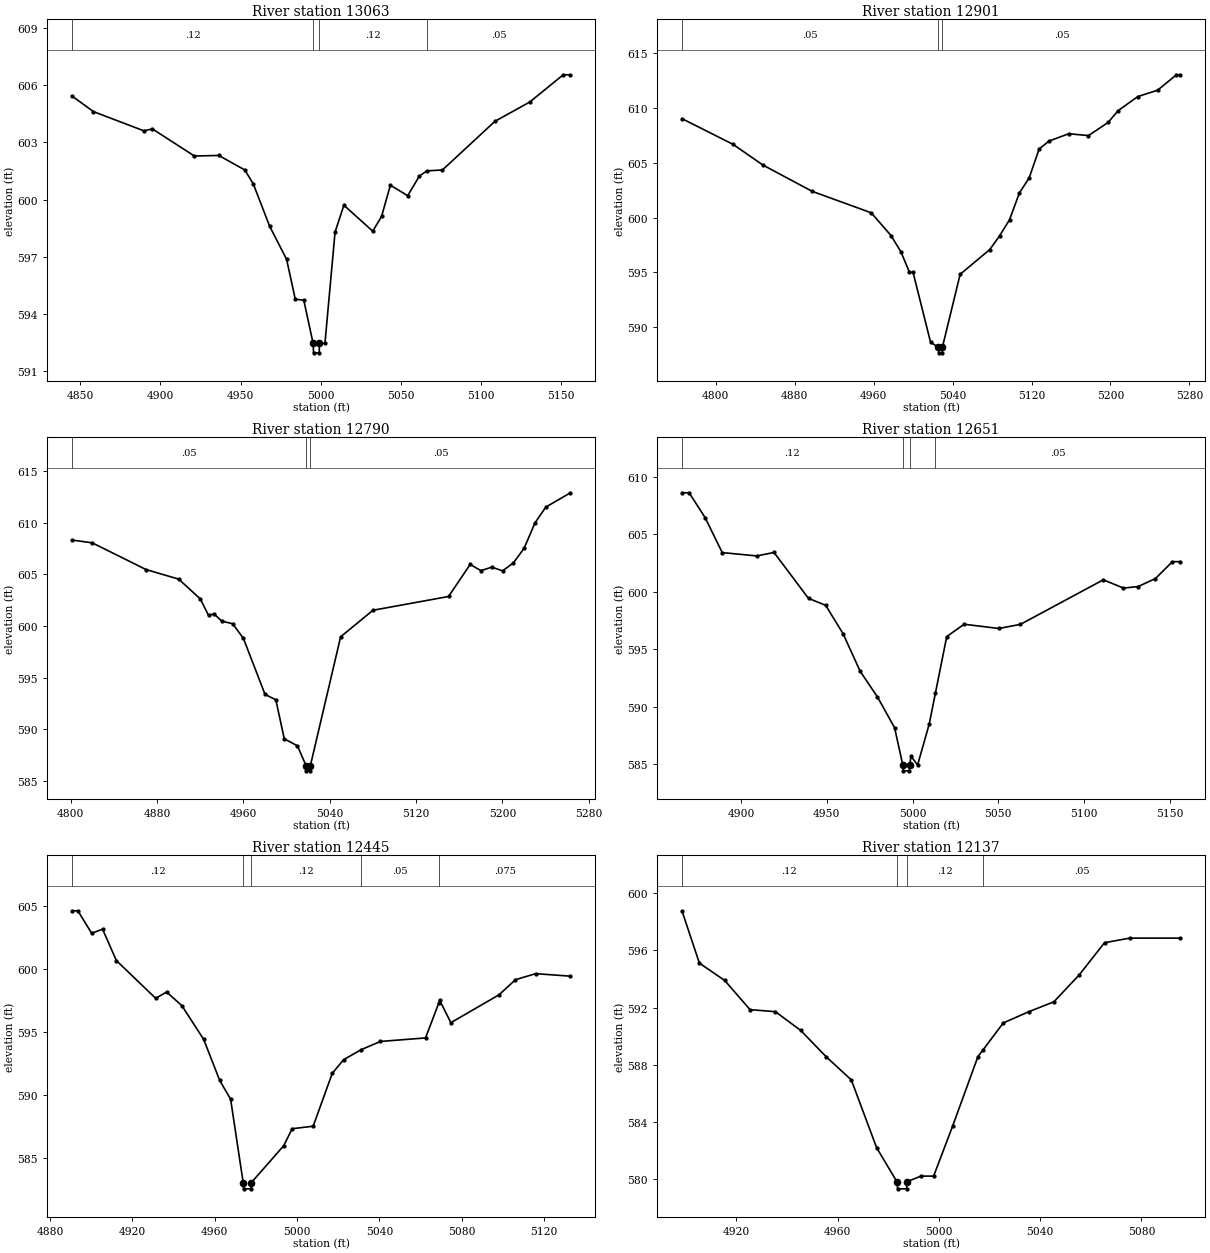
Type RM Length L Ch R = 1,13063,162,162,162
BEGIN DESCRIPTION:
McKamy Creek 35.0
END DESCRIPTION:
XS GIS Cut Line= 3
      2403305.85      7054840.43      2403158.78      7054890.01
      2403015.69      7054951.39
#Sta/Elev= 30
  4844.8  605.44  4858.2  604.62  4889.7  603.61  4895.0  603.71  4921.2  602.29
  4936.4  602.32  4952.6  601.56  4957.9  600.83  4968.1  598.61  4978.7  596.87
  4984.1  594.78  4989.4  594.73  4995.2  592.47  4995.5  591.97  4999.0  591.97
  4999.2  592.47  5002.6  592.47  5008.9  598.30  5014.4  599.71  5032.4  598.35
  5037.9  599.12  5043.4  600.76  5054.2  600.21  5061.5  601.24  5066.1  601.51
  5075.9  601.56  5108.6  604.11  5130.3  605.12  5151.2  606.55  5155.7  606.55
#Mann=4,-1,0
  4844.8    0.12       0  4995.2    0.07       0  4999.2    0.12       0
  5066.1    0.05       0
Bank Sta=4995.2,4999.2
Exp/Cntr=0.3,0.1

Type RM Length L Ch R = 1,12901,111,111,111
BEGIN DESCRIPTION:
Mapping XS 9a786fa8
END DESCRIPTION:
XS GIS Cut Line= 3
      2403410.81      7054754.33      2403176.71      7054754.07
      2402905.81      7054753.98
#Sta/Elev= 30
  4765.9  609.04  4817.7  606.69  4847.7  604.81  4897.7  602.40  4957.7  600.43
  4977.7  598.35  4987.7  596.87  4996.4  594.99  5000.0  594.99  5017.7  588.61
  5025.7  588.13  5026.0  587.63  5029.5  587.63  5029.7  588.13  5047.7  594.81
  5077.7  597.07  5087.7  598.33  5097.7  599.79  5107.7  602.24  5117.7  603.64
  5127.7  606.26  5137.7  606.99  5157.7  607.66  5177.7  607.49  5197.7  608.70
  5207.7  609.77  5227.7  611.06  5247.7  611.64  5266.8  613.05  5270.9  613.05
#Mann=3,-1,0
  4765.9    0.05       0  5025.7    0.05       0  5029.7    0.05       0
Bank Sta=5025.7,5029.7
Exp/Cntr=0.3,0.1

Type RM Length L Ch R = 1,12790,139,139,139
BEGIN DESCRIPTION:
Mapping XS 15e0bb43
END DESCRIPTION:
XS GIS Cut Line= 3
      2403377.84      7054646.69      2403178.22      7054644.08
      2402916.07      7054642.35
#Sta/Elev= 30
  4801.2  608.32  4820.0  608.05  4870.0  605.46  4900.1  604.54  4920.1  602.63
  4927.8  601.03  4932.8  601.18  4940.1  600.47  4950.1  600.23  4960.1  598.80
  4980.1  593.39  4990.1  592.87  4997.9  589.10  5010.1  588.42  5018.1  586.50
  5018.3  586.00  5021.8  586.00  5022.1  586.50  5050.1  598.96  5080.1  601.53
  5150.1  602.86  5170.1  605.96  5180.1  605.36  5190.1  605.70  5200.1  605.34
  5210.1  606.10  5220.1  607.53  5230.1  609.97  5240.1  611.50  5263.0  612.89
#Mann=3,-1,0
  4801.2    0.05       0  5018.1    0.05       0  5022.1    0.05       0
Bank Sta=5018.1,5022.1
Exp/Cntr=0.3,0.1

Type RM Length L Ch R = 1,12651,206,206,206
BEGIN DESCRIPTION:
McKamy Creek 34.0
END DESCRIPTION:
XS GIS Cut Line= 3
      2403312.41      7054518.04      2403178.56      7054504.82
      2403024.61      7054531.23
#Sta/Elev= 30
  4865.5  608.63  4869.7  608.63  4879.0  606.47  4889.0  603.42  4909.1  603.13
  4919.2  603.43  4939.3  599.43  4949.3  598.83  4959.4  596.37  4969.4  593.09
  4979.5  590.85  4989.5  588.16  4994.3  584.91  4994.6  584.41  4998.1  584.41
  4998.3  584.91  4999.1  585.69  5002.9  584.91  5009.7  588.49  5013.3  591.18
  5019.9  596.10  5030.0  597.18  5050.3  596.81  5062.9  597.17  5111.2  601.05
  5122.9  600.33  5131.5  600.46  5141.6  601.16  5151.5  602.63  5156.2  602.63
#Mann=4,-1,0
  4865.5    0.12       0  4994.3    0.07       0  4998.3    0.12       0
  5013.3    0.05       0
Bank Sta=4994.3,4998.3
Exp/Cntr=0.3,0.1

Type RM Length L Ch R = 1,12445,308,308,308
BEGIN DESCRIPTION:
McKamy Creek 33.0
END DESCRIPTION:
XS GIS Cut Line= 3
      2403299.44      7054290.60      2403196.12      7054326.55
      2403074.56      7054380.03
#Sta/Elev= 30
  4890.6  604.63  4893.5  604.63  4900.2  602.84  4905.5  603.17  4912.2  600.67
  4931.3  597.67  4936.6  598.17  4944.0  597.09  4954.6  594.41  4962.4  591.14
  4967.7  589.65  4973.8  583.02  4974.0  582.52  4977.5  582.52  4977.8  583.02
  4993.5  585.95  4997.6  587.30  5007.8  587.50  5017.1  591.71  5022.6  592.79
  5031.2  593.59  5040.5  594.24  5062.4  594.52  5068.8  597.28  5069.3  597.50
  5074.7  595.73  5098.1  597.95  5106.1  599.15  5115.9  599.63  5132.8  599.43
#Mann=5,-1,0
  4890.6    0.12       0  4973.8    0.07       0  4977.8    0.12       0
  5031.2    0.05       0  5068.8   0.075       0
Bank Sta=4973.8,4977.8
Exp/Cntr=0.3,0.1

Type RM Length L Ch R = 1,12137,301,301,301
BEGIN DESCRIPTION:
McKamy Creek 32.0
END DESCRIPTION:
XS GIS Cut Line= 3
      2403275.93      7054060.57      2403179.00      7054060.00
      2403079.03      7054060.00
#Sta/Elev= 25
  4898.5  598.77  4905.4  595.11  4915.4  593.90  4925.4  591.86  4935.4  591.72
  4945.4  590.41  4955.4  588.58  4965.4  586.95  4975.4  582.21  4983.4  579.84
  4983.7  579.34  4987.2  579.34  4987.4  579.84  4992.9  580.23  4997.9  580.23
  5005.4  583.72  5015.4  588.58  5017.5  589.07  5025.4  590.93  5035.4  591.71
  5045.4  592.41  5055.4  594.29  5065.4  596.54  5075.4  596.86  5095.4  596.86
#Mann=4,-1,0
  4898.5    0.12       0  4983.4    0.07       0  4987.4    0.12       0
  5017.5    0.05       0
Bank Sta=4983.4,4987.4
Exp/Cntr=0.3,0.1

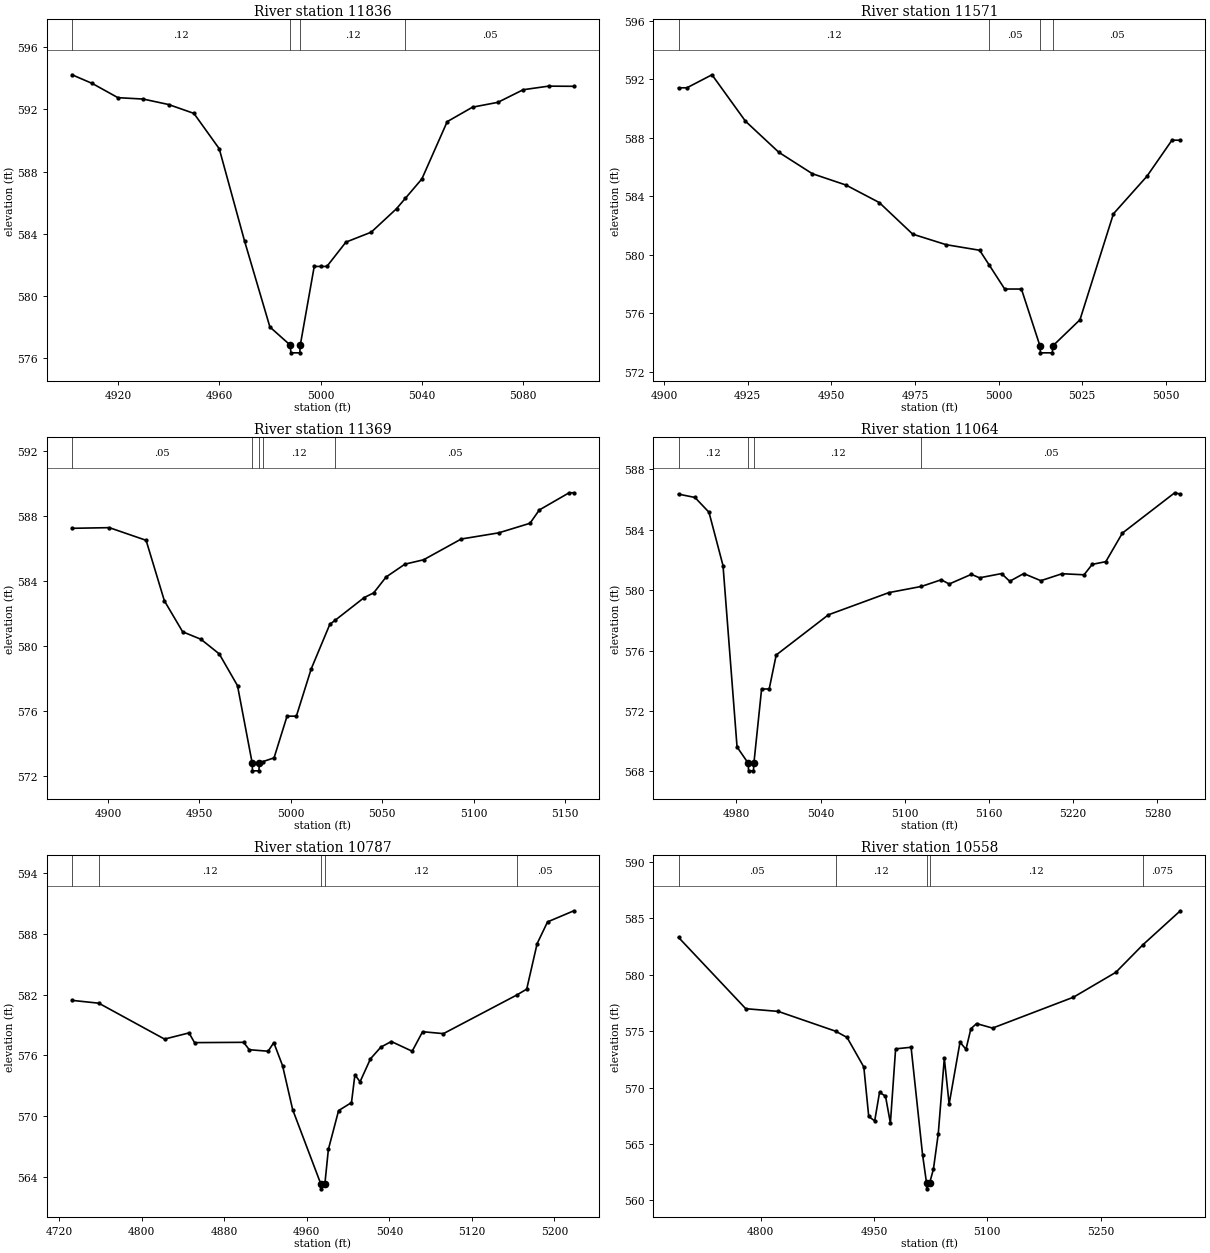
Type RM Length L Ch R = 1,11836,265,265,265
BEGIN DESCRIPTION:
McKamy Creek 31.0
END DESCRIPTION:
XS GIS Cut Line= 3
      2403277.04      7053764.05      2403179.00      7053760.00
      2403079.02      7053760.00
#Sta/Elev= 27
  4901.9  594.22  4909.9  593.66  4920.0  592.75  4930.0  592.66  4940.0  592.31
  4950.0  591.74  4960.0  589.47  4970.0  583.54  4980.0  578.02  4988.0  576.86
  4988.3  576.36  4991.8  576.36  4992.0  576.86  4997.5  581.91  5000.0  581.91
  5002.5  581.91  5010.0  583.47  5020.0  584.11  5030.0  585.62  5033.5  586.29
  5040.0  587.53  5050.0  591.21  5060.0  592.14  5070.0  592.45  5080.0  593.26
  5090.0  593.49  5100.0  593.48
#Mann=4,-1,0
  4901.9    0.12       0  4988.0    0.07       0  4992.0    0.12       0
  5033.5    0.05       0
Bank Sta=4988,4992
Exp/Cntr=0.3,0.1

Type RM Length L Ch R = 1,11571,202,202,202
BEGIN DESCRIPTION:
McKamy Creek 30.0
END DESCRIPTION:
XS GIS Cut Line= 3
      2403228.96      7053510.00      2403129.00      7053510.00
      2403078.96      7053510.00
#Sta/Elev= 23
  4904.3  591.42  4906.8  591.42  4914.3  592.31  4924.3  589.14  4934.3  587.01
  4944.3  585.55  4954.3  584.78  4964.3  583.58  4974.3  581.42  4984.3  580.70
  4994.3  580.32  4997.2  579.30  5001.8  577.67  5006.8  577.67  5012.3  573.81
  5012.5  573.31  5016.0  573.31  5016.3  573.81  5024.3  575.57  5034.3  582.81
  5044.3  585.37  5051.8  587.84  5054.3  587.84
#Mann=4,-1,0
  4904.3    0.12       0  4997.2    0.05       0  5012.3    0.05       0
  5016.3    0.05       0
Bank Sta=5012.3,5016.3
Exp/Cntr=0.3,0.1

Type RM Length L Ch R = 1,11369,305,305,305
BEGIN DESCRIPTION:
McKamy Creek 29.0
END DESCRIPTION:
XS GIS Cut Line= 3
      2403299.44      7053328.80      2403179.79      7053325.22
      2403028.95      7053360.01
#Sta/Elev= 30
  4880.3  587.24  4900.7  587.28  4920.8  586.50  4930.8  582.77  4940.8  580.86
  4950.8  580.40  4960.8  579.50  4970.8  577.54  4978.8  572.79  4979.0  572.29
  4982.5  572.29  4982.8  572.79  4984.7  572.86  4990.8  573.09  4997.9  575.66
  5003.0  575.66  5011.1  578.57  5021.3  581.32  5024.2  581.57  5040.1  582.97
  5045.3  583.26  5052.1  584.24  5062.4  585.03  5072.6  585.30  5093.2  586.58
  5113.7  586.96  5130.8  587.55  5135.9  588.37  5152.2  589.43  5154.8  589.43
#Mann=5,-1,0
  4880.3    0.05       0  4978.8    0.07       0  4982.8    0.05       0
  4984.7    0.12       0  5024.2    0.05       0
Bank Sta=4978.8,4982.8
Exp/Cntr=0.3,0.1

Type RM Length L Ch R = 1,11064,277,277,277
BEGIN DESCRIPTION:
McKamy Creek 28.0
END DESCRIPTION:
XS GIS Cut Line= 3
      2403290.68      7053061.44      2403229.00      7053060.00
      2402973.05      7053208.49
#Sta/Elev= 30
  4938.8  586.36  4950.5  586.14  4960.5  585.16  4970.5  581.63  4980.5  569.62
  4988.5  568.54  4988.7  568.04  4992.2  568.04  4992.5  568.54  4998.0  573.46
  5003.4  573.46  5008.4  575.71  5045.6  578.37  5088.7  579.84  5111.9  580.25
  5126.0  580.69  5131.7  580.41  5147.5  581.05  5153.3  580.82  5169.0  581.10
  5174.8  580.59  5184.8  581.10  5197.0  580.63  5212.1  581.09  5227.8  581.02
  5233.6  581.71  5243.3  581.89  5255.1  583.78  5292.4  586.45  5296.4  586.36
#Mann=4,-1,0
  4938.8    0.12       0  4988.5    0.07       0  4992.5    0.12       0
  5111.9    0.05       0
Bank Sta=4988.5,4992.5
Exp/Cntr=0.3,0.1

Type RM Length L Ch R = 1,10787,229,229,229
BEGIN DESCRIPTION:
McKamy Creek 27.0
END DESCRIPTION:
XS GIS Cut Line= 3
      2403327.15      7052969.41      2403080.49      7052865.91
      2402863.77      7052835.77
#Sta/Elev= 30
  4732.5  581.45  4758.4  581.17  4822.1  577.62  4845.8  578.23  4851.2  577.27
  4898.8  577.30  4904.2  576.57  4922.5  576.42  4928.0  577.27  4936.5  574.99
  4946.3  570.64  4973.5  563.31  4973.7  562.81  4977.5  563.31  4980.9  566.71
  4990.8  570.55  5003.3  571.34  5006.6  574.08  5011.6  573.40  5021.7  575.67
  5031.8  576.83  5041.9  577.38  5062.1  576.42  5072.2  578.35  5092.4  578.16
  5163.5  581.98  5173.1  582.56  5183.2  587.06  5193.3  589.21  5218.8  590.31
#Mann=5,-1,0
  4732.5    0.05       0  4758.4    0.12       0  4973.5    0.07       0
  4977.5    0.12       0  5163.5    0.05       0
Bank Sta=4973.5,4977.5
Exp/Cntr=0.3,0.1

Type RM Length L Ch R = 1,10558,342,342,342
BEGIN DESCRIPTION:
McKamy Creek 26.0
END DESCRIPTION:
XS GIS Cut Line= 3
      2403451.51      7052972.42      2403255.69      7052733.39
      2402979.01      7052510.01
#Sta/Elev= 30
  4691.0  583.32  4780.0  577.00  4823.0  576.76  4899.2  575.00  4914.2  574.45
  4936.4  571.83  4942.9  567.45  4950.8  567.05  4957.2  569.58  4965.1  569.25
  4971.6  566.86  4978.5  573.44  4999.0  573.58  5014.2  564.06  5019.5  561.53
  5019.7  561.03  5023.5  561.53  5028.6  562.78  5035.0  565.91  5043.0  572.61
  5049.4  568.54  5063.8  574.03  5071.7  573.40  5078.2  575.22  5085.7  575.68
  5106.9  575.28  5214.1  578.02  5270.1  580.22  5306.1  582.67  5355.6  585.68
#Mann=5,-1,0
  4691.0    0.05       0  4899.2    0.12       0  5019.5    0.07       0
  5023.5    0.12       0  5306.1   0.075       0
Bank Sta=5019.5,5023.5
Exp/Cntr=0.3,0.1

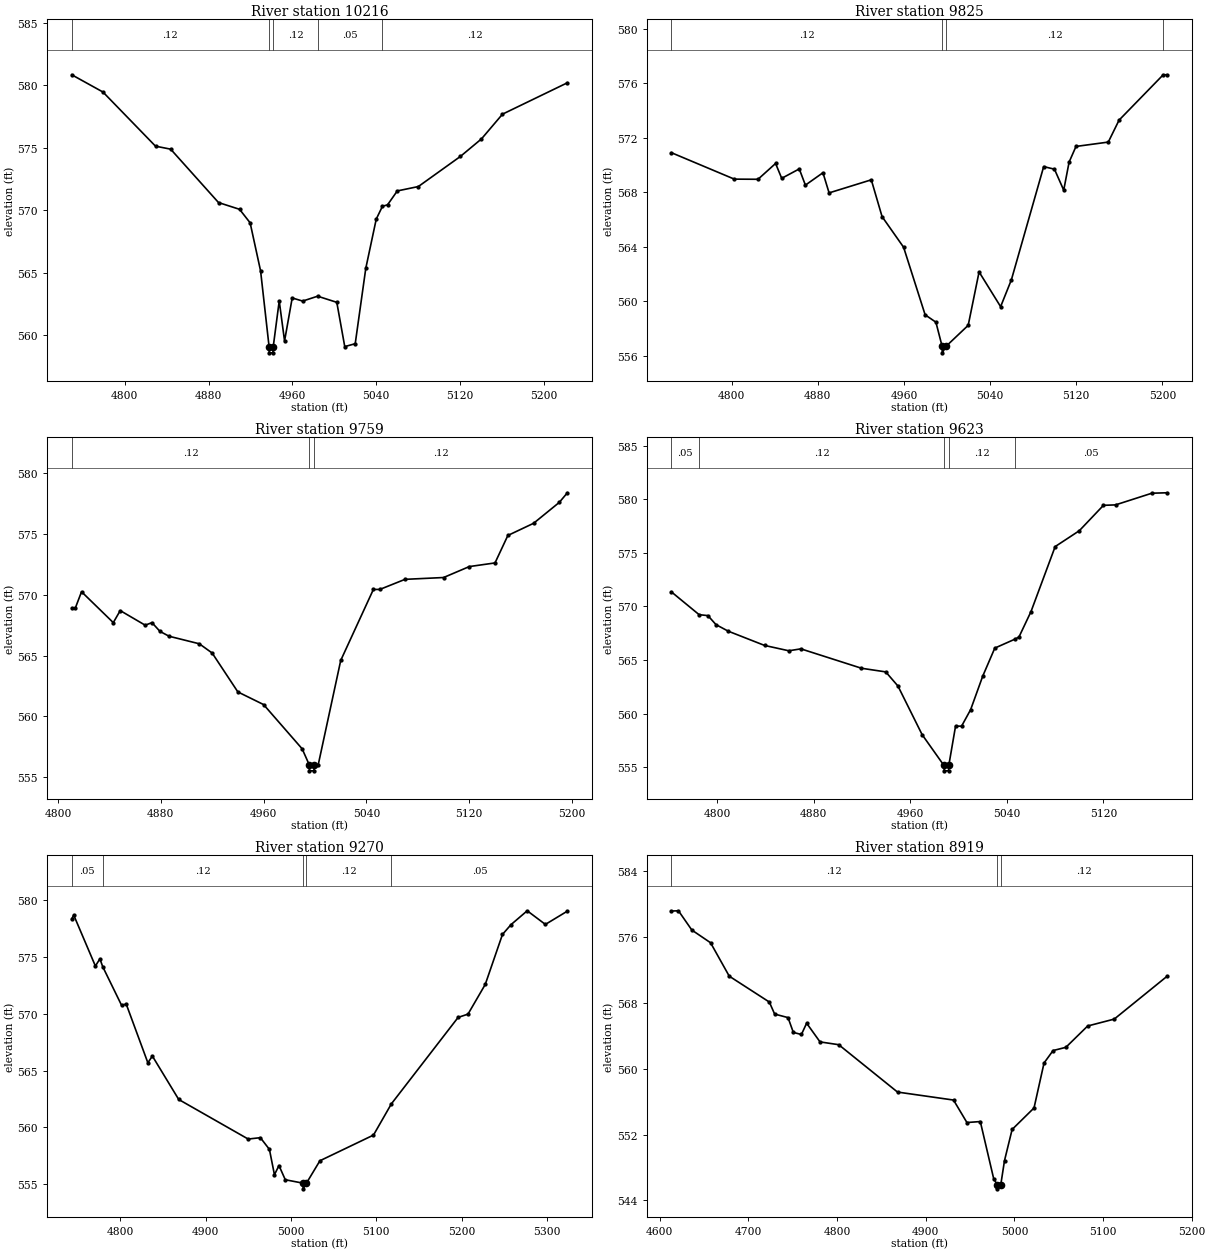
Type RM Length L Ch R = 1,10216,391,391,391
BEGIN DESCRIPTION:
McKamy Creek 25.0
END DESCRIPTION:
XS GIS Cut Line= 3
      2403528.63      7052463.78      2403279.03      7052440.35
      2403057.33      7052462.48
#Sta/Elev= 30
  4749.3  580.85  4779.1  579.47  4829.3  575.14  4843.8  574.90  4889.5  570.63
  4909.6  570.09  4919.7  569.01  4929.7  565.16  4937.8  559.11  4938.0  558.61
  4941.5  558.61  4941.8  559.11  4947.5  562.76  4952.6  559.56  4959.9  563.00
  4969.9  562.75  4984.2  563.14  5002.5  562.65  5010.1  559.11  5020.1  559.34
  5030.2  565.37  5040.2  569.31  5046.1  570.33  5051.0  570.45  5060.3  571.56
  5080.4  571.91  5120.6  574.32  5140.7  575.72  5160.8  577.70  5222.8  580.21
#Mann=5,-1,0
  4749.3    0.12       0  4937.8   0.033       0  4941.8    0.12       0
  4984.2    0.05       0  5046.1    0.12       0
Bank Sta=4937.8,4941.8
Exp/Cntr=0.3,0.1

Type RM Length L Ch R = 1,9825,66,66,66
BEGIN DESCRIPTION:
McKamy Creek 24.0
END DESCRIPTION:
XS GIS Cut Line= 4
      2403366.56      7052058.22      2403229.10      7052130.95
      2403128.74      7052128.31      2402924.43      7052122.27
#Sta/Elev= 30
  4744.1  570.90  4802.5  568.96  4824.5  568.95  4840.8  570.11  4846.5  569.02
  4862.8  569.71  4868.5  568.52  4884.8  569.43  4890.5  567.95  4929.7  568.91
  4939.7  566.21  4959.7  563.96  4979.7  559.00  4989.7  558.46  4995.4  556.71
  4995.6  556.21  4999.4  556.71  5019.7  558.23  5029.8  562.15  5049.8  559.60
  5059.8  561.57  5089.8  569.88  5099.8  569.69  5108.4  568.15  5113.4  570.21
  5119.8  571.36  5149.8  571.68  5159.8  573.29  5200.8  576.62  5204.4  576.62
#Mann=4,-1,0
  4744.1    0.12       0  4995.4    0.07       0  4999.4    0.12       0
  5200.8   0.075       0
Bank Sta=4995.4,4999.4
Exp/Cntr=0.3,0.1

Type RM Length L Ch R = 1,9759,136,136,136
BEGIN DESCRIPTION:
Mapping XS 7549cf17
END DESCRIPTION:
XS GIS Cut Line= 5
      2403313.08      7052033.04      2403240.73      7052060.63
      2403128.98      7052062.20      2403083.26      7052060.98
      2402932.71      7052058.57
#Sta/Elev= 30
  4810.8  568.89  4813.5  568.89  4818.4  570.25  4843.1  567.71  4848.5  568.70
  4867.9  567.50  4873.2  567.71  4879.4  566.99  4886.5  566.59  4910.0  565.97
  4920.0  565.21  4940.0  562.01  4960.0  560.97  4990.0  557.33  4995.5  556.02
  4995.7  555.52  4999.2  555.52  4999.5  556.02  5002.5  556.02  5020.0  564.60
  5045.4  570.44  5050.4  570.44  5070.0  571.27  5100.0  571.42  5120.0  572.32
  5140.0  572.62  5150.0  574.88  5170.0  575.88  5190.0  577.60  5196.3  578.39
#Mann=3,-1,0
  4810.8    0.12       0  4995.5    0.07       0  4999.5    0.12       0
Bank Sta=4995.5,4999.5
Exp/Cntr=0.3,0.1

Type RM Length L Ch R = 1,9623,353,353,353
BEGIN DESCRIPTION:
McKamy Creek 23.0
END DESCRIPTION:
XS GIS Cut Line= 3
      2403365.77      7051947.62      2403128.98      7051925.74
      2402956.37      7051931.47
#Sta/Elev= 30
  4762.2  571.35  4785.1  569.23  4792.4  569.14  4799.1  568.30  4809.2  567.69
  4839.3  566.36  4859.4  565.86  4869.4  566.04  4919.6  564.23  4939.7  563.89
  4949.8  562.57  4969.8  558.04  4987.9  555.16  4988.2  554.66  4991.7  554.66
  4991.9  555.16  4997.5  558.83  5002.5  558.83  5010.0  560.37  5020.0  563.49
  5030.0  566.11  5046.4  566.93  5050.0  567.14  5060.0  569.52  5080.0  575.58
  5100.0  577.06  5120.0  579.43  5130.0  579.47  5160.1  580.56  5172.7  580.60
#Mann=5,-1,0
  4762.2    0.05       0  4785.1    0.12       0  4987.9    0.07       0
  4991.9    0.12       0  5046.4    0.05       0
Bank Sta=4987.9,4991.9
Exp/Cntr=0.3,0.1

Type RM Length L Ch R = 1,9270,351,351,351
BEGIN DESCRIPTION:
McKamy Creek 22.0
END DESCRIPTION:
XS GIS Cut Line= 3
      2403467.07      7051695.46      2403229.00      7051610.00
      2402903.43      7051569.67
#Sta/Elev= 30
  4743.0  578.35  4745.3  578.68  4770.7  574.20  4776.0  574.83  4779.3  574.14
  4801.5  570.73  4806.8  570.86  4832.2  565.69  4837.5  566.28  4868.4  562.46
  4949.8  558.98  4964.1  559.10  4974.7  558.07  4980.6  555.84  4985.9  556.65
  4993.3  555.40  5014.1  555.10  5014.3  554.60  5018.1  555.10  5033.9  557.07
  5096.7  559.33  5117.7  562.08  5195.9  569.68  5207.5  569.97  5227.7  572.58
  5247.9  576.98  5257.9  577.84  5276.9  579.06  5298.2  577.86  5324.0  579.03
#Mann=5,-1,0
  4743.0    0.05       0  4779.3    0.12       0  5014.1    0.07       0
  5018.1    0.12       0  5117.7    0.05       0
Bank Sta=5014.1,5018.1
Exp/Cntr=0.3,0.1

Type RM Length L Ch R = 1,8919,349,349,349
BEGIN DESCRIPTION:
McKamy Creek 21.0
END DESCRIPTION:
XS GIS Cut Line= 3
      2403602.93      7051487.85      2403279.66      7051275.27
      2403118.99      7051213.33
#Sta/Elev= 30
  4613.1  579.14  4621.0  579.17  4636.1  576.83  4657.2  575.29  4678.3  571.23
  4723.5  568.09  4729.5  566.63  4744.6  566.20  4750.6  564.40  4759.7  564.15
  4765.6  565.52  4780.7  563.25  4801.8  562.91  4868.1  557.16  4931.3  556.19
  4946.4  553.46  4961.5  553.58  4976.6  546.64  4980.6  545.91  4980.8  545.41
  4984.6  545.91  4988.8  548.84  4997.4  552.62  5022.1  555.23  5033.4  560.69
  5043.6  562.20  5058.0  562.59  5082.6  565.18  5112.6  566.02  5172.2  571.22
#Mann=3,-1,0
  4613.1    0.12       0  4980.6    0.07       0  4984.6    0.12       0
Bank Sta=4980.6,4984.6
Exp/Cntr=0.3,0.1

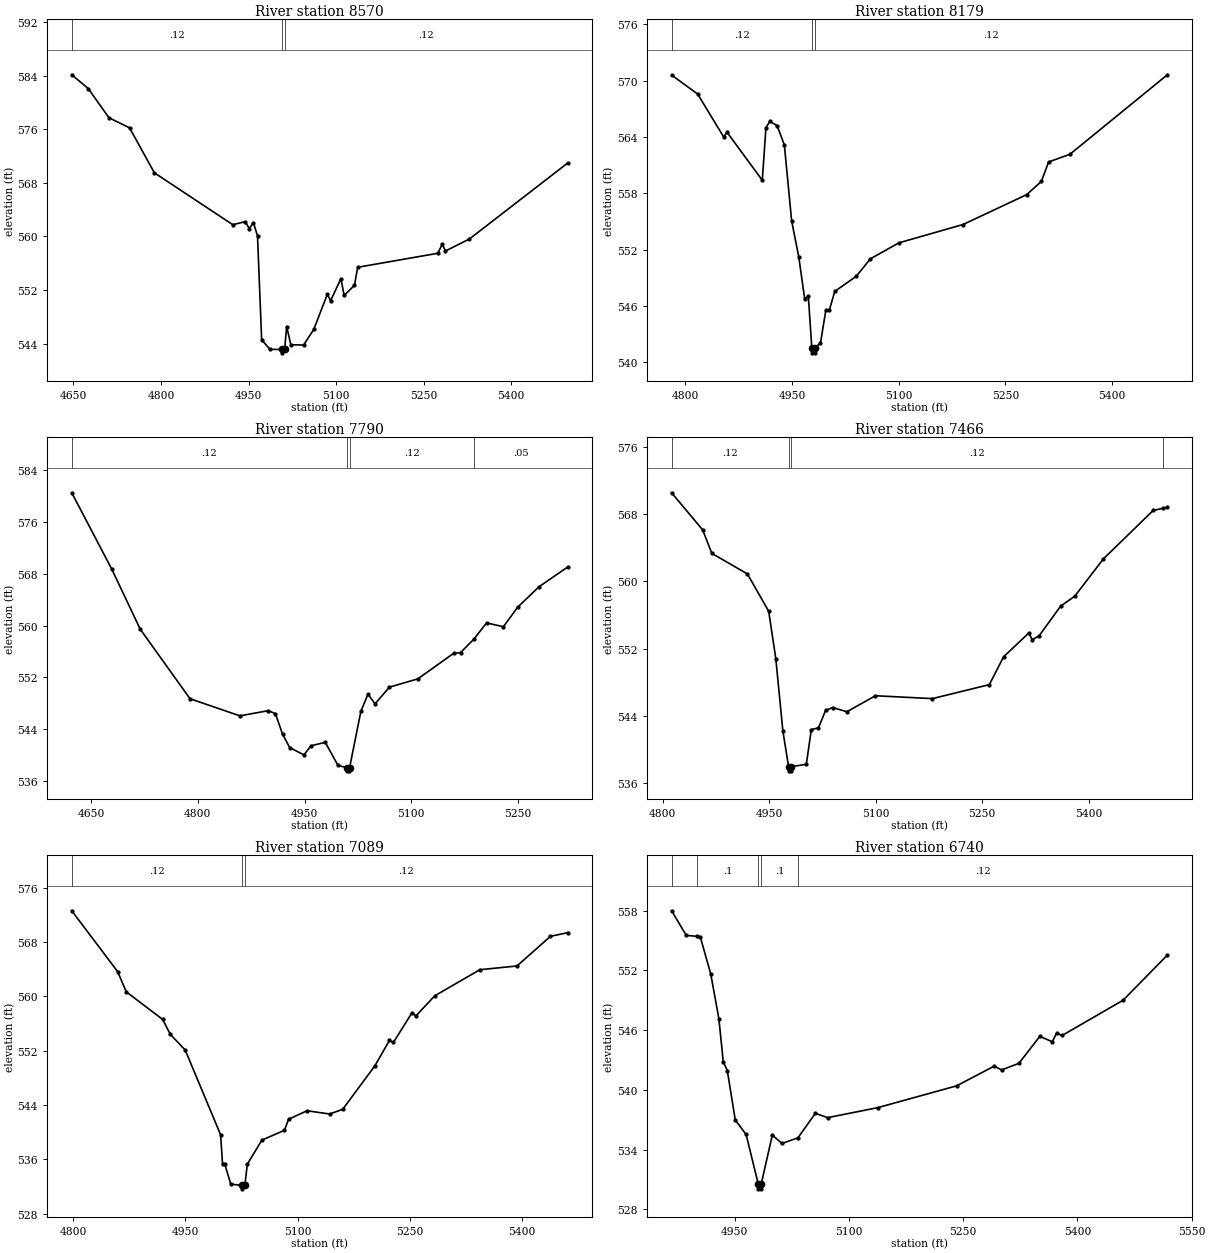
Type RM Length L Ch R = 1,8570,391,391,391
BEGIN DESCRIPTION:
McKamy Creek 20.0
END DESCRIPTION:
XS GIS Cut Line= 3
      2403729.03      7051310.03      2403479.59      7051060.54
      2403026.01      7050858.59
#Sta/Elev= 30
  4647.2  584.11  4675.5  582.05  4710.9  577.70  4746.2  576.20  4788.7  569.49
  4923.0  561.75  4944.2  562.20  4951.3  561.18  4958.4  562.06  4965.4  560.06
  4972.5  544.59  4986.7  543.16  5007.9  543.14  5008.1  542.64  5011.9  543.14
  5015.3  546.56  5022.5  543.85  5044.4  543.80  5061.8  546.14  5085.1  551.40
  5090.5  550.39  5108.3  553.71  5113.8  551.20  5131.5  552.71  5137.0  555.40
  5274.3  557.49  5281.9  558.84  5287.4  557.83  5328.4  559.62  5496.5  570.93
#Mann=3,-1,0
  4647.2    0.12       0  5007.9    0.07       0  5011.9    0.12       0
Bank Sta=5007.9,5011.9
Exp/Cntr=0.3,0.1

Type RM Length L Ch R = 1,8179,389,389,389
BEGIN DESCRIPTION:
McKamy Creek 19.0
END DESCRIPTION:
XS GIS Cut Line= 3
      2403745.17      7050747.66      2403529.00      7050710.00
      2403052.19      7050735.23
#Sta/Elev= 30
  4780.7  570.59  4817.4  568.56  4853.7  564.02  4858.8  564.48  4908.2  559.38
  4913.3  564.99  4918.9  565.66  4929.1  565.19  4939.2  563.14  4949.4  555.08
  4959.5  551.20  4967.8  546.74  4972.9  547.04  4977.8  541.50  4978.1  541.00
  4981.6  541.00  4981.8  541.50  4990.0  542.05  4997.6  545.59  5002.6  545.59
  5010.1  547.55  5040.2  549.15  5060.2  551.02  5100.3  552.72  5190.4  554.67
  5279.8  557.85  5300.5  559.26  5310.6  561.33  5340.6  562.15  5477.6  570.62
#Mann=3,-1,0
  4780.7    0.12       0  4977.8    0.07       0  4981.8    0.12       0
Bank Sta=4977.8,4981.8
Exp/Cntr=0.3,0.1

Type RM Length L Ch R = 1,7790,324,324,324
BEGIN DESCRIPTION:
McKamy Creek 18.0
END DESCRIPTION:
XS GIS Cut Line= 3
      2403755.18      7050393.31      2403378.08      7050394.57
      2403058.99      7050410.67
#Sta/Elev= 30
  4622.9  580.50  4679.1  568.71  4719.1  559.44  4789.1  548.70  4859.1  546.06
  4899.1  546.86  4909.1  546.39  4919.1  543.23  4929.1  541.16  4949.1  540.03
  4959.1  541.44  4979.1  541.97  4997.0  538.40  5009.3  538.07  5009.6  537.57
  5013.1  537.57  5013.3  538.07  5029.1  546.74  5039.1  549.40  5049.1  547.91
  5069.2  550.49  5109.2  551.77  5159.3  555.70  5169.3  555.84  5187.9  557.90
  5205.7  560.41  5229.4  559.82  5249.4  562.83  5279.4  565.99  5319.5  569.02
#Mann=4,-1,0
  4622.9    0.12       0  5009.3    0.07       0  5013.3    0.12       0
  5187.9    0.05       0
Bank Sta=5009.3,5013.3
Exp/Cntr=0.3,0.1

Type RM Length L Ch R = 1,7466,377,377,377
BEGIN DESCRIPTION:
McKamy Creek 17.0
END DESCRIPTION:
XS GIS Cut Line= 3
      2403765.70      7050176.65      2403578.12      7050169.87
      2403069.04      7050210.50
#Sta/Elev= 30
  4812.3  570.51  4856.0  566.11  4869.0  563.31  4919.1  560.87  4949.1  556.43
  4959.1  550.80  4969.1  542.18  4977.1  537.98  4977.4  537.48  4980.9  537.48
  4981.1  537.98  5002.1  538.26  5009.1  542.38  5019.2  542.59  5029.2  544.65
  5039.2  545.00  5059.3  544.50  5099.4  546.40  5179.7  546.06  5259.9  547.72
  5280.0  551.03  5315.5  553.85  5320.5  553.04  5330.2  553.54  5360.3  557.04
  5380.3  558.23  5420.5  562.65  5490.7  568.41  5504.8  568.67  5510.7  568.77
#Mann=4,-1,0
  4812.3    0.12       0  4977.1    0.07       0  4981.1    0.12       0
  5504.8    0.05       0
Bank Sta=4977.1,4981.1
Exp/Cntr=0.3,0.1

Type RM Length L Ch R = 1,7089,349,349,349
BEGIN DESCRIPTION:
McKamy Creek 16.0
END DESCRIPTION:
XS GIS Cut Line= 3
      2403680.27      7049809.76      2403478.85      7049825.06
      2403047.71      7049987.71
#Sta/Elev= 30
  4798.0  572.60  4859.4  563.63  4870.8  560.67  4919.6  556.59  4929.6  554.43
  4949.7  552.08  4997.0  539.61  4999.6  535.28  5002.6  535.28  5010.5  532.35
  5025.4  532.15  5025.6  531.65  5029.4  532.15  5032.7  535.28  5052.2  538.83
  5082.4  540.27  5087.8  541.90  5112.6  543.15  5142.8  542.67  5160.2  543.36
  5203.2  549.76  5222.7  553.51  5228.0  553.21  5252.9  557.59  5258.2  557.12
  5283.1  560.06  5343.5  563.92  5393.2  564.47  5438.0  568.84  5460.8  569.37
#Mann=3,-1,0
  4798.0    0.12       0  5025.4    0.07       0  5029.4    0.12       0
Bank Sta=5025.4,5029.4
Exp/Cntr=0.3,0.1

Type RM Length L Ch R = 1,6740,415,415,415
BEGIN DESCRIPTION:
McKamy Creek 15.0
END DESCRIPTION:
XS GIS Cut Line= 3
      2403506.97      7049460.51      2403383.16      7049508.25
      2402927.75      7049755.30
#Sta/Elev= 30
  4867.3  557.99  4886.6  555.52  4901.1  555.42  4905.1  555.33  4918.7  551.64
  4929.4  547.13  4935.1  542.83  4940.4  541.95  4950.9  536.98  4965.1  535.53
  4981.0  530.57  4981.3  530.07  4984.8  530.07  4985.0  530.57  4999.5  535.46
  5012.3  534.63  5033.1  535.19  5056.0  537.65  5072.2  537.22  5137.8  538.22
  5241.4  540.41  5290.8  542.39  5300.5  542.01  5323.2  542.67  5350.7  545.38
  5366.9  544.84  5372.6  545.68  5380.2  545.48  5460.0  549.01  5518.1  553.54
#Mann=5,-1,0
  4867.3    0.12       0  4901.1     0.1       0  4981.0    0.07       0
  4985.0     0.1       0  5033.1    0.12       0
Bank Sta=4981,4985
Exp/Cntr=0.3,0.1