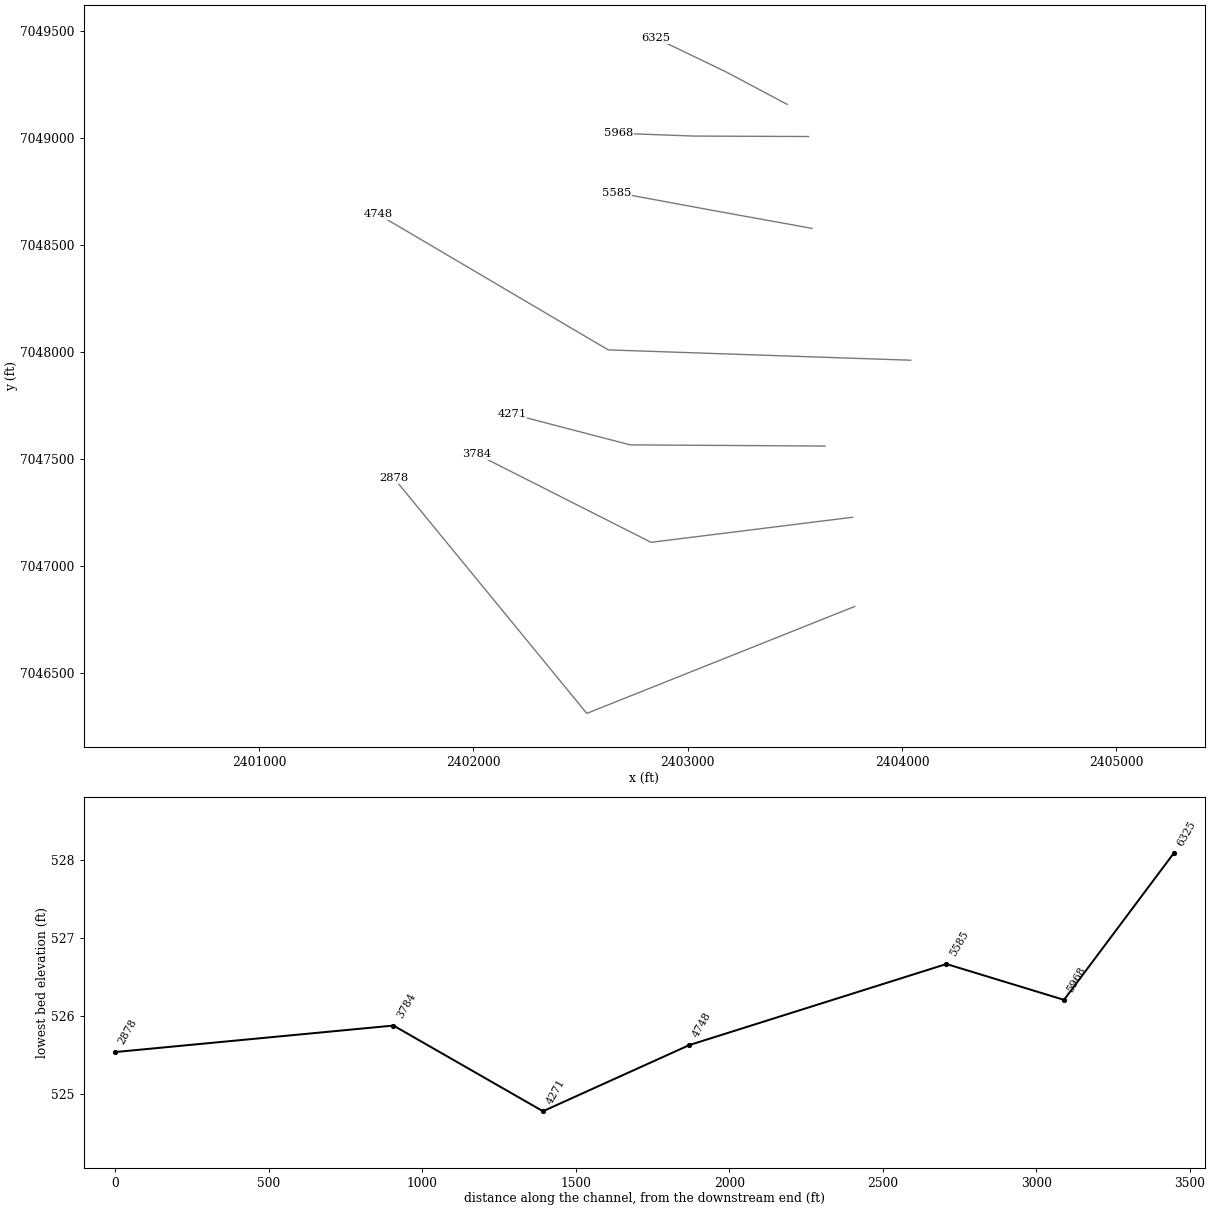
HEC-RAS study McKamy Creek.prj: McKamy Creek Base Level Engineering

--- McKamy Creek.g01 (geometry) --- (continued)

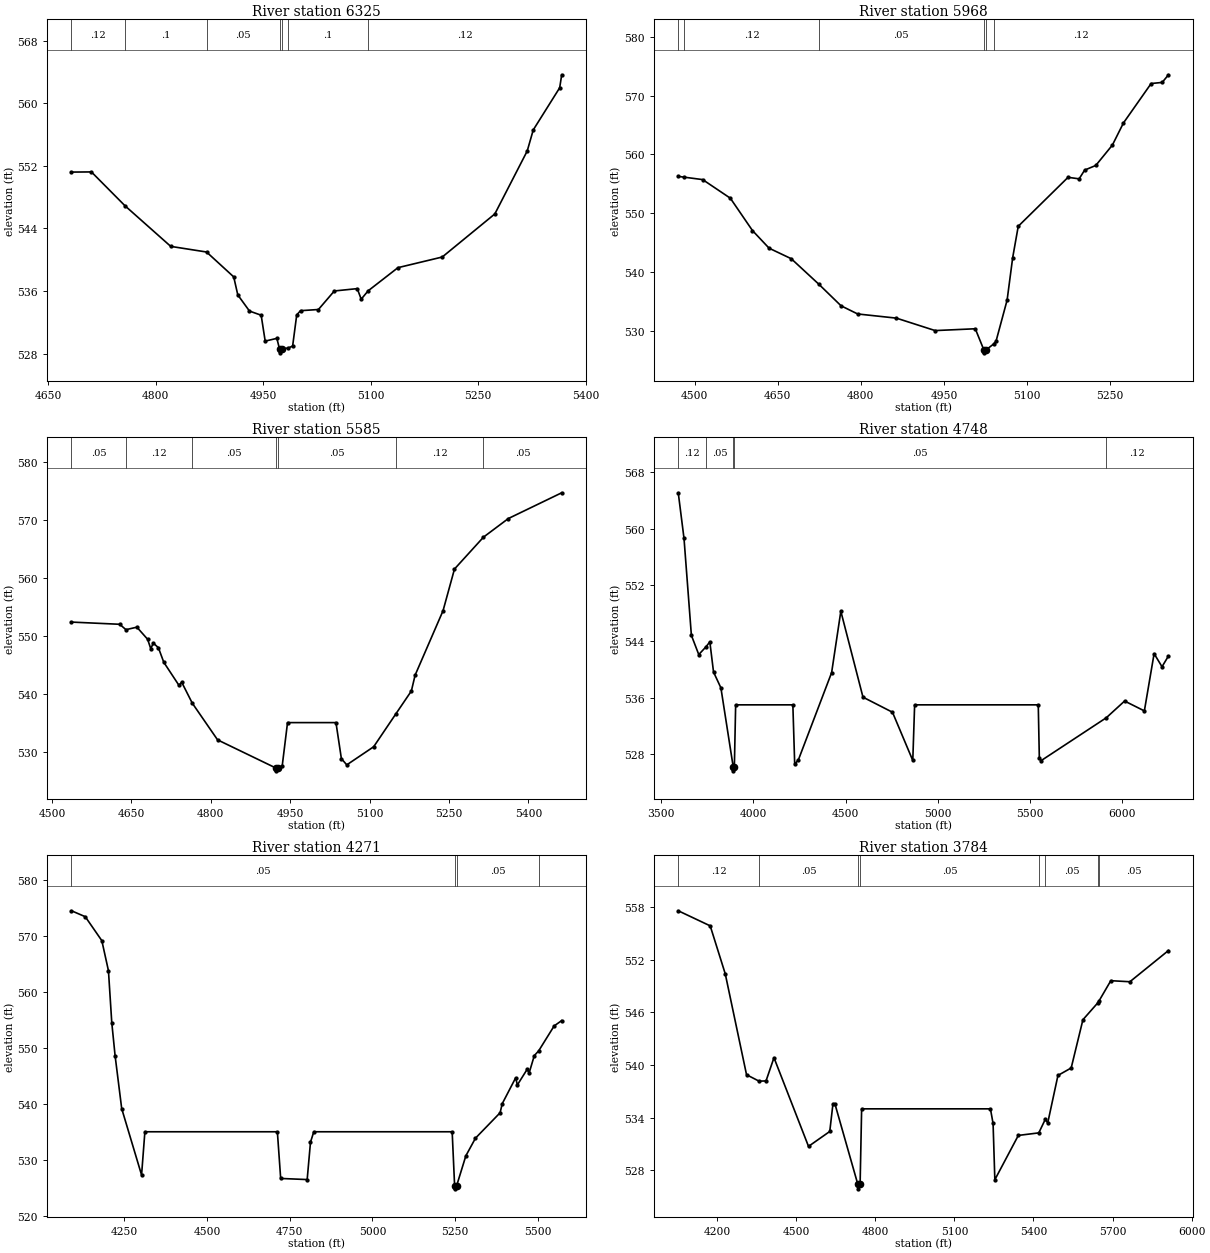
Type RM Length L Ch R = 1,6325,357,357,357
BEGIN DESCRIPTION:
McKamy Creek 14.0
END DESCRIPTION:
XS GIS Cut Line= 3
      2403463.57      7049158.43      2403179.00      7049310.00
      2402853.21      7049467.09
#Sta/Elev= 30
  4682.6  551.20  4710.4  551.22  4757.4  546.88  4821.1  541.70  4871.1  540.98
  4909.0  537.80  4914.7  535.49  4931.0  533.43  4947.3  532.90  4952.9  529.59
  4969.2  529.94  4972.9  528.59  4973.1  528.09  4976.9  528.59  4984.9  528.71
  4991.2  528.95  4996.9  532.93  5002.2  533.48  5027.2  533.63  5049.4  536.00
  5081.4  536.30  5086.9  534.95  5096.6  536.02  5138.2  538.98  5200.0  540.34
  5273.4  545.85  5318.6  553.90  5327.0  556.59  5363.9  561.98  5366.7  563.64
#Mann=7,-1,0
  4682.6    0.12       0  4757.4     0.1       0  4871.1    0.05       0
  4972.9    0.07       0  4976.9    0.05       0  4984.9     0.1       0
  5096.6    0.12       0
Bank Sta=4972.9,4976.9
Exp/Cntr=0.3,0.1

Type RM Length L Ch R = 1,5968,383,383,383
BEGIN DESCRIPTION:
McKamy Creek 13.0
END DESCRIPTION:
XS GIS Cut Line= 3
      2403563.10      7049007.90      2403029.00      7049010.00
      2402677.75      7049023.08
#Sta/Elev= 30
  4470.1  556.26  4481.1  556.12  4514.2  555.71  4564.2  552.54  4604.2  547.03
  4634.2  544.03  4674.2  542.24  4723.9  537.91  4764.2  534.22  4794.2  532.83
  4864.2  532.12  4934.2  530.00  5006.7  530.31  5022.2  526.71  5022.5  526.21
  5026.2  526.71  5039.9  527.72  5044.2  528.19  5064.2  535.19  5074.3  542.44
  5084.3  547.76  5174.3  556.10  5194.3  555.84  5204.3  557.33  5224.4  558.12
  5254.4  561.59  5274.4  565.36  5324.4  572.07  5344.4  572.26  5355.7  573.56
#Mann=6,-1,0
  4470.1    0.05       0  4481.1    0.12       0  4723.9    0.05       0
  5022.2   0.033       0  5026.2    0.05       0  5039.9    0.12       0
Bank Sta=5022.2,5026.2
Exp/Cntr=0.3,0.1

Type RM Length L Ch R = 1,5585,837,837,837
BEGIN DESCRIPTION:
McKamy Creek 12.0
END DESCRIPTION:
XS GIS Cut Line= 3
      2403580.49      7048578.21      2403129.00      7048660.00
      2402669.87      7048745.15
#Sta/Elev= 30
  4537.0  552.36  4628.1  551.98  4639.8  551.05  4660.5  551.48  4680.8  549.39
  4686.6  547.79  4691.7  548.71  4701.1  547.94  4711.3  545.42  4740.0  541.43
  4745.1  541.98  4765.1  538.36  4812.9  532.02  4922.7  527.17  4923.0  526.67
  4926.7  527.17  4934.9  527.47  4945.0  535.00  5036.5  535.00  5046.7  528.78
  5056.9  527.70  5107.7  530.83  5149.6  536.51  5178.9  540.46  5185.9  543.18
  5238.7  554.32  5260.3  561.52  5315.1  567.03  5362.0  570.24  5462.8  574.69
#Mann=7,-1,0
  4537.0    0.05       0  4639.8    0.12       0  4765.1    0.05       0
  4922.7   0.033       0  4926.7    0.05       0  5149.6    0.12       0
  5315.1    0.05       0
Bank Sta=4922.7,4926.7
Exp/Cntr=0.3,0.1

Type RM Length L Ch R = 1,4748,477,477,477
BEGIN DESCRIPTION:
McKamy Creek 10.0
END DESCRIPTION:
XS GIS Cut Line= 3
      2404040.17      7047961.64      2402629.00      7048010.00
      2401555.74      7048643.95
#Sta/Elev= 30
  3592.2  565.11  3623.4  558.63  3663.4  544.87  3703.4  542.14  3741.9  543.22
  3763.5  543.94  3783.5  539.66  3823.5  537.41  3890.6  526.13  3891.6  525.63
  3896.4  526.13  3903.5  535.00  4213.7  535.00  4223.7  526.57  4243.7  527.19
  4423.9  539.57  4473.9  548.29  4594.0  536.09  4754.0  533.95  4864.1  527.10
  4874.1  535.00  5544.6  535.00  5550.4  527.40  5560.2  527.08  5913.7  533.17
  6012.8  535.54  6120.0  534.14  6172.8  542.27  6215.7  540.41  6250.7  541.94
#Mann=5,-1,0
  3592.2    0.12       0  3741.9    0.05       0  3890.6   0.033       0
  3896.4    0.05       0  5913.7    0.12       0
Bank Sta=3890.6,3896.4
Exp/Cntr=0.3,0.1

Type RM Length L Ch R = 1,4271,487,487,487
BEGIN DESCRIPTION:
McKamy Creek 9.0
END DESCRIPTION:
XS GIS Cut Line= 3
      2403640.57      7047560.34      2402731.79      7047565.70
      2402179.01      7047710.00
#Sta/Elev= 30
  4091.2  574.57  4132.8  573.51  4182.8  569.22  4202.8  563.84  4212.8  554.56
  4222.8  548.65  4242.8  539.15  4302.8  527.26  4312.8  535.00  4712.8  535.00
  4722.8  526.64  4802.8  526.44  4812.8  533.13  4822.8  535.00  5240.6  535.00
  5248.0  525.28  5249.0  524.78  5253.8  525.28  5281.9  530.69  5310.9  533.85
  5385.3  538.40  5391.8  540.03  5432.3  544.66  5437.4  543.38  5467.6  546.24
  5472.7  545.47  5488.6  548.64  5501.7  549.48  5548.5  553.95  5571.3  554.91
#Mann=4,-1,0
  4091.2    0.05       0  5248.0   0.033       0  5253.8    0.05       0
  5501.7    0.12       0
Bank Sta=5248,5253.8
Exp/Cntr=0.3,0.1

Type RM Length L Ch R = 1,3784,906,906,906
BEGIN DESCRIPTION:
McKamy Creek 8.0
END DESCRIPTION:
XS GIS Cut Line= 3
      2403769.30      7047227.26      2402829.00      7047110.00
      2402015.53      7047522.15
#Sta/Elev= 30
  4052.5  557.58  4173.7  555.86  4230.8  550.39  4311.5  538.89  4358.7  538.16
  4385.4  538.18  4415.6  540.83  4546.6  530.72  4627.2  532.42  4639.4  535.59
  4647.4  535.50  4733.8  526.38  4735.1  525.88  4742.3  526.38  4748.1  535.00
  5236.7  535.00  5246.7  533.33  5253.4  526.92  5342.5  531.97  5420.1  532.26
  5445.0  533.82  5453.9  533.38  5492.8  538.81  5543.0  539.66  5587.5  545.16
  5645.0  547.12  5648.7  547.31  5693.3  549.61  5765.7  549.49  5912.0  553.05
#Mann=8,-1,0
  4052.5    0.12       0  4358.7    0.05       0  4733.8   0.033       0
  4742.3    0.05       0  5420.1   0.075       0  5445.0    0.05       0
  5645.0   0.075       0  5648.7    0.05       0
Bank Sta=4733.8,4742.3
Exp/Cntr=0.3,0.1

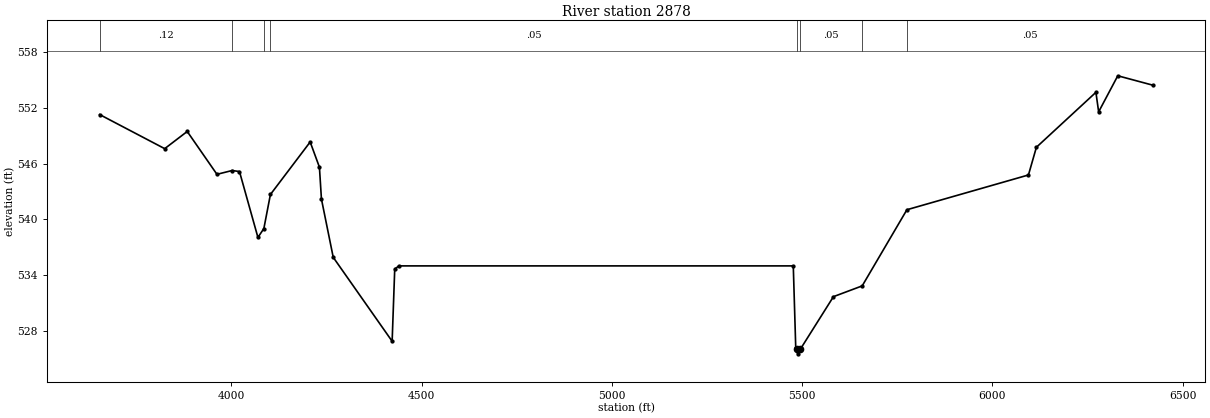
Type RM Length L Ch R = 1,2878,0,0,0
BEGIN DESCRIPTION:
McKamy Creek 6.0
END DESCRIPTION:
XS GIS Cut Line= 3
      2403778.99      7046810.00      2402529.00      7046310.00
      2401628.97      7047410.04
#Sta/Elev= 30
  3653.8  551.28  3824.8  547.61  3884.0  549.46  3962.1  544.85  4002.1  545.26
  4021.3  545.15  4069.8  538.06  4085.4  539.02  4102.6  542.68  4207.1  548.33
  4231.4  545.62  4236.7  542.19  4267.7  535.92  4422.5  526.89  4429.3  534.65
  4440.0  535.00  5476.7  535.00  5483.2  526.14  5486.8  526.04  5488.1  525.54
  5495.3  526.04  5582.2  531.69  5657.8  532.85  5775.3  541.04  6094.7  544.78
  6115.6  547.76  6272.0  553.67  6279.2  551.57  6329.5  555.45  6421.4  554.44
#Mann=8,-1,0
  3653.8    0.12       0  4002.1    0.05       0  4085.4    0.12       0
  4102.6    0.05       0  5486.8   0.033       0  5495.3    0.05       0
  5657.8     0.1       0  5775.3    0.05       0
Bank Sta=5486.8,5495.3
Exp/Cntr=0.3,0.1

Chan Stop Cuts=-1