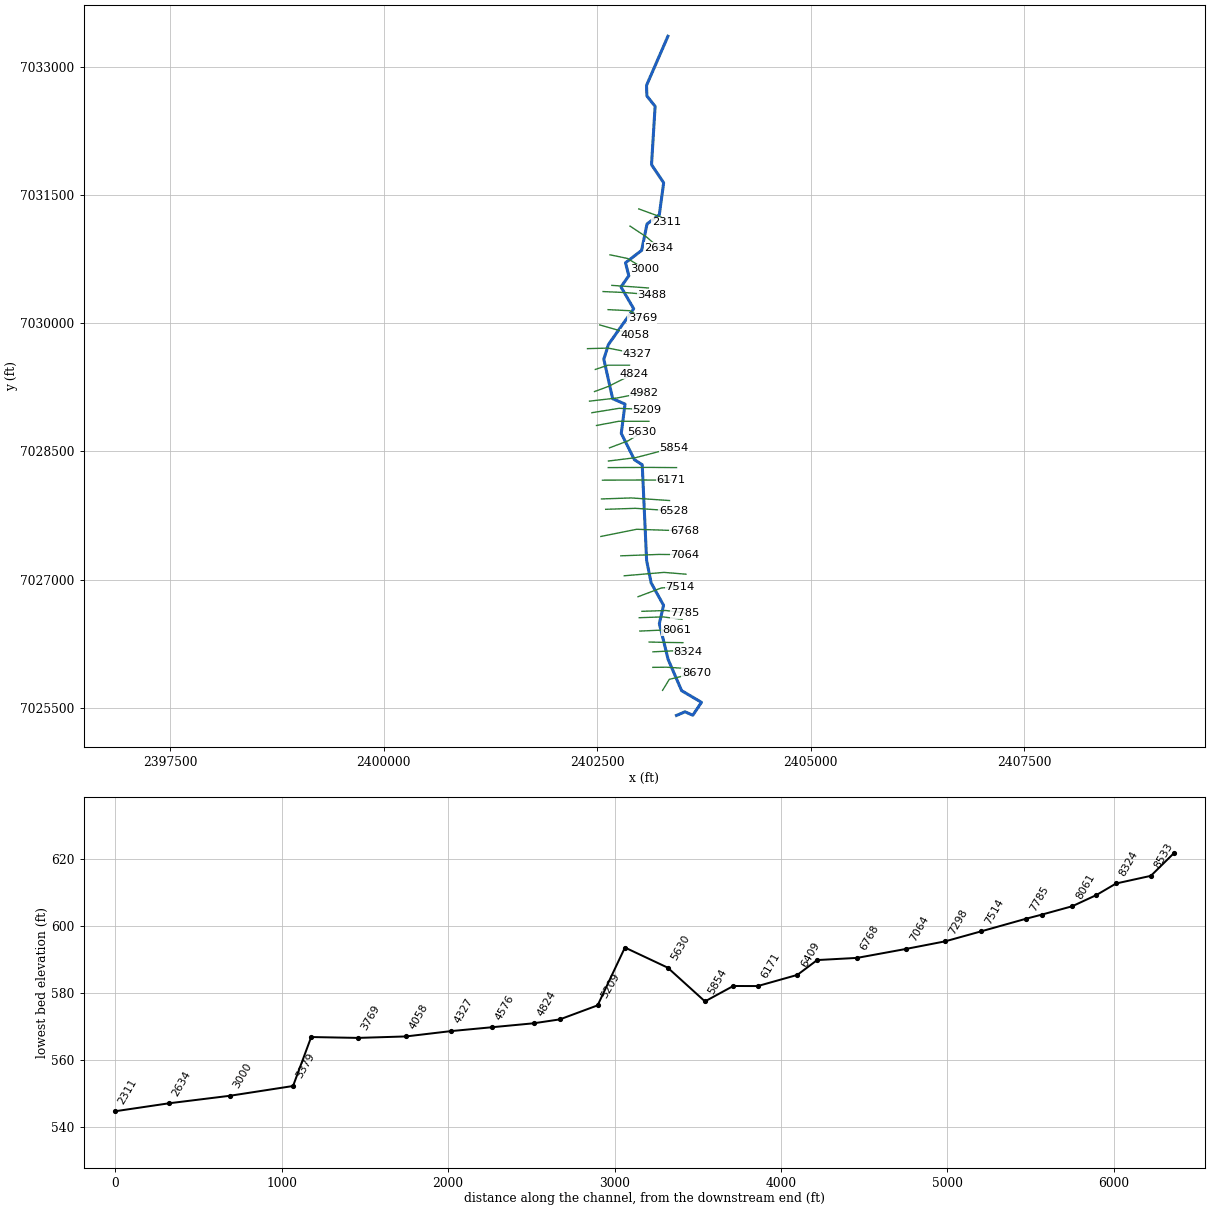
--- Moorehead Branch.prj (project) ---

Proj Title=Moorehead Branch Base Level Engineering
Current Plan=p01
Default Exp/Contr=0.3,0.1
English Units
Geom File=g01
Flow File=f01
Plan File=p01
Y Axis Title=Elevation
X Axis Title(PF)=Main Channel Distance
X Axis Title(XS)=Station
BEGIN DESCRIPTION:
Moorehead Branch
END DESCRIPTION:
DSS Export Rating Curves= 0
DSS Export Rating Curve Sorted= 0
DSS Export Volume Flow Curves= 0
DXF OffsetX= 0
DXF OffsetY= 0
DXF ScaleX= 1
DXF ScaleY= 10

--- Moorehead Branch.p01 (plan) ---

Plan Title=Multiple Run
Program Version=4.10
Short Identifier=Multiple
Geom File=g01
Flow File=f01
Subcritical Flow
K Sum by GR= 0
Std Step Tol= 0.01
Critical Tol= 0.01
Num of Std Step Trials= 20
Max Error Tol= 0.3
Flow Tol Ratio= 0.001
Split Flow NTrial= 30
Split Flow Tol= 0.02
Split Flow Ratio= 0.02
Log Output Level= 0
Friction Slope Method= 1
Unsteady Friction Slope Method= 2
Unsteady Bridges Friction Slope Method= 1
Parabolic Critical Depth
Global Vel Dist= 1 , 1 , 1
Global Log Level= 0
CheckData=True
Encroach Param=-1 ,0,0, 0
BEGIN DESCRIPTION:
Multiple Run
END DESCRIPTION:
Computation Interval=1HOUR
Output Interval=1HOUR
Run HTab= 0
Run UNet= 0
Run PostProcess= 0
Run WQNet= 0
UNET Theta= 1
UNET Theta Warmup= 1
UNET ZTol= 0.02
UNET ZSATol= 0.05
UNET MxIter= 20
UNET MaxInSteps= 0
UNET DtIC= 0
UNET DtMin= 0
UNET MaxCRTS= 20
UNET WFStab= 2
UNET SFStab= 1
UNET WFX= 1
UNET SFX= 1
UNET DSS MLevel= 4
UNET DZMax Abort= 100
UNET Convert EG Bridges= 0
UNET Use Existing IB Tables=-1
UNET Froude Reduction=False
UNET Froude Limit= 1
UNET Froude Power= 10
UNET Time Slicing=0,0, 5
UNET Junction Losses=0
Instantaneous Interval=1HOUR
Write IC File= 0
Write IC File at Sim End=0
Echo Input=False
Echo Parameters=False
Echo Output=False
Write Detailed= 0
WQ AD Non Conservative
WQ ULTIMATE=-1
WQ Max Comp Step=1HOUR
WQ Output Interval=15MIN
WQ Output Selected Increments= 0
WQ Output face flow=0
WQ Output face velocity=0
WQ Output face area=0
WQ Output face dispersion=0
WQ Output cell volume=0
WQ Output cell surface area=0
WQ Output cell continuity=0
WQ Output cumulative cell continuity=0
WQ Output face conc=0
WQ Output face dconc_dx=0
WQ Output face courant=0
WQ Output face peclet=0
WQ Output face adv mass=0
WQ Output face disp mass=0
WQ Output cell mass=0
WQ Output cell source sink temp=0
WQ Output cell source sink nsm=0
WQ Output MaxMinRange=-1
WQ Daily Max Min Mean=-1
WQ Daily Range=0
WQ Daily Time=0
WQ Create Restart=0
WQ Fixed Restart=0
WQ System Summary=0
WQ Use Fixed Temperature=0
Sorting and Armoring Iterations= 10
XS Update Threshold= 0.02
Hydraulics Update Threshold= 0.02
Energy Slope Method= 1
Volume Change Method= 0
XS Weighting Method= 0
Number of US Weighted Cross Sections= 1
Number of DS Weighted Cross Sections= 1
Upstream XS Weight=0.25
Main XS Weight=0.5
Downstream XS Weight=0.25
Number of DS XS's Weighted with US Boundary= 1
Upstream Boundary Weight= 1
Weight of XSs Associated with US Boundary= 0
Number of US XS's Weighted with DS Boundary= 1
Downstream Boundary Weight= 0.5
Weight of XSs Associated with DS Boundary= 0.5
Sediment Output Level= 4
Mass or Volume Output= 0
Output Increment Type= 1
Profile and TS Output Increment= 10
XS Output Flag= 0
XS Output Increment= 10
Disregard all LS=0
Disregard all Conn=0
Disregard all Breaches=0
Disregard all Pumps=0

--- Moorehead Branch.f01 (steady flow) ---

Flow Title=Multiple
Number of Profiles=7
Profile Names=10-year,25-year,50-year,1pct_min,100-year,1pct_plu,500-year
River Rch & RM= Moorehead Branch,Reach-1,8670
     519     701     849     510    1018    2031    1463
River Rch & RM= Moorehead Branch,Reach-1,3488
     655     898    1099     667    1330    2654    1947
Boundary for River Rch & Prof#=Moorehead Branch,Reach-1,1
Up Type=0
Dn Type=3
Dn Slope=0.005
Boundary for River Rch & Prof#=Moorehead Branch,Reach-1,2
Up Type=0
Dn Type=3
Dn Slope=0.005
Boundary for River Rch & Prof#=Moorehead Branch,Reach-1,3
Up Type=0
Dn Type=3
Dn Slope=0.005
Boundary for River Rch & Prof#=Moorehead Branch,Reach-1,4
Up Type=0
Dn Type=3
Dn Slope=0.005
Boundary for River Rch & Prof#=Moorehead Branch,Reach-1,5
Up Type=0
Dn Type=3
Dn Slope=0.005
Boundary for River Rch & Prof#=Moorehead Branch,Reach-1,6
Up Type=0
Dn Type=3
Dn Slope=0.005
Boundary for River Rch & Prof#=Moorehead Branch,Reach-1,7
Up Type=0
Dn Type=3
Dn Slope=0.005

--- Moorehead Branch.g01 (geometry) ---

Geom Title=Existing Conditions
Program Version=4.10

River Reach=Moorehead Branch,Reach-1
Reach XY= 30
        2403429.        7025410.        2403529.      7025452.64
       2403620.5      7025412.67       2403721.4      7025563.37
      2403489.52      7025700.17      2403331.27      7026065.94
      2403228.68      7026484.96       2403277.9      7026699.45
      2403132.55      7026961.47      2403079.52      7027225.22
      2403028.32      7028344.16      2402936.79      7028403.57
      2402782.74      7028711.56      2402827.04      7029054.35
      2402682.03      7029118.01      2402578.71      7029580.39
      2402632.41      7029751.55      2402928.24       7030170.7
      2402779.47      7030426.16      2402871.19      7030556.59
      2402832.46      7030708.51      2403021.26      7030853.55
      2403084.36       7031162.7      2403228.01      7031270.28
      2403279.04      7031644.66      2403137.04      7031856.68
      2403179.04      7032540.02      2403082.54      7032661.47
      2403078.68      7032785.11        2403329.        7033360.

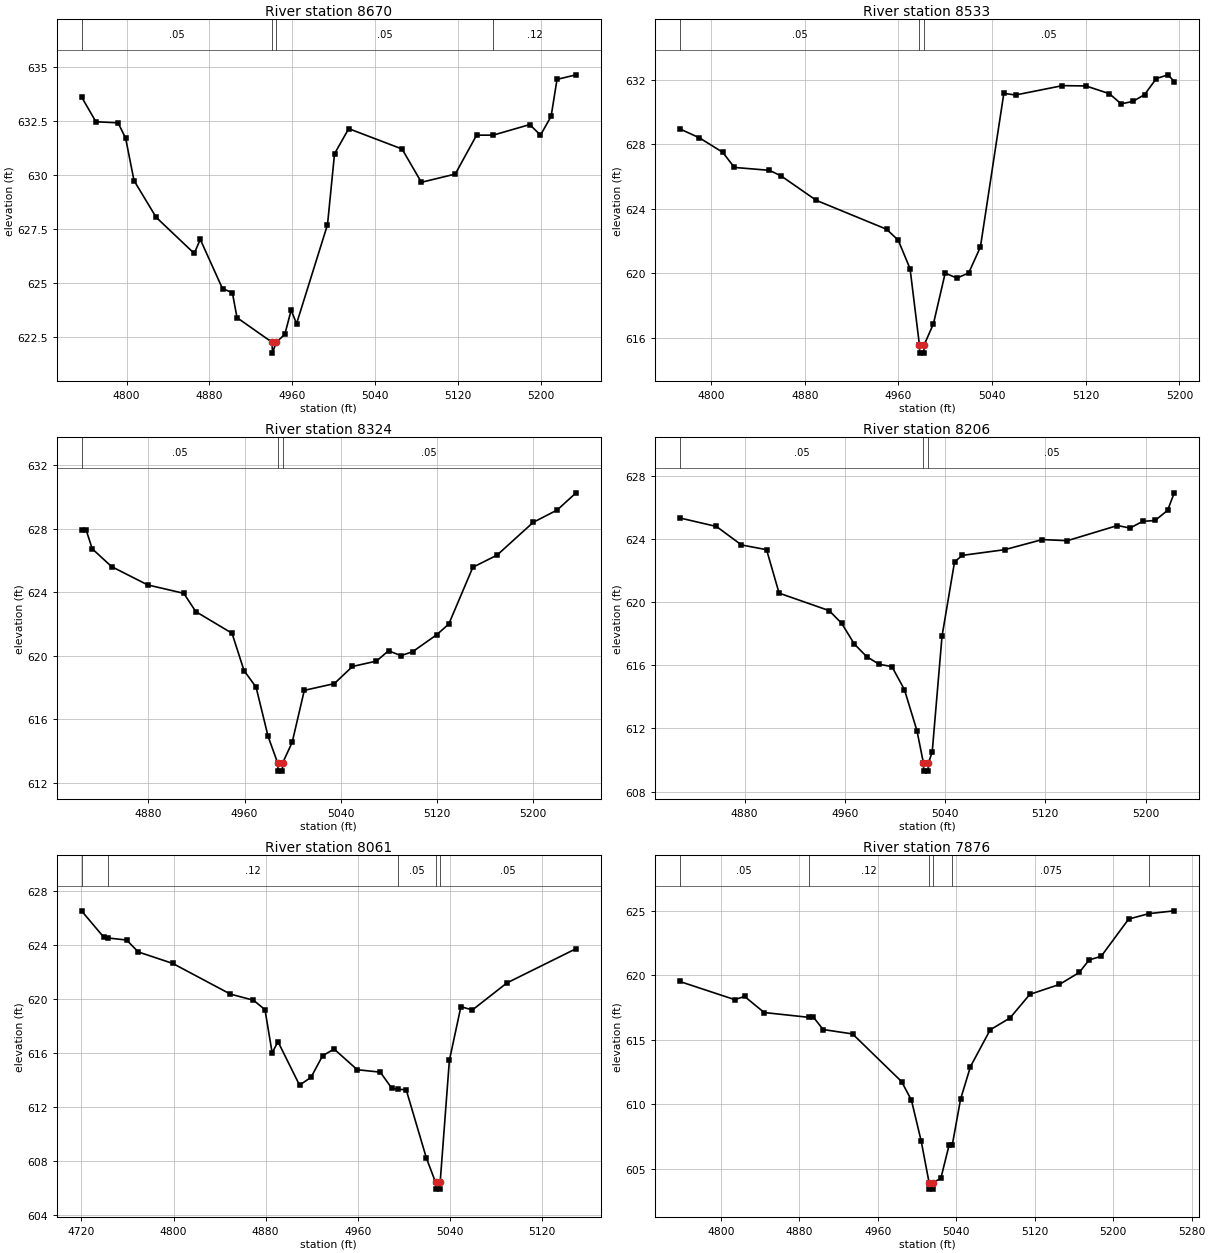
Type RM Length L Ch R = 1 ,8670    ,137,137,137
BEGIN DESCRIPTION:
Moorehead Branch 29.0
END DESCRIPTION:
XS GIS Cut Line= 3
      2403266.44      7025703.63      2403344.99      7025832.76
      2403662.48      7025909.17
#Sta/Elev= 30
  4756.5   633.6  4770.4  632.45  4791.8   632.4  4799.1  631.69  4807.2  629.73
  4828.6  628.03  4865.4  626.36  4871.2  627.01  4892.7  624.73  4902.2  624.55
  4906.7  623.39  4940.6  622.25  4940.9  621.75  4944.6  622.25  4952.9  622.62
    4959  623.74  4964.2  623.11  4994.1  627.69  5000.9  630.97  5014.6  632.13
  5066.1  631.19  5084.8  629.65  5117.5  630.03  5138.1  631.83  5154.1  631.83
  5189.5  632.32  5199.8  631.83  5210.1   632.7  5215.8  634.41  5234.2  634.62
#Mann= 4 ,-1 , 0
  4756.5     .05       0  4940.6    .033       0  4944.6     .05       0
  5154.1     .12       0
Bank Sta=4940.6,4944.6
XS Rating Curve= 0 ,0
Exp/Cntr=0.3,0.1

Type RM Length L Ch R = 1 ,8533    ,209,209,209
BEGIN DESCRIPTION:
Moorehead Branch 28.0
END DESCRIPTION:
XS GIS Cut Line= 3
      2403152.33      7025972.66       2403308.4      7025974.81
      2403574.31      7025958.38
#Sta/Elev= 30
  4773.1  628.94  4789.8  628.39  4809.8  627.49  4819.8  626.55  4849.8  626.37
  4859.8  626.02  4889.8  624.51  4949.8  622.72  4959.8  622.04  4969.9  620.27
  4977.9  615.54  4978.1  615.04  4981.6  615.04  4981.9  615.54  4989.9  616.87
  4999.9     620  5009.9  619.69    5020  620.01    5030  621.62    5050  631.14
    5060  631.04  5100.1  631.62  5120.2   631.6  5140.2  631.12  5150.2  630.49
  5160.2  630.64  5170.2  631.06  5180.3  632.06  5190.3  632.29  5195.6  631.87
#Mann= 3 ,-1 , 0
  4773.1     .05       0  4977.9    .033       0  4981.9     .05       0
Bank Sta=4977.9,4981.9
XS Rating Curve= 0 ,0
Exp/Cntr=0.3,0.1

Type RM Length L Ch R = 1 ,8324    ,118,118,118
BEGIN DESCRIPTION:
Moorehead Branch 27.3
END DESCRIPTION:
XS GIS Cut Line= 3
      2403154.07      7026154.61      2403390.09       7026166.3
      2403564.63      7026156.99
#Sta/Elev= 30
  4824.5   627.9  4828.4   627.9  4833.4  626.73  4849.5  625.61  4879.5  624.46
  4909.5  623.93  4919.5  622.78  4949.6  621.42  4959.6  619.07  4969.6  618.03
  4979.6  614.93  4987.6  613.25  4987.9  612.75  4991.4  612.75  4991.6  613.25
  4999.6  614.56  5009.7  617.83  5034.6  618.25  5049.7  619.33  5069.7  619.67
  5079.7  620.32    5090  620.01  5099.8  620.26  5119.8  621.33  5129.8     622
  5149.8  625.57  5169.9  626.33  5199.9  628.39  5219.9  629.17  5235.6  630.25
#Mann= 3 ,-1 , 0
  4824.5     .05       0  4987.6     .05       0  4991.6     .05       0
Bank Sta=4987.6,4991.6
XS Rating Curve= 0 ,0
Exp/Cntr=0.3,0.1

Type RM Length L Ch R = 1 ,8206    ,145,145,145
BEGIN DESCRIPTION:
Moorehead Branch 27.0
END DESCRIPTION:
XS GIS Cut Line= 3
      2403109.73       7026269.1      2403336.35      7026264.42
      2403504.27      7026262.09
#Sta/Elev= 30
  4828.3  625.33  4857.6  624.79  4877.6  623.62  4897.6  623.32  4907.6  620.57
  4947.6  619.46  4957.6  618.65  4967.6  617.35  4977.6  616.54  4987.6  616.06
  4997.6  615.92  5007.6  614.46  5017.6  611.86  5022.8   609.8    5023   609.3
  5026.5   609.3  5026.8   609.8  5029.8  610.54  5037.6  617.84  5047.6  622.55
  5053.8  622.96  5087.6  623.32  5117.6  623.96  5137.6  623.89  5177.6  624.85
  5187.6  624.69  5197.6  625.11  5207.6  625.17  5217.6  625.81  5222.9  626.92
#Mann= 3 ,-1 , 0
  4828.3     .05       0  5022.8     .05       0  5026.8     .05       0
Bank Sta=5022.8,5026.8
XS Rating Curve= 0 ,0
Exp/Cntr=0.3,0.1

Type RM Length L Ch R = 1 ,8061    ,185,185,185
BEGIN DESCRIPTION:
Moorehead Branch 26.0
END DESCRIPTION:
XS GIS Cut Line= 3
      2402999.87      7026397.59        2403279.        7026410.
        2403429.        7026410.
#Sta/Elev= 30
  4720.1  626.53  4739.2   624.6  4743.3  624.52  4759.3  624.37  4769.3  623.49
  4799.3  622.64  4849.4  620.37  4869.4  619.92  4879.4  619.22  4885.6  616.03
  4890.7  616.85  4909.4  613.64  4919.4  614.22  4929.4  615.81  4939.4  616.31
  4959.5  614.78  4979.5   614.6  4989.5  613.41    4995  613.33    5002   613.3
  5019.5  608.26  5027.5  606.45  5027.8  605.95  5031.3  605.95  5031.5  606.45
  5039.5  615.47  5049.5  619.44  5059.5   619.2  5089.5   621.2  5149.5  623.73
#Mann= 5 ,-1 , 0
  4720.1     .05       0  4743.3     .12       0    4995     .05       0
  5027.5    .033       0  5031.5     .05       0
Bank Sta=5027.5,5031.5
XS Rating Curve= 0 ,0
Exp/Cntr=0.3,0.1

Type RM Length L Ch R = 1 ,7876    ,91,91,91
BEGIN DESCRIPTION:
Moorehead Branch 25.3
END DESCRIPTION:
XS GIS Cut Line= 3
      2402992.91      7026554.13      2403270.93      7026563.48
       2403495.1      7026535.39
#Sta/Elev= 30
  4758.1  619.52  4814.2  618.11  4824.2  618.36  4844.2  617.11  4889.4  616.74
  4894.3  616.76  4904.3  615.79  4934.3  615.45  4984.3  611.75  4994.3  610.31
  5004.3  607.12  5012.3  603.91  5012.6  603.41  5016.1  603.41  5016.3  603.91
  5024.3  604.25  5032.8  606.86    5036  606.86  5044.4  610.39  5054.5  612.92
  5074.6  615.77  5094.8  616.69    5115  618.52  5145.2  619.29  5165.4  620.22
  5175.4  621.19  5187.7  621.47  5215.7  624.36  5236.2  624.78  5262.2     625
#Mann= 6 ,-1 , 0
  4758.1     .05       0  4889.4     .12       0  5012.3     .07       0
  5016.3     .12       0    5036    .075       0  5236.2      .1       0
Bank Sta=5012.3,5016.3
XS Rating Curve= 0 ,0
Exp/Cntr=0.3,0.1

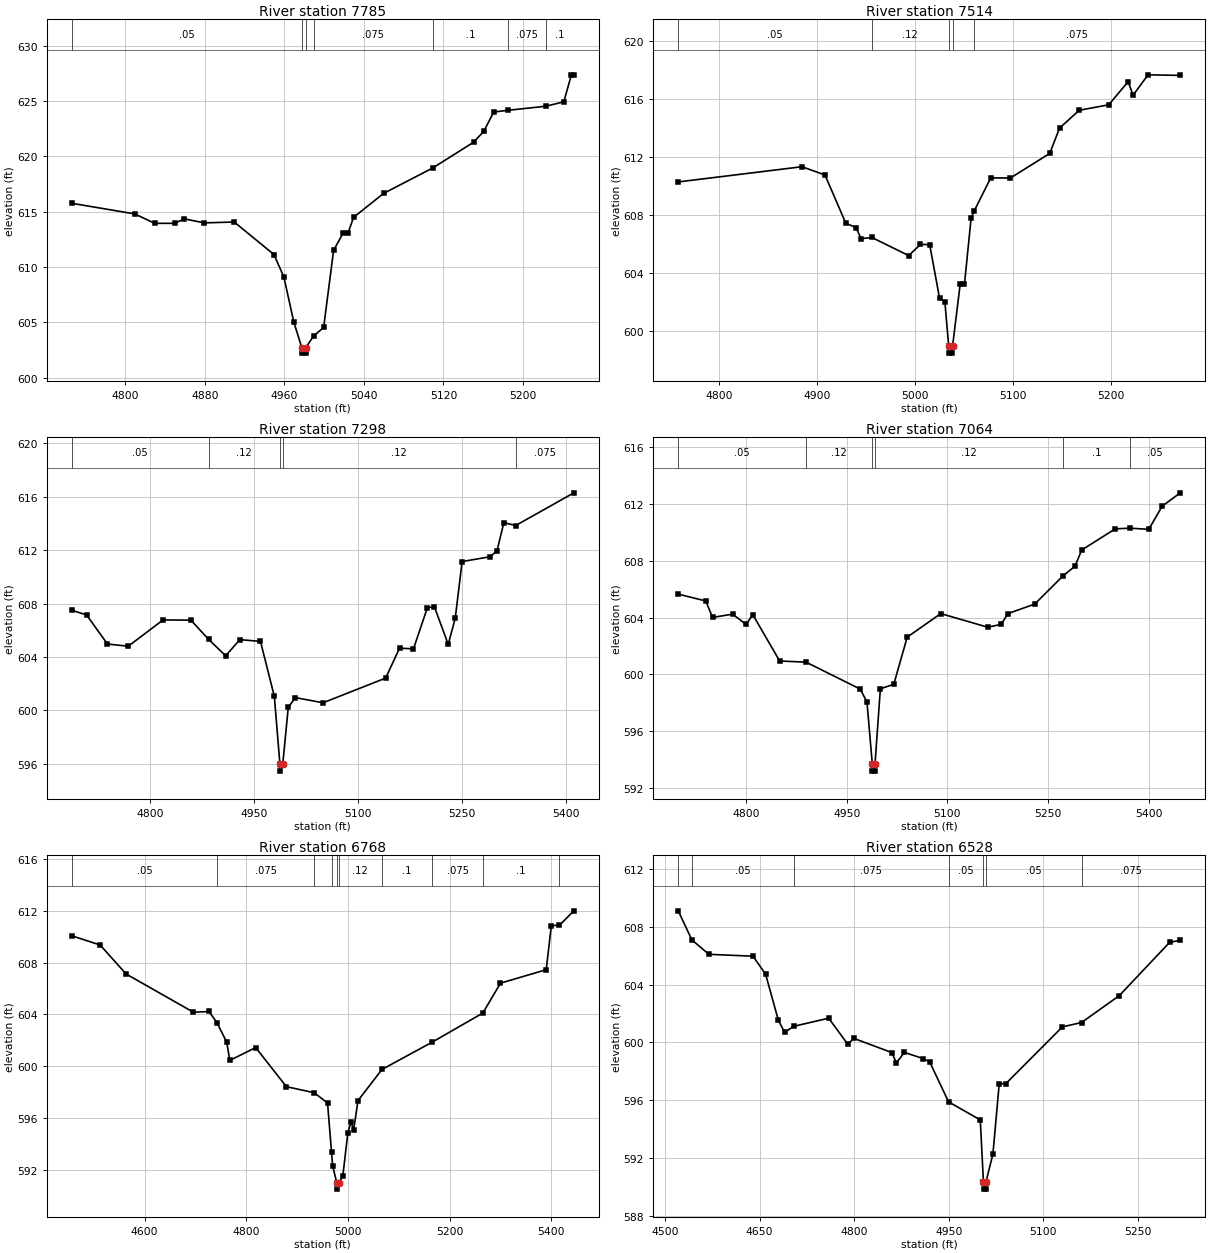
Type RM Length L Ch R = 1 ,7785    ,271,271,271
BEGIN DESCRIPTION:
Moorehead Branch 25.0
END DESCRIPTION:
XS GIS Cut Line= 3
      2403025.62      7026628.89      2403303.64      7026638.24
        2403529.        7026610.
#Sta/Elev= 30
    4746  615.76  4809.4   614.8  4829.4  613.95  4849.4  613.95  4859.4  614.35
  4879.5  613.99  4909.5  614.07  4949.5  611.13  4959.5  609.09  4969.5  605.02
  4977.5  602.73  4977.8  602.23  4981.3  602.23  4981.5  602.73  4989.3  603.77
  4999.5  604.55  5009.5  611.51  5019.4  613.12  5024.2  613.12  5029.6  614.49
  5059.8  616.65  5109.5  618.96  5150.5  621.28  5160.6  622.25  5170.7     624
  5185.2  624.16  5222.8  624.52  5241.2  624.92  5248.8  627.36  5251.3  627.36
#Mann= 7 ,-1 , 0
    4746     .05       0  4977.5     .07       0  4981.5     .05       0
  4989.3    .075       0  5109.5      .1       0  5185.2    .075       0
  5222.8      .1       0
Bank Sta=4977.5,4981.5
XS Rating Curve= 0 ,0
Exp/Cntr=0.3,0.1

Type RM Length L Ch R = 1 ,7514    ,216,216,216
BEGIN DESCRIPTION:
Moorehead Branch 24.0
END DESCRIPTION:
XS GIS Cut Line= 3
      2402978.91      7026799.45      2403252.24      7026902.24
      2403471.82       7026918.6
#Sta/Elev= 30
  4758.4  610.27  4884.6  611.32  4908.1  610.75  4929.4  607.41  4939.7  607.12
    4945  606.35    4956  606.43  4993.5  605.18  5005.5  605.95  5014.9  605.94
    5025  602.23  5030.4  601.99  5034.3  598.94  5034.5  598.44    5038  598.44
  5038.3  598.94    5046  603.19  5050.4  603.19  5057.2  607.78  5060.3  608.26
  5077.2  610.55  5097.3  610.54  5137.4  612.24  5147.4  613.99  5167.5  615.22
  5197.6   615.6  5217.4   617.2  5222.4  616.26  5237.7  617.67  5270.6  617.63
#Mann= 5 ,-1 , 0
  4758.4     .05       0    4956     .12       0  5034.3     .07       0
  5038.3     .12       0  5060.3    .075       0
Bank Sta=5034.3,5038.3
XS Rating Curve= 0 ,0
Exp/Cntr=0.3,0.1

Type RM Length L Ch R = 1 ,7298    ,234,234,234
BEGIN DESCRIPTION:
Moorehead Branch 23.0
END DESCRIPTION:
XS GIS Cut Line= 3
      2402817.71      7027044.76      2403282.61      7027084.48
      2403539.66      7027063.45
#Sta/Elev= 30
  4687.5   607.5  4708.9  607.15    4739  604.97  4769.1  604.81  4819.3  606.78
  4859.4  606.76    4885  605.32  4909.6  604.09    4930   605.3  4959.8  605.17
  4979.8  601.05  4987.9  595.95  4988.1  595.45  4991.9  595.95  4999.9  600.22
    5010  600.96  5050.1  600.57  5140.4  602.42  5160.5  604.66  5180.6  604.61
  5200.6  607.69  5210.7  607.77  5230.7  604.95  5240.8  606.89  5250.8  611.15
  5290.9  611.51    5301  611.94    5311  614.07  5328.1  613.85    5412   616.3
#Mann= 5 ,-1 , 0
  4687.5     .05       0    4885     .12       0  4987.9     .07       0
  4991.9     .12       0  5328.1    .075       0
Bank Sta=4987.9,4991.9
XS Rating Curve= 0 ,0
Exp/Cntr=0.3,0.1

Type RM Length L Ch R = 1 ,7064    ,296,296,296
BEGIN DESCRIPTION:
Moorehead Branch 22.0
END DESCRIPTION:
XS GIS Cut Line= 3
      2402777.92      7027278.39      2403221.87      7027294.75
      2403526.01      7027292.43
#Sta/Elev= 30
  4698.9  605.66    4740  605.18    4750  604.02    4780  604.25    4800  603.53
  4810.1  604.21  4850.1  600.95  4889.4  600.87  4970.2  598.97  4980.2  598.06
  4988.2  593.69  4988.4  593.19  4991.9  593.19  4992.2  593.69  5000.2  598.99
  5020.2  599.31  5040.2  602.63  5090.2  604.29  5160.3  603.33  5180.3  603.53
  5190.3  604.29  5230.3  604.96  5272.7  606.96  5290.3  607.63  5300.3  608.77
  5350.3  610.26  5371.7  610.31  5400.3  610.23  5420.3  611.86  5447.3   612.8
#Mann= 6 ,-1 , 0
  4698.9     .05       0  4889.4     .12       0  4988.2     .07       0
  4992.2     .12       0  5272.7      .1       0  5371.7     .05       0
Bank Sta=4988.2,4992.2
XS Rating Curve= 0 ,0
Exp/Cntr=0.3,0.1

Type RM Length L Ch R = 1 ,6768    ,240,240,240
BEGIN DESCRIPTION:
Moorehead Branch 21.0
END DESCRIPTION:
XS GIS Cut Line= 3
      2402544.34      7027505.02      2402962.54      7027589.13
      2403523.25      7027570.44
#Sta/Elev= 30
  4456.9  610.07  4512.7  609.36  4563.7  607.12  4696.3  604.16  4726.9  604.22
  4742.5  603.35  4761.8  601.84  4767.7  600.44  4818.7  601.43  4879.1  598.41
  4933.8  597.94    4960  597.15  4967.9  593.33    4970  592.31    4978  590.99
  4978.2  590.49    4982  590.99    4990  591.48    5000  594.86  5006.2  595.69
  5011.2  595.03    5020  597.34  5067.1  599.74  5166.3  601.86  5265.5   604.1
  5300.2  606.41  5390.2  607.45  5400.2  610.86  5416.2  610.88  5444.5     612
#Mann= 10 ,-1 , 0
  4456.9     .05       0  4742.5    .075       0  4933.8     .05       0
  4967.9     .12       0    4978     .07       0    4982     .12       0
  5067.1      .1       0  5166.3    .075       0  5265.5      .1       0
  5416.2     .05       0
Bank Sta=4978,4982
XS Rating Curve= 0 ,0
Exp/Cntr=0.3,0.1

Type RM Length L Ch R = 1 ,6528    ,119,119,119
BEGIN DESCRIPTION:
Moorehead Branch 20.3
END DESCRIPTION:
XS GIS Cut Line= 3
      2402600.41      7027822.76      2402948.52      7027834.45
      2403395.59      7027804.17
#Sta/Elev= 30
  4520.9   609.1  4542.5  607.09  4569.5  606.09  4639.6  605.96  4659.6   604.7
  4679.6  601.54  4689.6  600.69  4704.3  601.11  4759.6  601.67  4789.6  599.88
  4799.7  600.27  4859.7  599.29  4866.9  598.58  4879.7   599.3  4909.8  598.87
  4919.8  598.64  4949.7  595.88    5000  594.63    5005  590.34  5005.3  589.84
  5008.8  589.84    5009  590.34    5020  592.25  5030.1  597.15  5040.1  597.12
  5130.3  601.07  5160.6  601.37  5220.5  603.23  5300.4  606.92  5317.3  607.06
#Mann= 7 ,-1 , 0
  4520.9    .075       0  4542.5     .05       0  4704.3    .075       0
  4949.7     .05       0    5005     .05       0    5009     .05       0
  5160.6    .075       0
Bank Sta=5005,5009
XS Rating Curve= 0 ,0
Exp/Cntr=0.3,0.1

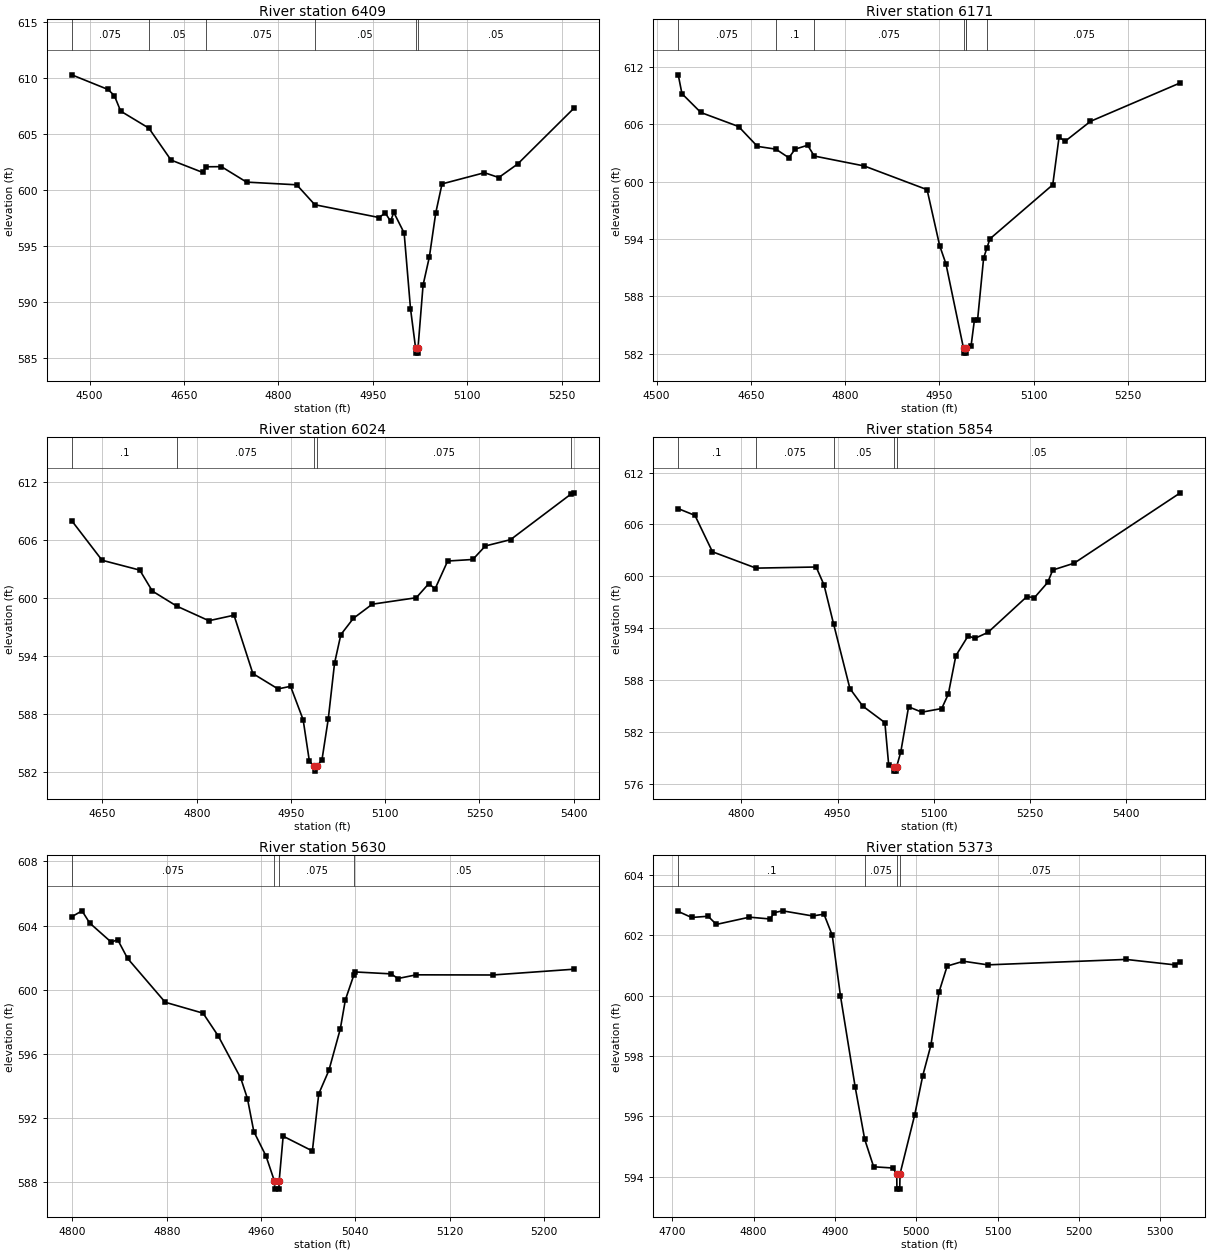
Type RM Length L Ch R = 1 ,6409    ,238,238,238
BEGIN DESCRIPTION:
Moorehead Branch 20.0
END DESCRIPTION:
XS GIS Cut Line= 3
      2402551.36      7027944.25      2402899.45      7027955.93
      2403348.04      7027925.56
#Sta/Elev= 30
  4471.7  610.25  4529.4  608.94  4539.4  608.39  4549.4  607.01  4594.2  605.49
  4629.4  602.64  4679.5  601.54  4685.5  602.04  4709.5  602.05  4749.5  600.67
  4829.2  600.43    4858  598.65  4959.9  597.51  4969.9  597.91  4978.4  597.18
  4983.4  597.97  4999.9  596.13    5010  589.38    5018   585.9  5018.2   585.4
  5021.7   585.4    5022   585.9    5030  591.48    5040  593.99  5050.1  597.91
  5060.1  600.51  5127.6  601.51  5150.3  601.08  5180.4  602.29  5269.6  607.26
#Mann= 6 ,-1 , 0
  4471.7    .075       0  4594.2     .05       0  4685.5    .075       0
    4858     .05       0    5018     .05       0    5022     .05       0
Bank Sta=5018,5022
XS Rating Curve= 0 ,0
Exp/Cntr=0.3,0.1

Type RM Length L Ch R = 1 ,6171    ,147,147,147
BEGIN DESCRIPTION:
Moorehead Branch 19.3
END DESCRIPTION:
XS GIS Cut Line= 3
      2402563.05      7028163.87      2403034.96      7028166.21
      2403362.04      7028163.87
#Sta/Elev= 30
  4534.4  611.19  4540.3  609.22  4570.3  607.25  4630.4  605.78  4660.4   603.7
  4689.8  603.41  4710.4  602.51  4720.4  603.41  4740.4  603.82  4750.8  602.69
  4830.4  601.65  4930.4  599.17  4950.4  593.32  4960.4  591.41  4988.4  582.56
  4988.6  582.06  4992.1  582.06  4992.4  582.56  4993.1  582.58  5000.4  582.81
  5005.8  585.56  5010.8  585.56  5020.4  592.02  5025.4  593.02  5030.4  594.02
  5130.4  599.68  5140.4  604.65  5150.4  604.25  5190.4  606.32  5333.4  610.35
#Mann= 7 ,-1 , 0
  4534.4    .075       0  4689.8      .1       0  4750.8    .075       0
  4988.4     .05       0  4992.4    .075       0  4993.1     .05       0
  5025.4    .075       0
Bank Sta=4988.4,4992.4
XS Rating Curve= 0 ,0
Exp/Cntr=0.3,0.1

Type RM Length L Ch R = 1 ,6024    ,170,170,170
BEGIN DESCRIPTION:
Moorehead Branch 19.0
END DESCRIPTION:
XS GIS Cut Line= 3
      2402630.79      7028311.06      2403102.72       7028313.4
      2403429.77      7028311.06
#Sta/Elev= 30
  4601.2     608  4649.4  603.91  4709.4  602.89  4729.4  600.72  4768.3  599.16
  4819.4  597.65  4859.4  598.22  4889.4  592.18  4929.4  590.59  4949.4  590.86
  4969.4   587.4  4979.4  583.08  4987.4  582.58  4987.7  582.08  4991.4  582.58
  4999.4  583.26  5009.4  587.49  5019.4  593.26  5029.4  596.21  5049.4   597.9
  5079.4  599.36  5149.4  600.03  5169.4  601.49  5179.4  600.95  5199.4  603.83
  5239.4  603.99  5259.4  605.39  5299.4  606.04  5395.4  610.75  5400.2  610.89
#Mann= 5 ,-1 , 0
  4601.2      .1       0  4768.3    .075       0  4987.4     .07       0
  4991.4    .075       0  5395.4      .1       0
Bank Sta=4987.4,4991.4
XS Rating Curve= 0 ,0
Exp/Cntr=0.3,0.1

Type RM Length L Ch R = 1 ,5854    ,224,224,224
BEGIN DESCRIPTION:
Moorehead Branch 18.0
END DESCRIPTION:
XS GIS Cut Line= 3
      2402633.08      7028388.15      2402953.19      7028427.88
      2403399.39      7028544.68
#Sta/Elev= 30
  4701.3  607.83  4727.4  607.05  4754.7  602.84  4822.8  600.95  4916.6  601.08
  4928.9     599  4943.8   594.5  4969.3  587.02  4989.4  584.99  5023.9  583.08
  5029.9  578.14  5038.2  577.97  5038.5  577.47    5042  577.47  5042.2  577.97
  5048.7  579.68  5060.9  584.91  5081.6  584.29  5112.6  584.71  5122.9  586.37
  5134.7  590.82  5153.9  593.12  5164.2  592.82  5184.9  593.52  5245.6  597.66
  5257.3  597.53    5278  599.29    5286  600.73  5319.3  601.52  5485.1  609.66
#Mann= 5 ,-1 , 0
  4701.3      .1       0  4822.8    .075       0  4943.8     .05       0
  5038.2     .05       0  5042.2     .05       0
Bank Sta=5038.2,5042.2
XS Rating Curve= 0 ,0
Exp/Cntr=0.3,0.1

Type RM Length L Ch R = 1 ,5630    ,257,257,257
BEGIN DESCRIPTION:
Moorehead Branch 17.0
END DESCRIPTION:
XS GIS Cut Line= 3
      2402644.76      7028542.35      2402862.07      7028624.13
      2403027.93      7028724.58
#Sta/Elev= 30
  4799.4  604.55  4808.1  604.92  4814.6  604.16    4833  602.96  4838.3  603.13
  4846.7  601.96  4878.7  599.22  4910.8  598.54  4923.7  597.12  4942.8  594.49
  4948.5  593.21  4953.9  591.16  4964.2  589.64  4971.4  588.07  4971.7  587.57
  4975.2  587.57  4975.4  588.07  4978.8  590.87  5003.6  589.95    5009  593.51
  5017.6  594.97  5027.3  597.56  5031.6  599.37  5038.8  600.92  5039.7  601.11
  5070.4  600.99  5076.2   600.7  5091.7  600.93  5156.6  600.92  5225.5  601.28
#Mann= 4 ,-1 , 0
  4799.4    .075       0  4971.4     .07       0  4975.4    .075       0
  5038.8     .05       0
Bank Sta=4971.4,4975.4
XS Rating Curve= 0 ,0
Exp/Cntr=0.3,0.1

Type RM Length L Ch R = 1 ,5373    ,164,164,164
BEGIN DESCRIPTION:
Moorehead Branch 16.0
END DESCRIPTION:
XS GIS Cut Line= 3
      2402492.93      7028804.03      2402752.26      7028853.09
      2403105.73      7028853.09
#Sta/Elev= 30
  4707.3  602.79  4723.7  602.59    4744  602.63  4754.2  602.36  4794.9   602.6
  4820.2  602.54  4825.4  602.75  4835.6  602.81  4872.6  602.64  4886.5   602.7
  4896.7     602  4906.8  599.99  4924.9  596.97  4936.6  595.24  4947.6  594.33
  4971.2  594.29    4976  594.09  4976.2  593.59  4979.7  593.59    4980  594.09
    4998  596.04    5008  597.35    5018  598.36    5028  600.12    5038  600.98
    5058  601.14    5088  601.02    5258   601.2    5318  601.02  5324.7  601.13
#Mann= 4 ,-1 , 0
  4707.3      .1       0  4936.6    .075       0    4976     .07       0
    4980    .075       0
Bank Sta=4976,4980
XS Rating Curve= 0 ,0
Exp/Cntr=0.3,0.1

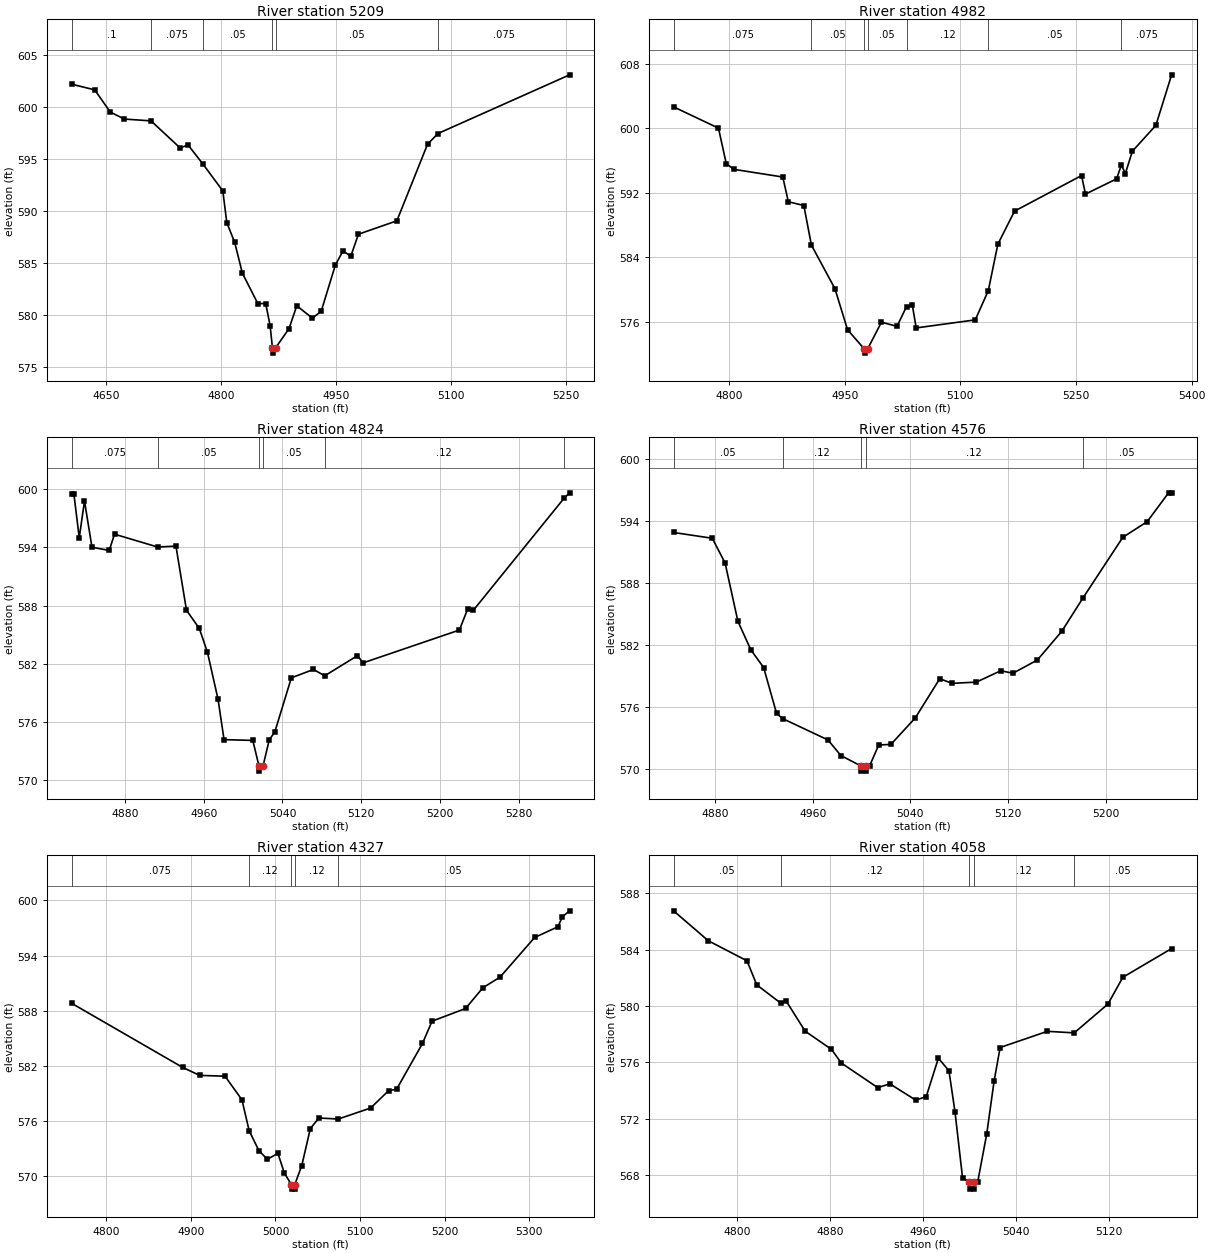
Type RM Length L Ch R = 1 ,5209    ,227,227,227
BEGIN DESCRIPTION:
Moorehead Branch 15.5
END DESCRIPTION:
XS GIS Cut Line= 3
      2402439.17      7028953.55      2402756.94      7029004.95
      2403084.04      7028990.93
#Sta/Elev= 30
  4605.5  602.21  4635.7  601.66    4656  599.52  4674.2  598.85  4709.1  598.67
  4747.1  596.06  4757.3  596.36  4776.9   594.5  4802.7  591.92  4807.9  588.86
  4818.1  586.98  4828.2  583.99  4848.4  581.06  4858.6  581.07  4864.4  578.92
  4867.4  576.79  4867.7  576.29  4871.4  576.79    4889  578.65  4899.1  580.85
  4919.4  579.67  4930.9  580.31  4949.5   584.8  4959.5  586.15  4969.5  585.62
  4979.5  587.75  5029.6  589.04  5069.6  596.42  5083.1  597.45  5254.8  603.11
#Mann= 6 ,-1 , 0
  4605.5      .1       0  4709.1    .075       0  4776.9     .05       0
  4867.4     .05       0  4871.4     .05       0  5083.1    .075       0
Bank Sta=4867.4,4871.4
XS Rating Curve= 0 ,0
Exp/Cntr=0.3,0.1

Type RM Length L Ch R = 1 ,4982    ,158,158,158
BEGIN DESCRIPTION:
Moorehead Branch 15.0
END DESCRIPTION:
XS GIS Cut Line= 3
      2402411.17      7029089.06      2402735.91      7029126.44
      2403048.99      7029187.19
#Sta/Elev= 30
  4728.2  602.67  4786.4  600.03  4796.5  595.63  4806.5  594.91  4869.8  593.96
    4877  590.89  4897.1  590.42  4906.9  585.51  4937.4   580.1  4953.8  574.99
  4975.7  572.59  4975.9  572.09  4979.7  572.59  4997.8  575.94  5017.9  575.41
  5030.3  577.88  5037.8  578.04  5042.8  575.22  5119.4  576.22  5136.3  579.85
  5148.7  585.62  5170.3  589.72  5257.2  594.14  5262.3  591.84  5302.7  593.73
  5308.9  595.47    5314  594.38  5323.1  597.16  5353.6  600.38    5374  606.65
#Mann= 7 ,-1 , 0
  4728.2    .075       0  4906.9     .05       0  4975.7     .05       0
  4979.7     .05       0  5030.3     .12       0  5136.3     .05       0
  5308.9    .075       0
Bank Sta=4975.7,4979.7
XS Rating Curve= 0 ,0
Exp/Cntr=0.3,0.1

Type RM Length L Ch R = 1 ,4824    ,248,248,248
BEGIN DESCRIPTION:
Moorehead Branch 14.0
END DESCRIPTION:
XS GIS Cut Line= 3
      2402469.61      7029201.22        2402629.        7029260.
        2402929.        7029410.
#Sta/Elev= 30
    4826  599.56  4828.3  599.56  4833.8     595  4839.1   598.8  4846.7  594.02
  4864.2   593.7  4869.6  595.37  4913.3  594.05  4931.9  594.14  4942.6  587.52
  4955.6  585.65  4963.9  583.17  4974.6  578.34  4980.7  574.17  5009.9  574.09
  5016.2  571.42  5016.5  570.92  5020.2  571.42  5026.6  574.16  5032.2  574.96
    5049  580.55  5071.4  581.41  5082.9  580.76  5116.1  582.84  5121.7  582.09
  5219.5  585.48  5227.9  587.65  5233.5   587.5  5325.6  599.07  5331.3  599.64
#Mann= 6 ,-1 , 0
    4826    .075       0  4913.3     .05       0  5016.2     .05       0
  5020.2     .05       0  5082.9     .12       0  5325.6     .05       0
Bank Sta=5016.2,5020.2
XS Rating Curve= 0 ,0
Exp/Cntr=0.3,0.1

Type RM Length L Ch R = 1 ,4576    ,249,249,249
BEGIN DESCRIPTION:
Moorehead Branch 13.0
END DESCRIPTION:
XS GIS Cut Line= 3
      2402478.97      7029459.99        2402629.        7029510.
      2402878.96        7029510.
#Sta/Elev= 30
    4846  592.86  4877.7   592.3  4888.2  589.91  4898.7  584.26  4909.3   581.5
  4919.8  579.78  4930.4  575.34  4935.3  574.84  4972.5  572.77  4983.1  571.26
  4999.5  570.25  4999.8  569.75  5003.3  569.75  5003.5  570.25  5006.6  570.25
  5014.1  572.28  5024.1  572.34  5044.1  574.91  5064.1   578.7  5074.1  578.25
  5094.1  578.37  5114.1  579.47  5124.1  579.23  5144.1  580.51  5164.1  583.29
  5181.2  586.47  5214.1  592.39  5234.1  593.91  5251.6   596.7  5254.1   596.7
#Mann= 5 ,-1 , 0
    4846     .05       0  4935.3     .12       0  4999.5     .07       0
  5003.5     .12       0  5181.2     .05       0
Bank Sta=4999.5,5003.5
XS Rating Curve= 0 ,0
Exp/Cntr=0.3,0.1

Type RM Length L Ch R = 1 ,4327    ,269,269,269
BEGIN DESCRIPTION:
Moorehead Branch 12.0
END DESCRIPTION:
XS GIS Cut Line= 3
       2402387.8      7029703.52        2402629.        7029710.
      2402969.54      7029642.77
#Sta/Elev= 30
  4759.1  588.81  4890.3  581.83  4910.4  580.96  4940.4  580.87  4960.4   578.3
  4968.9  574.94  4980.4  572.77  4990.4  571.83  5002.9  572.47  5010.6  570.31
  5018.8  569.08    5019  568.58  5022.5  568.58  5022.8  569.08  5031.1  571.15
  5041.2  575.17  5051.3  576.32  5074.2  576.21  5112.5  577.41  5133.7   579.3
  5143.1  579.45  5173.7  584.44    5185  586.86  5224.6  588.24    5245  590.49
  5265.4  591.66  5306.2  595.97  5333.8  597.14  5338.9  598.22  5347.5  598.87
#Mann= 5 ,-1 , 0
  4759.1    .075       0  4968.9     .12       0  5018.8     .07       0
  5022.8     .12       0  5074.2     .05       0
Bank Sta=5018.8,5022.8
XS Rating Curve= 0 ,0
Exp/Cntr=0.3,0.1

Type RM Length L Ch R = 1 ,4058    ,289,289,289
BEGIN DESCRIPTION:
Moorehead Branch 11.0
END DESCRIPTION:
XS GIS Cut Line= 3
       2402530.3      7029981.55        2402779.        7029910.
      2402941.48       7029862.4
#Sta/Elev= 30
  4745.6  586.76  4775.5  584.63  4808.7  583.21  4817.1   581.5  4837.6  580.21
  4842.4  580.35  4858.7  578.21  4881.3  576.92  4889.9  575.94  4921.1   574.2
  4931.5  574.47  4953.8  573.31  4962.8  573.57  4973.2  576.29  4982.3   575.4
  4987.5  572.48    4994  567.79  4999.8  567.49    5000  566.99  5003.5  566.99
  5003.8  567.49    5007  567.49  5014.8  570.92  5021.1  574.66  5026.3  577.05
  5066.9   578.2    5090  578.09    5119  580.14  5131.8  582.04  5173.7  584.08
#Mann= 5 ,-1 , 0
  4745.6     .05       0  4837.6     .12       0  4999.8     .07       0
  5003.8     .12       0    5090     .05       0
Bank Sta=4999.8,5003.8
XS Rating Curve= 0 ,0
Exp/Cntr=0.3,0.1

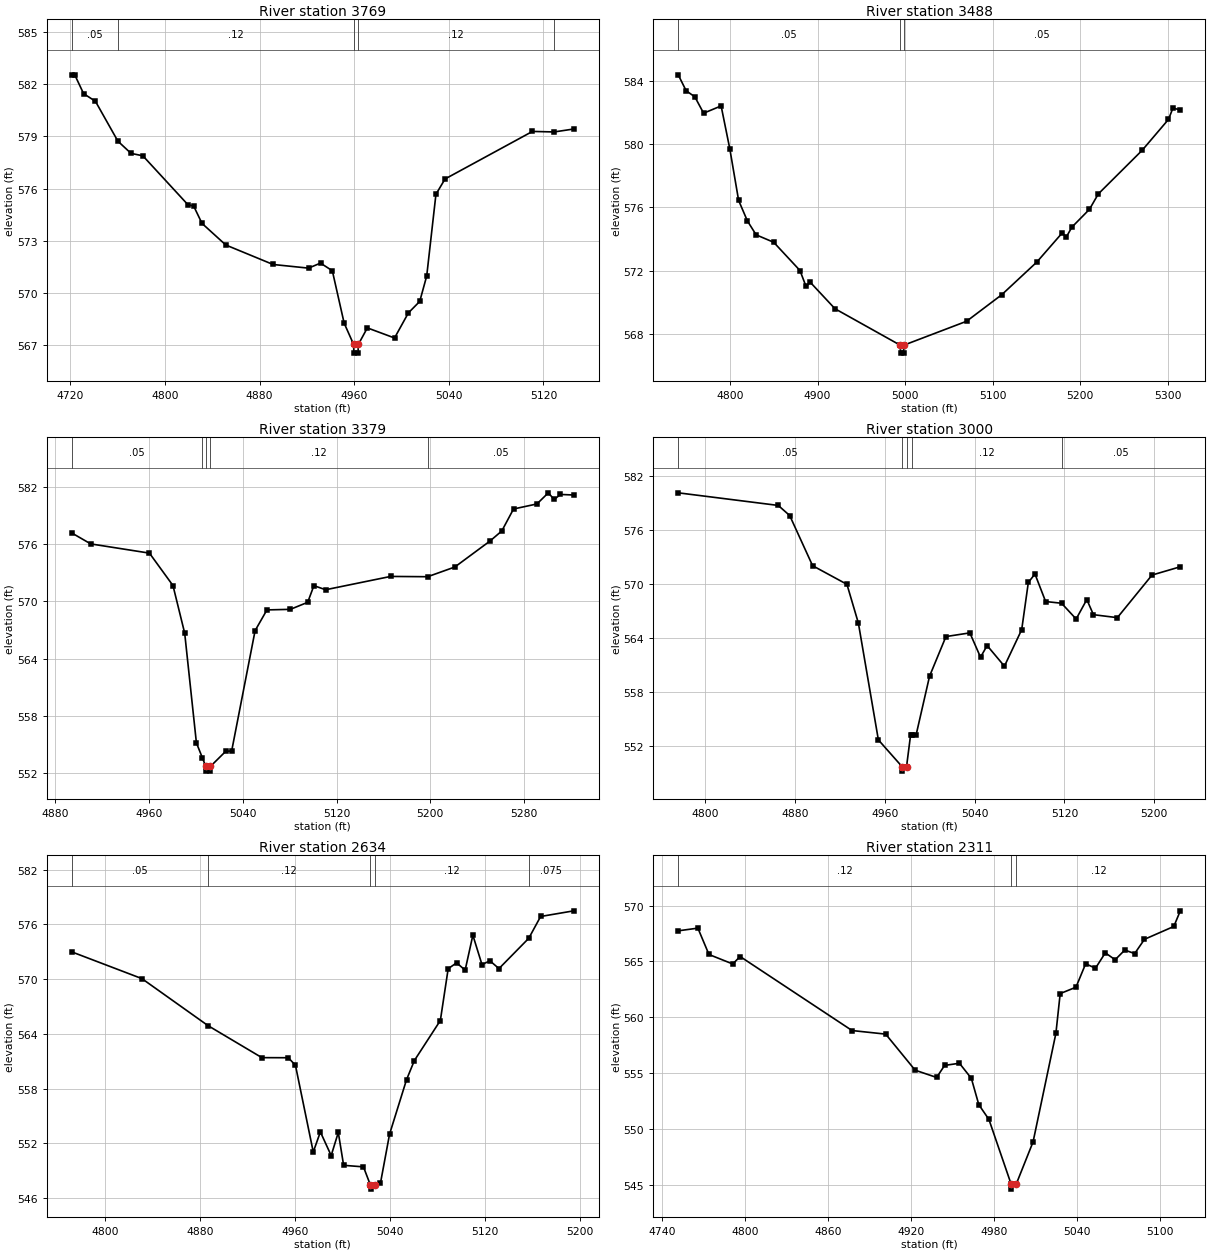
Type RM Length L Ch R = 1 ,3769    ,281,281,281
BEGIN DESCRIPTION:
Moorehead Branch 10.0
END DESCRIPTION:
XS GIS Cut Line= 3
        2402629.        7030160.       2402883.1      7030147.42
        2403029.        7030060.
#Sta/Elev= 30
  4721.2  582.53  4723.7  582.53  4731.2  581.45  4741.2  581.01  4760.2  578.72
  4771.3  578.02  4781.3  577.88  4819.3  575.08  4824.3  574.99  4831.3     574
  4851.4  572.76  4891.4  571.64  4921.4  571.43  4931.5  571.72  4941.5  571.28
  4951.5  568.27  4959.5  567.05  4959.7  566.55  4963.2  566.55  4963.5  567.05
  4971.1     568  4994.1  567.42  5005.8  568.86  5015.4  569.52  5021.3  570.98
  5029.1  575.67  5036.8  576.55  5110.7  579.28    5129  579.25  5145.7  579.42
#Mann= 5 ,-1 , 0
  4721.2     .05       0  4760.2     .12       0  4959.5     .07       0
  4963.5     .12       0    5129     .05       0
Bank Sta=4959.5,4963.5
XS Rating Curve= 0 ,0
Exp/Cntr=0.3,0.1

Type RM Length L Ch R = 1 ,3488    ,109,109,109
BEGIN DESCRIPTION:
Moorehead Branch 9.2
END DESCRIPTION:
XS GIS Cut Line= 3
      2402570.05      7030371.71      2402827.03      7030360.03
      2403142.44      7030334.33
#Sta/Elev= 30
  4740.8  584.36  4749.8  583.36  4759.8  582.97  4769.8  581.94  4789.8   582.4
  4799.8  579.67  4809.8  576.44  4819.8  575.15  4829.8  574.27  4849.9   573.8
  4879.9  572.02  4886.8  571.02  4891.8  571.27  4919.9  569.61  4994.5  567.31
  4994.8  566.81  4998.3  566.81  4998.5  567.31  5070.3  568.82  5110.4  570.49
  5150.5  572.55  5179.4  574.38  5184.4  574.15  5190.7  574.76  5210.7  575.88
  5220.8  576.85  5270.9   579.6    5301  581.55  5306.1  582.27  5314.5  582.14
#Mann= 3 ,-1 , 0
  4740.8     .05       0  4994.5    .033       0  4998.5     .05       0
Bank Sta=4994.5,4998.5
XS Rating Curve= 0 ,0
Exp/Cntr=0.3,0.1

Type RM Length L Ch R = 1 ,3379    ,379,379,379
BEGIN DESCRIPTION:
Moorehead Branch 9.0
END DESCRIPTION:
XS GIS Cut Line= 3
      2402672.85      7030444.14      2402873.75      7030430.12
      2403100.37      7030413.77
#Sta/Elev= 30
    4894   577.2  4910.2  576.05  4960.3  575.08  4980.4  571.67  4990.4  566.66
  5000.4  555.13  5005.5  553.56  5008.4  552.66  5008.7  552.16  5012.2  552.16
  5012.4  552.66  5025.4  554.24  5030.5  554.28  5050.5  566.93  5060.6  569.11
  5080.6  569.17  5095.4  569.91  5100.7  571.66  5110.7  571.23  5166.2  572.63
  5197.8   572.6    5221  573.62    5251  576.35  5261.1  577.41  5271.1  579.72
  5291.1  580.25  5300.8  581.42  5305.8  580.72  5311.2  581.25  5322.6  581.19
#Mann= 5 ,-1 , 0
    4894     .05       0  5005.5     .12       0  5008.4     .05       0
  5012.4     .12       0  5197.8     .05       0
Bank Sta=5008.4,5012.4
XS Rating Curve= 0 ,0
Exp/Cntr=0.3,0.1

Type RM Length L Ch R = 1 ,3000    ,366,366,366
BEGIN DESCRIPTION:
Moorehead Branch 8.0
END DESCRIPTION:
XS GIS Cut Line= 3
      2402651.79       7030801.6      2402855.06      7030759.55
      2403059.38      7030634.17
#Sta/Elev= 30
  4775.9  580.14    4865  578.74  4875.2  577.62  4895.6  572.05  4926.2  569.98
  4936.4  565.67  4954.2  552.71  4975.3  549.74  4975.5  549.24  4979.3  549.74
  4982.9  553.25  4984.6  553.25  4987.8  553.25  4999.8  559.78  5014.4  564.18
  5035.7  564.59  5045.2  561.89  5051.1  563.18  5066.5  560.89  5081.9  564.95
  5087.8  570.19  5093.7  571.13  5103.2  568.07  5117.4  567.88  5130.4  566.13
  5139.9  568.29  5145.8  566.61  5167.1  566.28    5198  571.01  5223.2  571.93
#Mann= 5 ,-1 , 0
  4775.9     .05       0  4975.3     .07       0  4979.3     .05       0
  4984.6     .12       0  5117.4     .05       0
Bank Sta=4975.3,4979.3
XS Rating Curve= 0 ,0
Exp/Cntr=0.3,0.1

Type RM Length L Ch R = 1 ,2634    ,323,323,323
BEGIN DESCRIPTION:
Moorehead Branch 7.0
END DESCRIPTION:
XS GIS Cut Line= 3
       2402885.4      7031138.06        2403079.        7031010.
      2403224.08      7030885.81
#Sta/Elev= 30
  4772.1  572.99  4831.2  570.06  4886.9  564.91  4932.3   561.4  4954.6  561.39
  4960.6  560.56  4975.6  551.06  4981.6  553.26  4990.7  550.67  4996.7   553.2
  5001.2   549.6  5017.9  549.43  5023.6  547.49  5023.9  546.99  5027.6  547.49
  5032.2  547.62  5039.9  553.01  5054.2  558.98  5060.8  561.08  5082.7  565.47
  5089.3  571.15  5096.4  571.79  5103.6  570.99  5110.1  574.82  5117.8  571.59
  5124.4  572.02  5132.1  571.16  5157.2  574.48  5167.2  576.87  5195.2  577.49
#Mann= 5 ,-1 , 0
  4772.1     .05       0  4886.9     .12       0  5023.6     .07       0
  5027.6     .12       0  5157.2    .075       0
Bank Sta=5023.6,5027.6
XS Rating Curve= 0 ,0
Exp/Cntr=0.3,0.1

Type RM Length L Ch R = 1 ,2311    ,337,337,337
BEGIN DESCRIPTION:
Moorehead Branch 6.0
END DESCRIPTION:
XS GIS Cut Line= 3
      2402988.19      7031338.97      2403249.91      7031243.17
      2403309.38       7031183.7
#Sta/Elev= 30
  4751.7  567.74  4765.9  567.98  4773.9  565.62  4791.1  564.77  4796.4  565.44
  4877.3  558.81  4901.6  558.49  4922.9  555.26  4938.4  554.61  4944.2  555.69
  4954.9  555.88  4963.5  554.53  4968.9  552.17  4976.2  550.85  4992.1  545.11
  4992.3  544.61  4996.1  545.11  5008.1  548.84  5024.6  558.56  5027.7  562.12
  5039.1  562.69  5046.1  564.79  5053.2  564.39  5060.3  565.77  5067.4  565.15
  5074.4  566.02  5081.5   565.7  5088.6  566.98  5109.8  568.13  5114.5  569.53
#Mann= 3 ,-1 , 0
  4751.7     .12       0  4992.1     .07       0  4996.1     .12       0
Bank Sta=4992.1,4996.1
XS Rating Curve= 0 ,0
Exp/Cntr=0.3,0.1