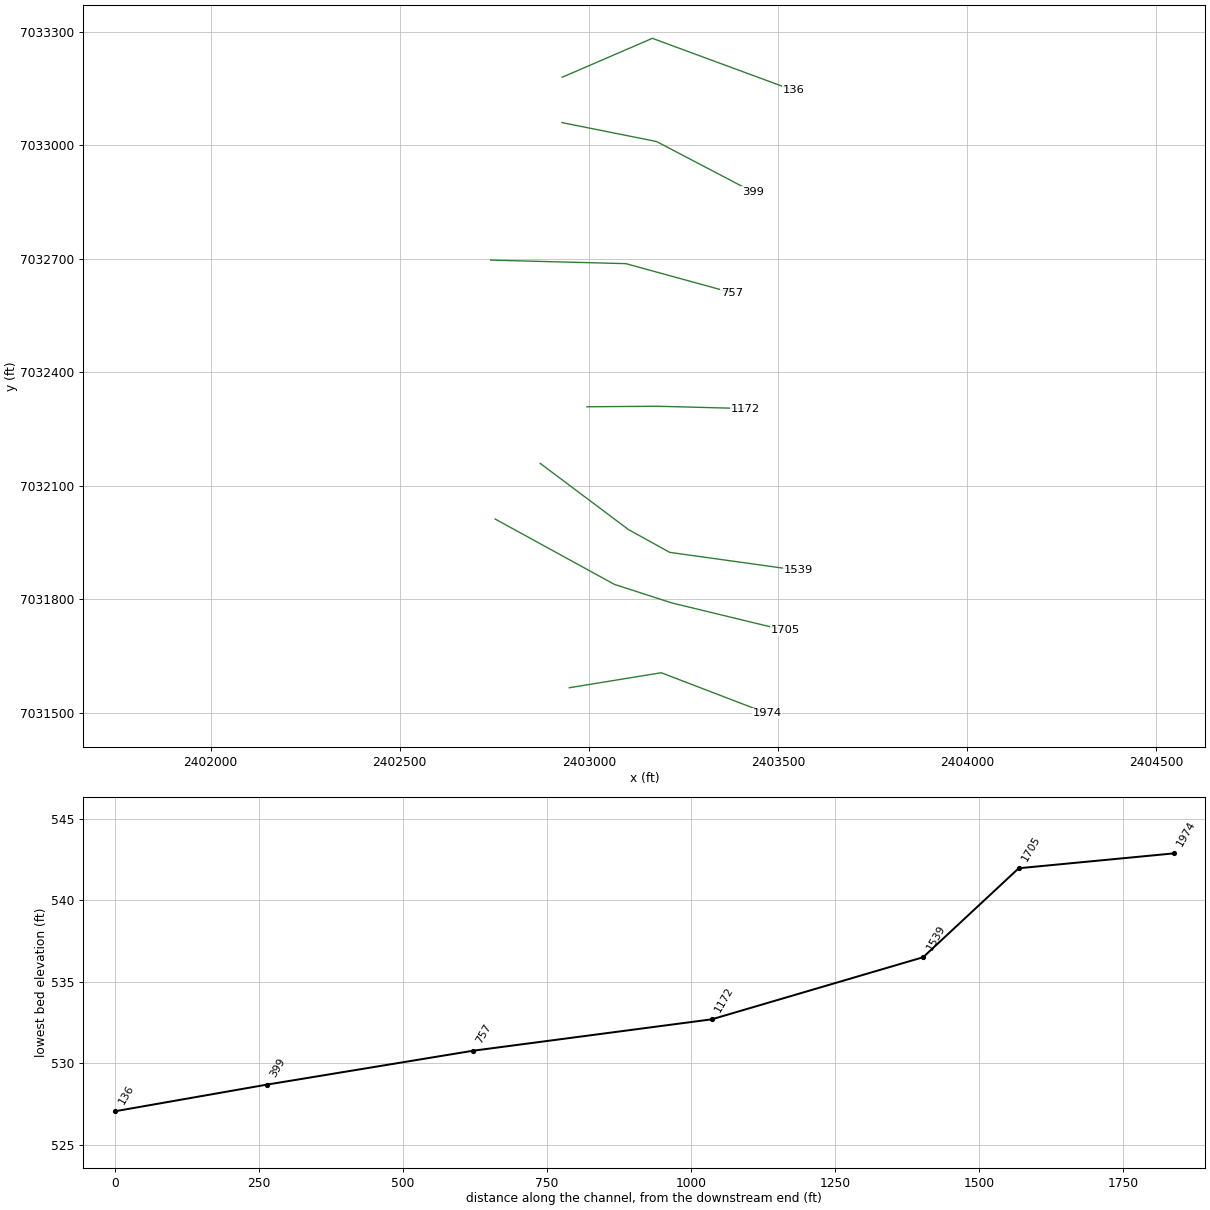
HEC-RAS study Moorehead Branch.prj: Moorehead Branch Base Level Engineering

--- Moorehead Branch.g01 (geometry) --- (continued)

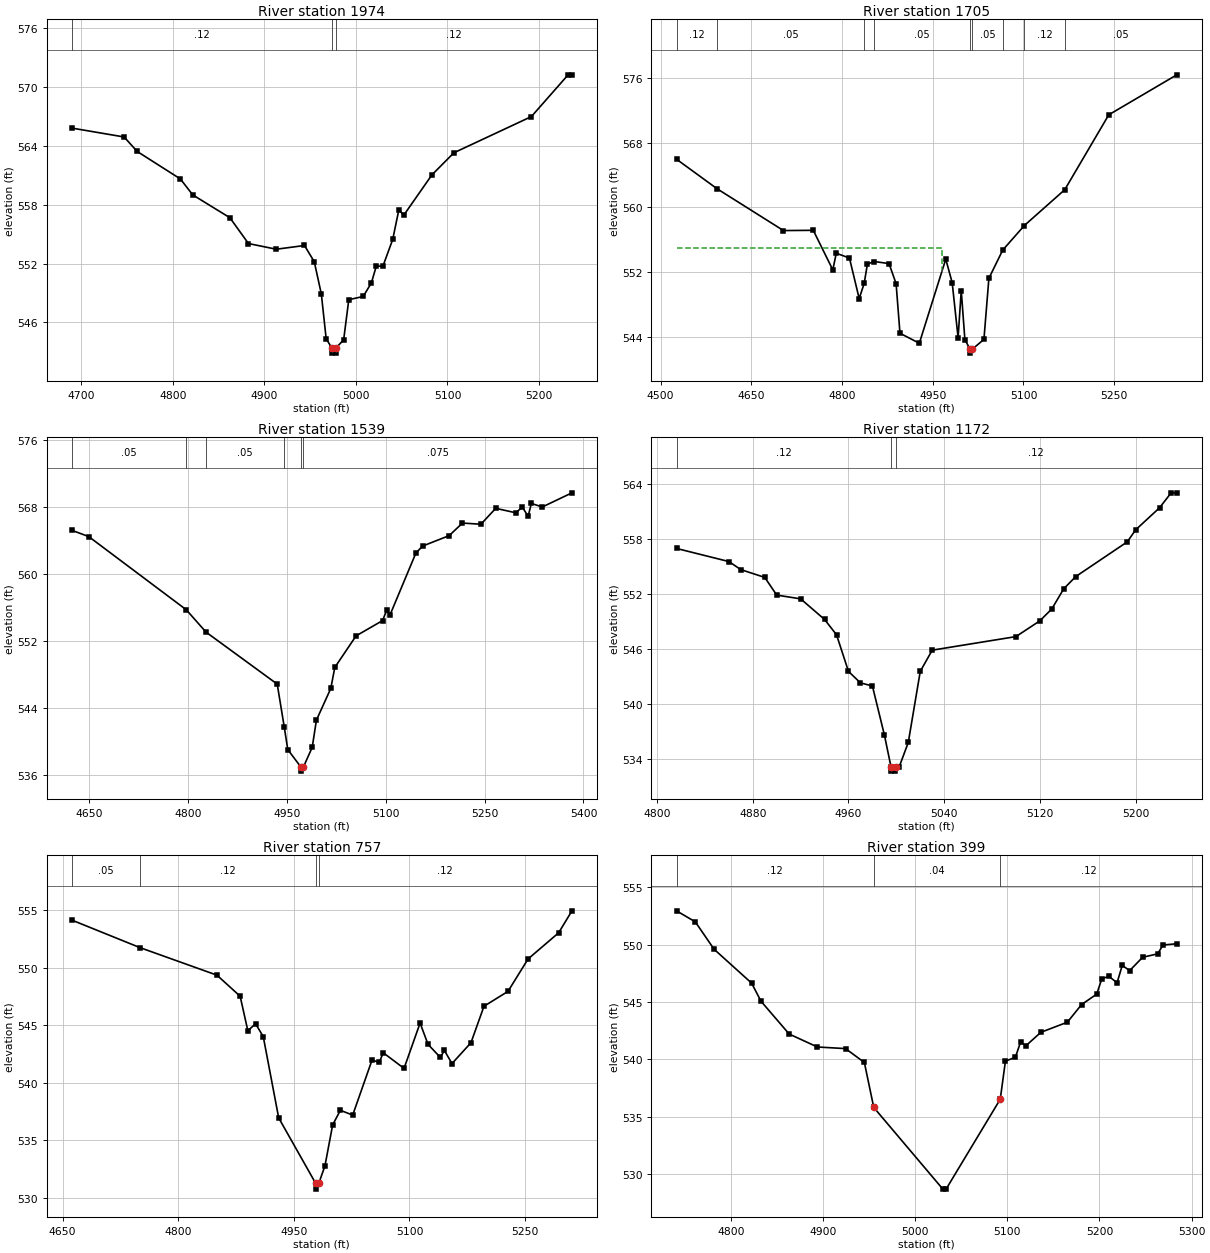
Type RM Length L Ch R = 1 ,1974    ,269,269,269
BEGIN DESCRIPTION:
Moorehead Branch 5.0
END DESCRIPTION:
XS GIS Cut Line= 3
      2402948.47      7031565.58       2403191.5       7031605.3
      2403471.85      7031497.83
#Sta/Elev= 30
  4689.5   565.8  4746.8  564.89    4761  563.42  4808.2  560.62  4821.8  558.99
  4862.3  556.67  4882.6  554.04    4913  553.46  4943.8  553.84  4954.5  552.19
  4962.2  548.91  4967.5  544.34  4973.9  543.38  4974.2  542.88  4977.7  542.88
  4977.9  543.38  4986.6  544.23  4992.2  548.32    5008  548.65  5016.9  550.04
  5022.3  551.75  5029.5  551.73  5040.2  554.46  5046.9  557.48  5052.3  556.93
    5083  561.03    5107  563.28  5191.7  566.97  5231.8  571.22    5236  571.22
#Mann= 3 ,-1 , 0
  4689.5     .12       0  4973.9     .07       0  4977.9     .12       0
Bank Sta=4973.9,4977.9
XS Rating Curve= 0 ,0
Exp/Cntr=0.3,0.1

Type RM Length L Ch R = 1 ,1705    ,166,166,166
BEGIN DESCRIPTION:
Moorehead Branch 4.2
END DESCRIPTION:
XS GIS Cut Line= 4
      2402752.27      7032011.82      2403067.67      7031838.94
      2403219.53      7031789.87      2403518.61      7031717.44
#Sta/Elev= 30
  4526.4  565.94  4593.4  562.29  4703.2  557.12  4752.5  557.15  4784.8  552.26
  4790.5  554.32  4812.3  553.72  4828.4  548.71  4836.6  550.58    4842  552.99
  4853.5  553.29  4877.7  553.04  4889.4  550.56  4895.8  544.43  4927.8  543.19
  4971.5  553.59  4982.1  550.69  4991.9  543.87  4997.1  549.71  5003.1  543.64
  5011.6  542.47  5011.8  541.97  5015.6  542.47  5034.6  543.67  5042.8  551.22
  5065.7  554.71  5101.4  557.74  5168.2  562.17    5241  571.43  5353.4  576.37
#Mann= 9 ,-1 , 0
  4526.4     .12       0  4593.4     .05       0  4836.6     .12       0
  4853.5     .05       0  5011.6     .05       0  5015.6     .05       0
  5065.7    .075       0  5101.4     .12       0  5168.2     .05       0
#XS Ineff= 2 , 0
       0    4965     555               0
Permanent Ineff=
       F       F
Bank Sta=5011.6,5015.6
XS Rating Curve= 0 ,0
Exp/Cntr=0.3,0.1

Type RM Length L Ch R = 1 ,1539    ,367,367,367
BEGIN DESCRIPTION:
Moorehead Branch 4.0
END DESCRIPTION:
XS GIS Cut Line= 4
      2402871.42      7032159.02      2403105.05      7031983.79
      2403213.89      7031923.63      2403553.61      7031876.32
#Sta/Elev= 30
  4623.1  565.27  4648.9  564.52    4797  555.78    4827  553.11  4935.1   546.9
  4945.9  541.72  4951.1  539.09  4970.9  537.01  4971.1  536.51  4974.9  537.01
  4988.2  539.35  4994.6   542.6  5016.4  546.38  5022.5  548.89  5054.8  552.66
  5095.1  554.49  5101.1  555.71  5106.2  555.14  5145.6  562.55  5155.7  563.38
  5196.1  564.63  5216.3  566.13  5244.3  565.99  5266.8  567.89  5297.1  567.36
  5307.2  568.03  5315.9  566.94  5320.9  568.47  5337.5  568.05  5382.5  569.74
#Mann= 6 ,-1 , 0
  4623.1     .05       0    4797    .075       0    4827     .05       0
  4945.9    .075       0  4970.9     .07       0  4974.9    .075       0
Bank Sta=4970.9,4974.9
XS Rating Curve= 0 ,0
Exp/Cntr=0.3,0.1

Type RM Length L Ch R = 1 ,1172    ,415,415,415
BEGIN DESCRIPTION:
Moorehead Branch 3.0
END DESCRIPTION:
XS GIS Cut Line= 3
      2402995.21      7032308.54        2403179.        7032310.
      2403413.43      7032303.87
#Sta/Elev= 30
  4816.2     557    4860  555.57    4870  554.69    4890  553.84    4900  551.91
    4920   551.5    4940  549.25    4950  547.58    4960  543.58    4970  542.33
    4980  541.99    4990  536.66  4995.5   533.2  4995.7   532.7  4999.2   532.7
  4999.5   533.2  5002.5   533.2    5010  535.83    5020  543.58    5030   545.9
    5100  547.38    5120   549.1    5130   550.4    5140   552.6    5150  553.93
  5193.1  557.72  5200.1  559.03  5220.1  561.44  5229.8  563.07  5234.5  563.07
#Mann= 3 ,-1 , 0
  4816.2     .12       0  4995.5     .07       0  4999.5     .12       0
Bank Sta=4995.5,4999.5
XS Rating Curve= 0 ,0
Exp/Cntr=0.3,0.1

Type RM Length L Ch R = 1 ,757     ,358,358,358
BEGIN DESCRIPTION:
Moorehead Branch 2.0
END DESCRIPTION:
XS GIS Cut Line= 3
      2402740.62      7032696.37      2403098.04      7032687.03
      2403379.03      7032609.99
#Sta/Elev= 30
  4661.9  554.15  4750.6  551.75  4850.3  549.36  4880.4  547.53  4890.4  544.53
  4900.4  545.14  4910.4  544.02  4930.4  536.96  4978.4  531.27  4978.6  530.77
  4982.4  531.27  4990.4  532.79  5000.4  536.35  5010.4  537.62  5026.4   537.2
  5051.5  541.99  5060.8  541.78    5066  542.62    5093  541.26  5113.8   545.2
  5124.1  543.35  5140.1  542.21  5145.3  542.82  5155.2  541.68  5179.8  543.49
  5196.7  546.66  5227.8  547.95  5253.9  550.77  5293.5  553.04  5310.8  554.95
#Mann= 4 ,-1 , 0
  4661.9     .05       0  4750.6     .12       0  4978.4     .07       0
  4982.4     .12       0
Bank Sta=4978.4,4982.4
XS Rating Curve= 0 ,0
Exp/Cntr=0.3,0.1

Type RM Length L Ch R = 1 ,399     ,263,263,263
BEGIN DESCRIPTION:
Moorehead Branch 1.0
END DESCRIPTION:
XS GIS Cut Line= 3
      2402929.04      7033059.99        2403179.        7033010.
      2403434.23       7032876.4
#Sta/Elev= 30
  4740.9  552.95  4761.3  551.99  4781.7   549.6  4822.4  546.65  4832.6  545.07
  4863.2  542.21  4893.8  541.08  4924.4  540.94  4944.8  539.73    4955  535.81
    5030  528.69  5033.5  528.69  5092.3  536.53  5097.9  539.85  5108.7  540.18
  5114.4  541.52    5120  541.18  5136.4  542.36  5165.1  543.24  5180.6  544.78
    5197  545.69  5202.6  547.04  5210.3  547.23  5219.1  546.68  5224.7  548.19
  5232.8  547.74  5246.8   548.9  5263.2   549.2  5268.9  549.97  5283.9  550.08
#Mann= 3 ,-1 , 0
  4740.9     .12       0    4955     .04       0  5092.3     .12       0
Bank Sta=4955,5092.3
XS Rating Curve= 0 ,0
Exp/Cntr=0.3,0.1

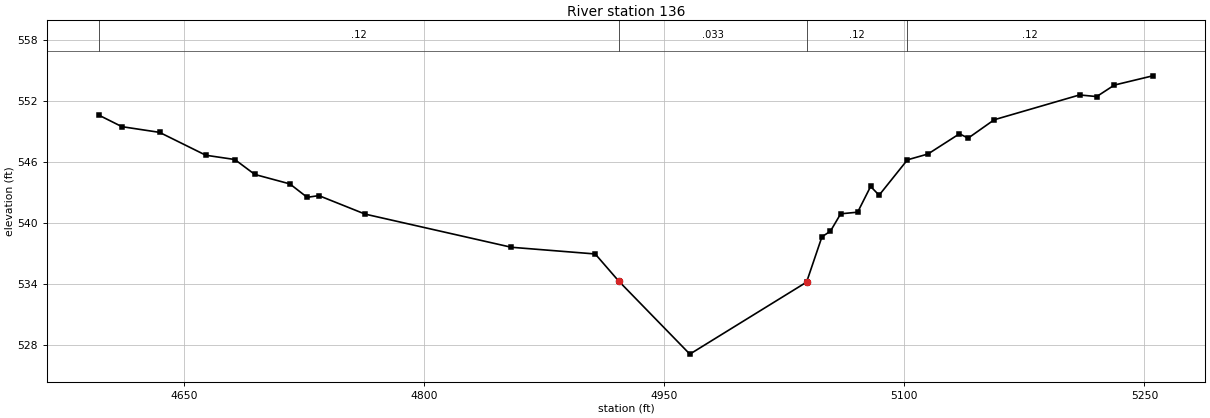
Type RM Length L Ch R = 1 ,136     ,0,0,0
BEGIN DESCRIPTION:
Moorehead Branch 0.5
END DESCRIPTION:
XS GIS Cut Line= 3
      2402929.81      7033179.99      2403168.13      7033282.79
      2403541.88      7033144.98
#Sta/Elev= 30
  4597.3  550.54  4611.4  549.43  4634.9  548.87  4663.8  546.62  4681.9   546.2
  4694.4  544.73  4716.3   543.8  4727.1  542.48  4734.4  542.65  4763.3  540.83
  4854.6  537.57    4907  536.91  4921.7  534.24  4966.1  527.06    5039  534.14
  5048.6   538.6  5053.9  539.15  5060.3  540.86  5070.9  541.02    5079  543.55
  5084.3  542.69    5102  546.17  5114.8  546.74  5134.5  548.73  5139.9   548.3
  5156.2  550.11  5209.5  552.55  5220.2  552.39  5231.2  553.52  5255.2  554.43
#Mann= 4 ,-1 , 0
  4597.3     .12       0  4921.7    .033       0    5039     .12       0
    5102     .12       0
Bank Sta=4921.7,5039
XS Rating Curve= 0 ,0
Exp/Cntr=0.3,0.1

Chan Stop Cuts=-1
Use User Specified Reach Order=0
Composite Channel Slope=5