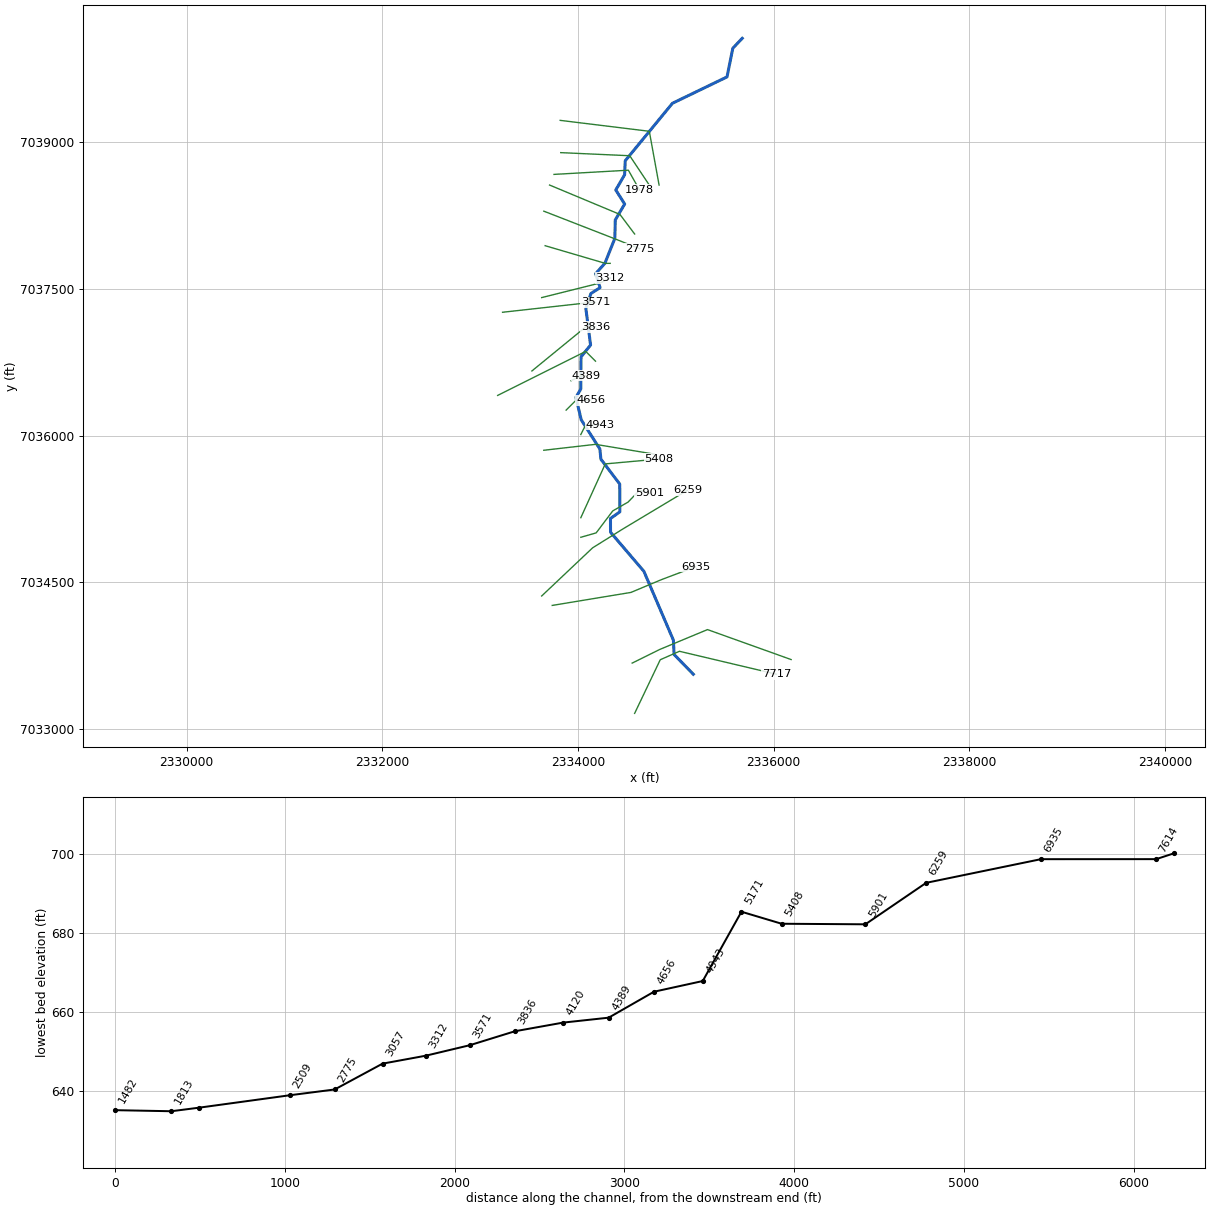
--- Old Buffalo Creek.prj (project) ---

Proj Title=Old Buffalo Creek Base Level Engineering
Current Plan=p01
Default Exp/Contr=0.3,0.1
English Units
Geom File=g01
Flow File=f01
Plan File=p01
BEGIN DESCRIPTION:
Old Buffalo Creek
END DESCRIPTION:

--- Old Buffalo Creek.p01 (plan) ---

Plan Title=Multiple Run
Short Identifier=Multiple
Geom File=g01
Flow File=f01
Subcritical Flow
K Sum by GR= 0
Std Step Tol= 0.01
Critical Tol= 0.01
Num of Std Step Trials= 20
Max Error Tol= 0.3
Flow Tol Ratio= 0.001
Split Flow NTrial= 30
Split Flow Tol= 0.02
Split Flow Ratio= 0.02
Log Output Level= 0
Friction Slope Method= 1
Unsteady Friction Slope Method= 2
Unsteady Bridges Friction Slope Method= 1
Parabolic Critical Depth
Global Vel Dist=  1 , 1 , 1
Global Log Level= 0
CheckData=True
Encroach Param= -1, 0, 0, 0
BEGIN DESCRIPTION:
Multiple Run
END DESCRIPTION:

--- Old Buffalo Creek.f01 (steady flow) ---

Flow Title=Multiple
Number of Profiles=7
Profile Names=10-year,25-year,50-year,1pct_min,100-year,1pct_plu,500-year
River Rch & RM= Old Buffalo Cree,Reach-1,7717
     273     353     416     244     486     970     663
River Rch & RM= Old Buffalo Cree,Reach-1,6935
     353     465     555     329     657    1310     917
River Rch & RM= Old Buffalo Cree,Reach-1,4943
     405     539     646     385     769    1530    1090
River Rch & RM= Old Buffalo Cree,Reach-1,1978
     585     797     971     587    1170    2340    1700
Boundary for River Rch & Prof#=Old Buffalo Cree,Reach-1,1
Up Type=0
Dn Type=3
Dn Slope=0.005
Boundary for River Rch & Prof#=Old Buffalo Cree,Reach-1,2
Up Type=0
Dn Type=3
Dn Slope=0.005
Boundary for River Rch & Prof#=Old Buffalo Cree,Reach-1,3
Up Type=0
Dn Type=3
Dn Slope=0.005
Boundary for River Rch & Prof#=Old Buffalo Cree,Reach-1,4
Up Type=0
Dn Type=3
Dn Slope=0.005
Boundary for River Rch & Prof#=Old Buffalo Cree,Reach-1,5
Up Type=0
Dn Type=3
Dn Slope=0.005
Boundary for River Rch & Prof#=Old Buffalo Cree,Reach-1,6
Up Type=0
Dn Type=3
Dn Slope=0.005
Boundary for River Rch & Prof#=Old Buffalo Cree,Reach-1,7
Up Type=0
Dn Type=3
Dn Slope=0.005

--- Old Buffalo Creek.g01 (geometry) ---

Geom Title=Existing Conditions

River Reach=Old Buffalo Cree,Reach-1
Reach XY= 30
      2335179.00      7033560.00      2334982.54      7033761.47
      2334975.24      7033908.44      2334673.48      7034612.43
      2334332.73      7035011.53      2334332.09      7035151.68
      2334427.99      7035220.29      2334426.76      7035504.07
      2334234.52      7035757.57      2334223.46      7035862.42
      2334032.76      7036161.56      2333978.72      7036389.82
      2334028.46      7036475.21      2334031.07      7036804.14
      2334128.75      7036925.22      2334080.22      7037299.50
      2334132.19      7037451.65      2334225.93      7037511.43
      2334180.63      7037653.96      2334275.38      7037761.50
      2334376.76      7038015.93      2334381.24      7038204.07
      2334477.24      7038366.13      2334386.30      7038509.92
      2334476.75      7038665.93      2334482.76      7038808.44
      2334965.78      7039396.38      2335523.41      7039665.61
      2335582.48      7039958.56      2335679.00      7040060.00

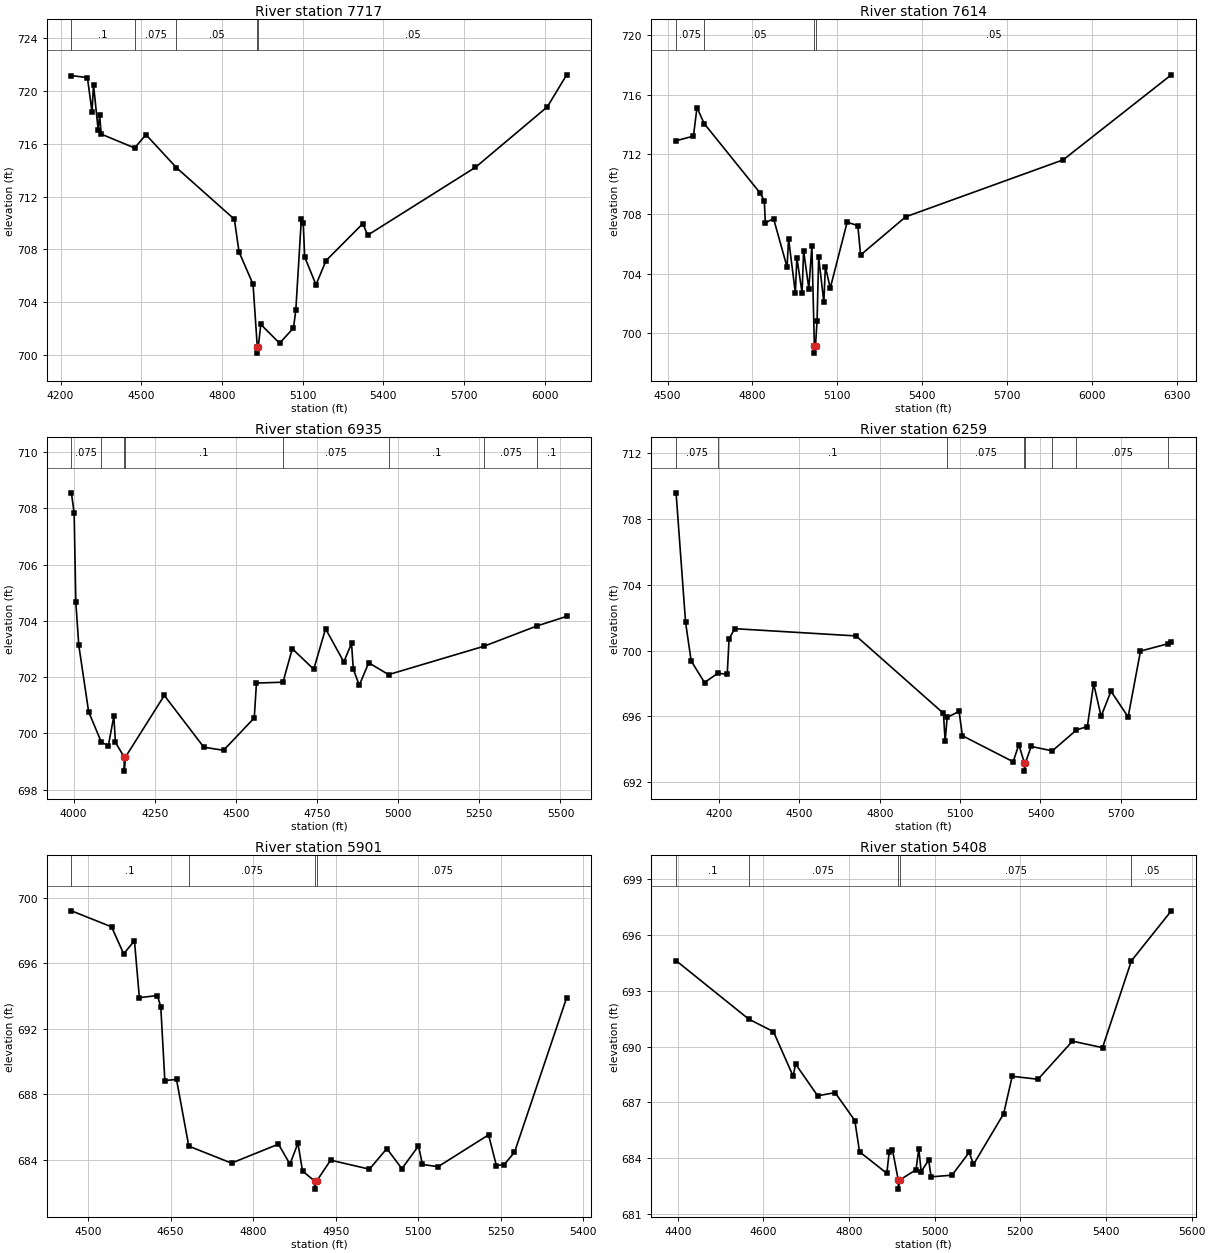
Type RM Length L Ch R = 1,7717,103,103,103
BEGIN DESCRIPTION:
Old Buffalo Creek 21.0
END DESCRIPTION:
XS GIS Cut Line= 4
      2334579.01      7033160.02      2334840.94      7033708.24
      2335037.11      7033794.68      2336028.98      7033560.01
#Sta/Elev= 30
  4240.2  721.18  4299.6  721.03  4316.8  718.43  4322.3  720.50  4339.5  717.07
  4345.0  718.17  4351.0  716.74  4475.2  715.69  4517.2  716.70  4630.8  714.19
  4846.0  710.28  4863.3  707.80  4915.4  705.35  4931.1  700.62  4931.3  700.12
  4935.1  700.62  4944.2  702.30  5014.2  700.87  5065.7  702.03  5074.4  703.38
  5094.9  710.28  5102.1  709.97  5107.3  707.42  5149.5  705.31  5186.7  707.14
  5323.7  709.95  5341.5  709.07  5742.3  714.22  6009.5  718.81  6081.4  721.24
#Mann=5,-1,0
  4240.2     0.1       0  4475.2   0.075       0  4630.8    0.05       0
  4931.1    0.04       0  4935.1    0.05       0
Bank Sta=4931.1,4935.1
Exp/Cntr=0.3,0.1

Type RM Length L Ch R = 1,7614,679,679,679
BEGIN DESCRIPTION:
Old Buffalo Creek 20.0
END DESCRIPTION:
XS GIS Cut Line= 4
      2334554.00      7033673.97      2334833.79      7033812.49
      2335323.83      7034016.43      2336179.00      7033710.00
#Sta/Elev= 30
  4530.1  712.91  4591.5  713.22  4604.1  715.13  4629.6  714.06  4828.4  709.38
  4842.3  708.87  4845.7  707.40  4874.9  707.69  4922.6  704.44  4928.0  706.34
  4951.9  702.71  4957.3  705.07  4975.7  702.71  4981.2  705.52  4999.6  703.00
  5010.4  705.87  5019.2  699.17  5019.5  698.67  5023.2  699.17  5028.8  700.85
  5034.3  705.09  5052.7  702.10  5058.1  704.46  5075.4  703.03  5135.1  707.45
  5172.9  707.22  5182.7  705.25  5342.1  707.81  5899.1  711.63  6281.5  717.33
#Mann=4,-1,0
  4530.1   0.075       0  4629.6    0.05       0  5019.2   0.033       0
  5023.2    0.05       0
Bank Sta=5019.2,5023.2
Exp/Cntr=0.3,0.1

Type RM Length L Ch R = 1,6935,676,676,676
BEGIN DESCRIPTION:
Old Buffalo Creek 18.0
END DESCRIPTION:
XS GIS Cut Line= 4
      2333736.69      7034263.46      2334541.70      7034396.48
      2334850.91      7034526.15      2335200.95      7034658.64
#Sta/Elev= 30
  3993.6  708.55  4002.0  707.82  4007.1  704.66  4016.2  703.14  4046.6  700.77
  4086.0  699.68  4107.4  699.57  4124.2  700.61  4129.2  699.68  4156.1  699.16
  4156.4  698.66  4160.1  699.16  4279.7  701.35  4401.4  699.51  4462.2  699.40
  4556.8  700.55  4563.5  701.79  4645.3  701.82  4673.9  703.01  4740.0  702.28
  4776.4  703.72  4832.6  702.54  4856.4  703.20  4861.8  702.29  4880.2  701.71
  4909.4  702.51  4970.6  702.09  5264.8  703.10  5427.7  703.82  5519.1  704.16
#Mann=8,-1,0
  3993.6   0.075       0  4086.0     0.1       0  4156.1    0.07       0
  4160.1     0.1       0  4645.3   0.075       0  4970.6     0.1       0
  5264.8   0.075       0  5427.7     0.1       0
Bank Sta=4156.1,4160.1
Exp/Cntr=0.3,0.1

Type RM Length L Ch R = 1,6259,358,358,358
BEGIN DESCRIPTION:
Old Buffalo Creek 17.0
END DESCRIPTION:
XS GIS Cut Line= 4
      2333629.01      7034360.01      2334149.37      7034851.98
      2334458.58      7035044.82      2335117.74      7035440.65
#Sta/Elev= 30
  4039.2  709.58  4074.6  701.73  4095.6  699.37  4145.4  698.06  4194.8  698.62
  4230.3  698.57  4237.2  700.72  4258.6  701.33  4711.3  700.89  5037.7  696.19
  5044.0  694.48  5051.5  695.94  5096.0  696.31  5108.4  694.83  5298.0  693.25
  5319.3  694.29  5339.8  693.18  5340.1  692.68  5343.8  693.18  5365.2  694.18
  5444.2  693.91  5534.5  695.18  5575.1  695.39  5598.5  697.99  5626.4  696.01
  5663.3  697.53  5727.4  695.97  5773.4  699.97  5877.4  700.42  5888.6  700.53
#Mann=8,-1,0
  4039.2   0.075       0  4194.8     0.1       0  5051.5   0.075       0
  5339.8    0.07       0  5343.8   0.075       0  5444.2     0.1       0
  5534.5   0.075       0  5877.4    0.05       0
Bank Sta=5339.8,5343.8
Exp/Cntr=0.3,0.1

Type RM Length L Ch R = 1,5901,493,493,493
BEGIN DESCRIPTION:
Old Buffalo Creek 16.0
END DESCRIPTION:
XS GIS Cut Line= 6
      2334028.95      7034959.99      2334185.95      7035004.93
      2334355.45      7035229.64      2334510.92      7035318.96
      2334631.09      7035442.64      2334728.97      7035410.01
#Sta/Elev= 30
  4470.0  699.22  4542.9  698.24  4564.9  696.59  4584.5  697.39  4593.4  693.91
  4626.1  694.04  4632.3  693.36  4639.7  688.84  4660.9  688.91  4683.2  684.83
  4760.8  683.79  4846.1  684.95  4867.0  683.73  4881.5  685.01  4889.8  683.31
  4911.6  682.70  4911.8  682.20  4915.6  682.70  4940.9  683.97  5011.4  683.42
  5043.0  684.68  5070.3  683.45  5100.5  684.84  5107.7  683.71  5136.0  683.57
  5227.8  685.52  5242.0  683.64  5256.1  683.70  5274.9  684.45  5369.7  693.91
#Mann=4,-1,0
  4470.0     0.1       0  4683.2   0.075       0  4911.6    0.07       0
  4915.6   0.075       0
Bank Sta=4911.6,4915.6
Exp/Cntr=0.3,0.1

Type RM Length L Ch R = 1,5408,237,237,237
BEGIN DESCRIPTION:
Old Buffalo Creek 15.0
END DESCRIPTION:
XS GIS Cut Line= 3
      2334029.00      7035159.99      2334279.00      7035710.00
      2334828.97      7035760.00
#Sta/Elev= 30
  4396.1  694.63  4565.5  691.49  4623.5  690.81  4669.6  688.41  4675.1  689.07
  4726.7  687.36  4767.4  687.53  4813.5  686.03  4824.5  684.35  4888.2  683.19
  4893.7  684.32  4901.4  684.45  4914.8  682.84  4915.0  682.34  4918.8  682.84
  4956.3  683.38  4962.9  684.51  4968.4  683.28  4986.0  683.91  4991.5  683.00
  5040.4  683.09  5080.6  684.32  5090.6  683.67  5160.9  686.39  5181.0  688.41
  5241.3  688.25  5321.6  690.30  5391.9  689.95  5459.3  694.62  5552.5  697.31
#Mann=5,-1,0
  4396.1     0.1       0  4565.5   0.075       0  4914.8    0.07       0
  4918.8   0.075       0  5459.3    0.05       0
Bank Sta=4914.8,4918.8
Exp/Cntr=0.3,0.1

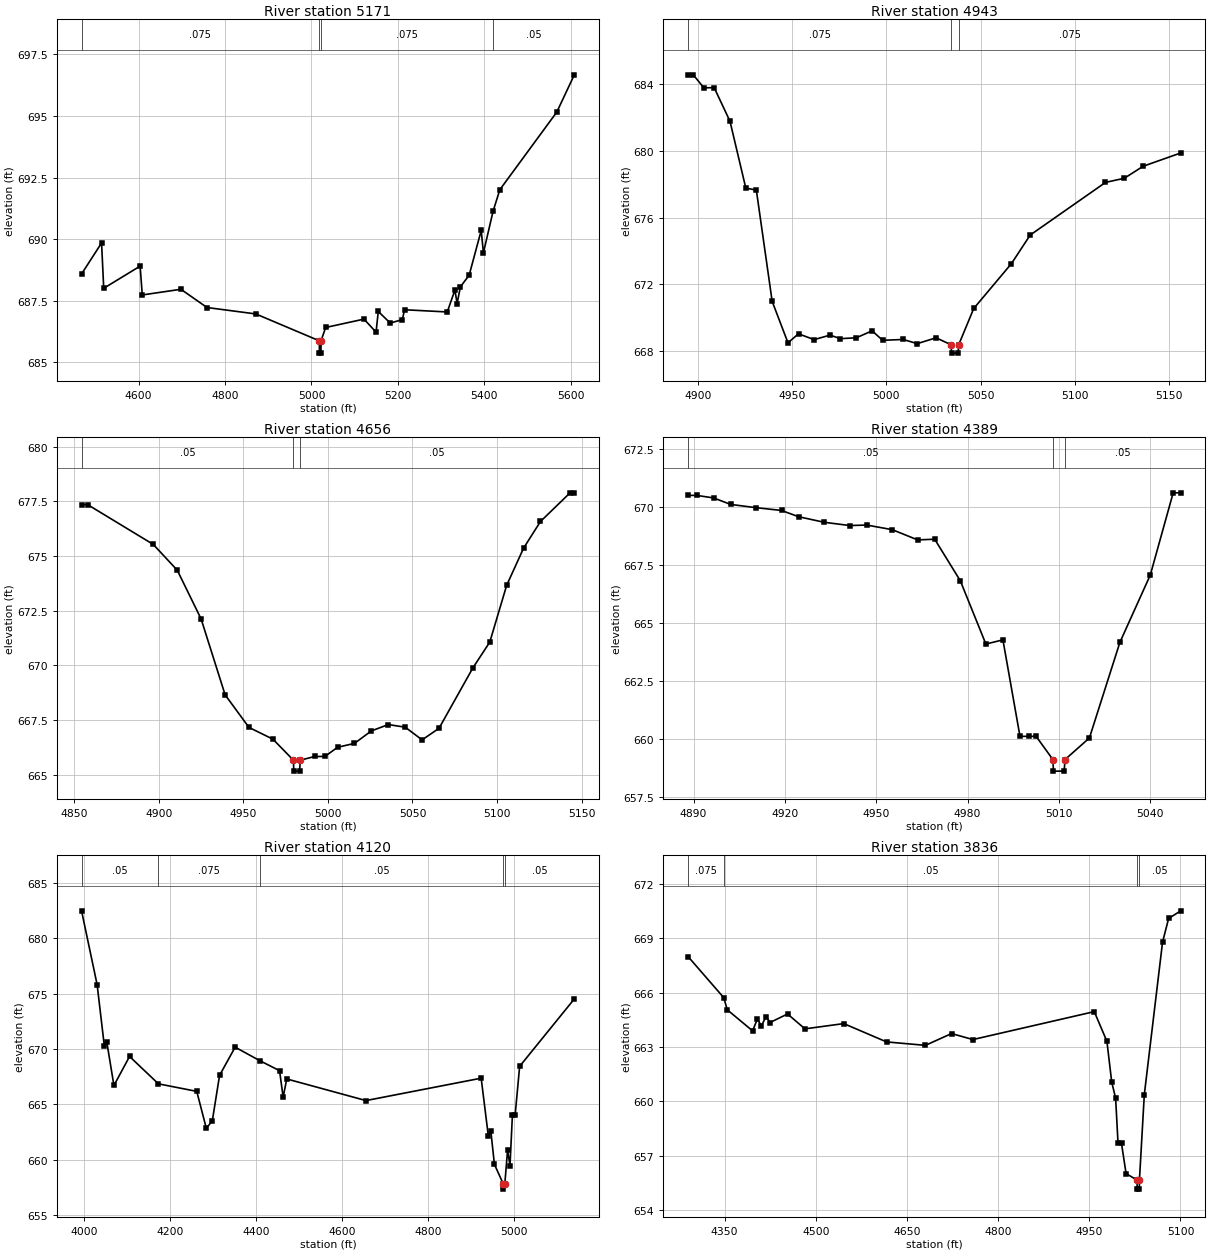
Type RM Length L Ch R = 1,5171,228,228,228
BEGIN DESCRIPTION:
Old Buffalo Creek 14.0
END DESCRIPTION:
XS GIS Cut Line= 3
      2333650.60      7035849.43      2334179.00      7035910.00
      2334778.96      7035810.01
#Sta/Elev= 30
  4468.1  688.59  4514.4  689.85  4519.4  688.01  4603.6  688.91  4608.6  687.74
  4698.0  687.97  4758.4  687.23  4871.2  686.97  5018.2  685.88  5018.5  685.38
  5022.0  685.38  5022.2  685.88  5032.9  686.42  5121.6  686.76  5149.5  686.23
  5154.6  687.07  5182.4  686.60  5210.3  686.74  5215.4  687.14  5314.2  687.05
  5332.0  687.94  5337.0  687.39  5344.6  688.07  5364.9  688.54  5392.8  690.36
  5397.9  689.45  5420.3  691.14  5435.9  692.01  5567.7  695.16  5608.2  696.67
#Mann=4,-1,0
  4468.1   0.075       0  5018.2    0.07       0  5022.2   0.075       0
  5420.3    0.05       0
Bank Sta=5018.2,5022.2
Exp/Cntr=0.3,0.1

Type RM Length L Ch R = 1,4943,287,287,287
BEGIN DESCRIPTION:
Old Buffalo Creek 13.0
END DESCRIPTION:
XS GIS Cut Line= 3
      2334029.02      7036010.03      2334079.00      7036110.00
      2334229.03      7036110.00
#Sta/Elev= 30
  4894.6  684.57  4897.4  684.57  4903.0  683.79  4908.5  683.80  4916.9  681.78
  4925.3  677.77  4930.9  677.65  4939.3  670.97  4947.7  668.48  4953.3  669.02
  4961.6  668.67  4970.0  668.94  4975.6  668.73  4984.0  668.78  4992.4  669.20
  4998.0  668.63  5008.9  668.68  5016.4  668.43  5026.4  668.78  5034.4  668.36
  5034.6  667.86  5038.1  667.86  5038.4  668.36  5046.4  670.54  5066.4  673.23
  5076.4  674.95  5116.4  678.11  5126.4  678.36  5136.4  679.08  5156.4  679.88
#Mann=3,-1,0
  4894.6   0.075       0  5034.4    0.07       0  5038.4   0.075       0
Bank Sta=5034.4,5038.4
Exp/Cntr=0.3,0.1

Type RM Length L Ch R = 1,4656,267,267,267
BEGIN DESCRIPTION:
Old Buffalo Creek 12.0
END DESCRIPTION:
XS GIS Cut Line= 3
      2333878.99      7036259.99      2333979.00      7036360.00
      2334128.96      7036360.00
#Sta/Elev= 28
  4854.3  677.35  4857.9  677.35  4896.7  675.53  4910.9  674.35  4925.0  672.12
  4939.2  668.65  4953.3  667.16  4967.5  666.62  4979.6  665.66  4979.8  665.16
  4983.3  665.16  4983.6  665.66  4992.2  665.83  4998.2  665.83  5005.7  666.25
  5015.7  666.43  5025.7  667.00  5035.7  667.29  5045.7  667.17  5055.7  666.59
  5065.7  667.12  5085.7  669.88  5095.7  671.06  5105.7  673.66  5115.7  675.36
  5125.7  676.58  5143.2  677.89  5145.7  677.89
#Mann=3,-1,0
  4854.3    0.05       0  4979.6    0.04       0  4983.6    0.05       0
Bank Sta=4979.6,4983.6
Exp/Cntr=0.3,0.1

Type RM Length L Ch R = 1,4389,269,269,269
BEGIN DESCRIPTION:
Old Buffalo Creek 11.0
END DESCRIPTION:
XS GIS Cut Line= 3
      2333929.02      7036560.01      2334029.00      7036610.00
      2334079.02      7036610.00
#Sta/Elev= 28
  4888.2  670.49  4891.0  670.49  4896.6  670.38  4902.2  670.10  4910.5  669.96
  4918.9  669.84  4924.5  669.57  4932.9  669.33  4941.3  669.19  4946.9  669.21
  4955.3  669.01  4963.6  668.57  4969.2  668.60  4977.6  666.81  4986.0  664.08
  4991.6  664.26  4997.2  660.10  5000.0  660.10  5002.5  660.10  5008.0  659.10
  5008.2  658.60  5011.7  658.60  5012.0  659.10  5020.0  660.03  5030.0  664.15
  5040.0  667.06  5047.5  670.60  5050.0  670.60
#Mann=3,-1,0
  4888.2    0.05       0  5008.0   0.033       0  5012.0    0.05       0
Bank Sta=5008,5012
Exp/Cntr=0.3,0.1

Type RM Length L Ch R = 1,4120,284,284,284
BEGIN DESCRIPTION:
Old Buffalo Creek 10.0
END DESCRIPTION:
XS GIS Cut Line= 3
      2333179.04      7036410.02      2334079.00      7036860.00
      2334178.99      7036760.01
#Sta/Elev= 30
  3993.8  682.46  4030.1  675.79  4046.9  670.25  4052.5  670.64  4069.2  666.70
  4105.6  669.32  4172.8  666.85  4262.1  666.17  4284.4  662.83  4298.4  663.53
  4315.2  667.61  4351.5  670.16  4408.4  668.95  4454.9  668.04  4463.3  665.65
  4471.7  667.29  4656.2  665.34  4924.5  667.36  4941.3  662.10  4946.9  662.61
  4955.3  659.59  4975.6  657.85  4975.9  657.35  4979.6  657.85  4986.0  660.86
  4991.6  659.48  4997.2  664.00  5003.5  664.00  5014.1  668.43  5141.4  674.51
#Mann=5,-1,0
  3993.8    0.05       0  4172.8   0.075       0  4408.4    0.05       0
  4975.6   0.033       0  4979.6    0.05       0
Bank Sta=4975.6,4979.6
Exp/Cntr=0.3,0.1

Type RM Length L Ch R = 1,3836,265,265,265
BEGIN DESCRIPTION:
Old Buffalo Creek 9.0
END DESCRIPTION:
XS GIS Cut Line= 3
      2333529.01      7036660.01      2334079.00      7037110.00
      2334178.98      7037110.00
#Sta/Elev= 30
  4289.9  667.99  4348.7  665.72  4354.5  665.05  4396.1  663.89  4404.0  664.54
  4410.5  664.16  4418.4  664.68  4424.8  664.35  4453.6  664.82  4482.3  664.00
  4546.1  664.29  4616.5  663.28  4680.4  663.09  4723.4  663.74  4758.6  663.41
  4958.2  664.95  4979.0  663.31  4986.9  661.06  4993.3  660.18  4997.3  657.68
  5003.0  657.68  5010.5  656.02  5028.5  655.66  5028.8  655.16  5032.3  655.16
  5032.5  655.66  5040.5  660.37  5070.5  668.78  5080.5  670.09  5100.5  670.51
#Mann=4,-1,0
  4289.9   0.075       0  4348.7    0.05       0  5028.5   0.033       0
  5032.5    0.05       0
Bank Sta=5028.5,5032.5
Exp/Cntr=0.3,0.1

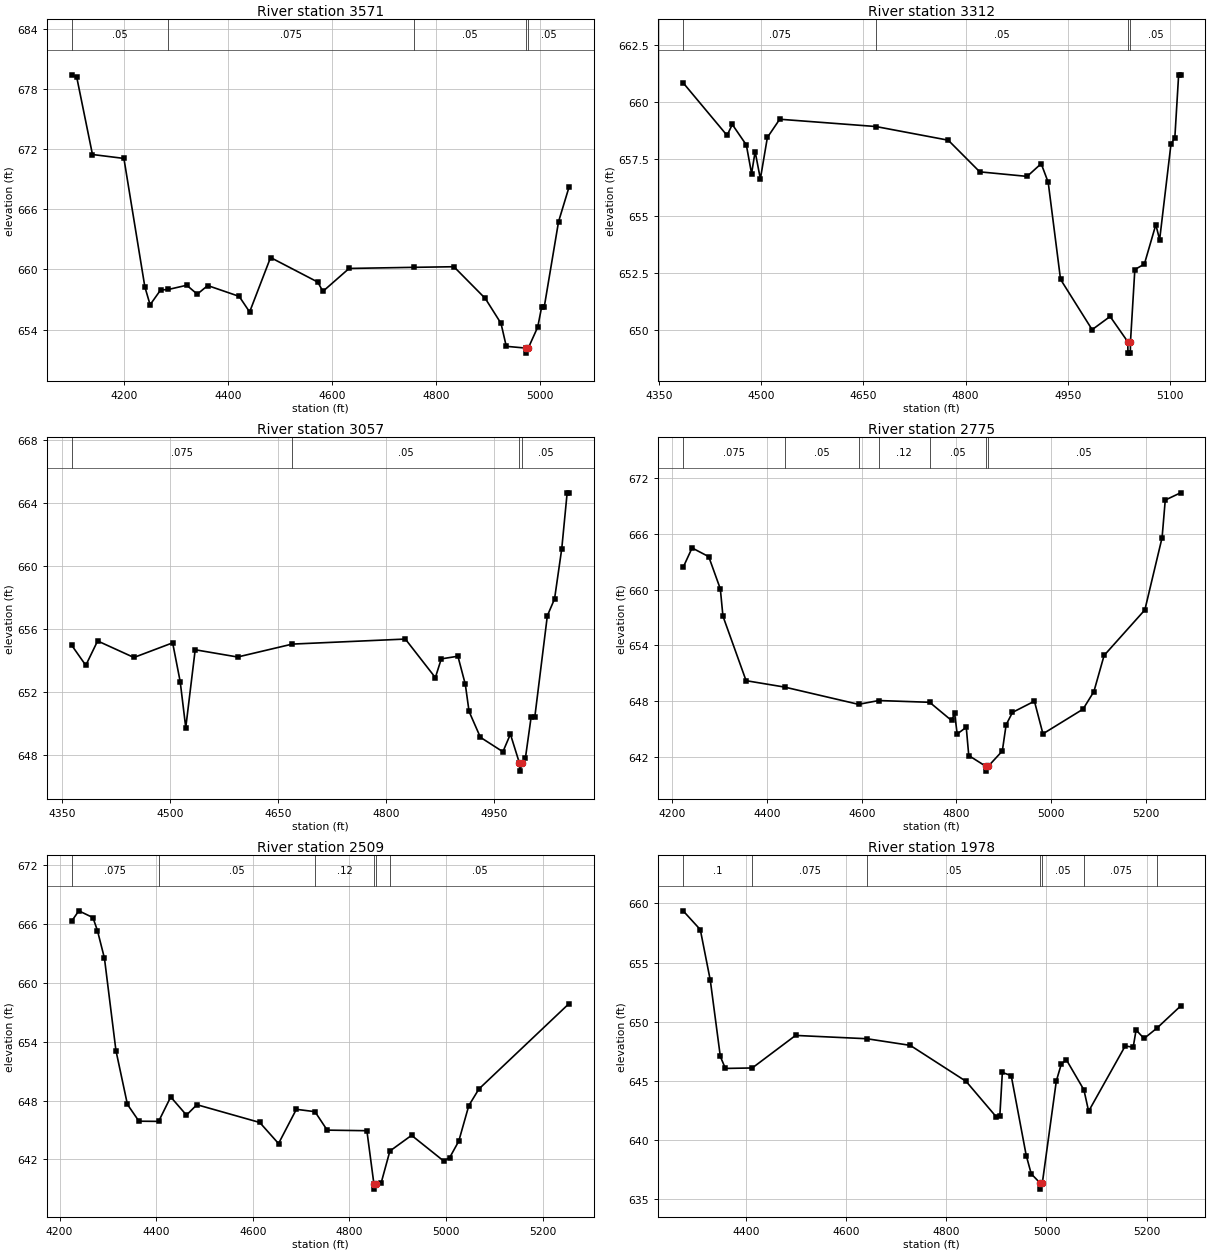
Type RM Length L Ch R = 1,3571,259,259,259
BEGIN DESCRIPTION:
Old Buffalo Creek 8.0
END DESCRIPTION:
XS GIS Cut Line= 3
      2333229.01      7037260.00      2334129.00      7037360.00
      2334178.98      7037360.00
#Sta/Elev= 30
  4099.5  679.44  4109.5  679.20  4139.7  671.48  4200.1  671.09  4240.3  658.27
  4250.4  656.47  4270.5  657.94  4285.5  658.00  4320.8  658.42  4341.0  657.53
  4361.1  658.39  4421.5  657.31  4441.6  655.75  4481.8  661.19  4572.4  658.74
  4582.4  657.81  4632.7  660.10  4756.6  660.21  4834.0  660.27  4894.3  657.10
  4924.5  654.61  4934.6  652.32  4972.8  652.14  4973.1  651.64  4976.8  652.14
  4995.0  654.24  5002.5  656.24  5007.5  656.24  5035.0  664.77  5055.0  668.20
#Mann=5,-1,0
  4099.5    0.05       0  4285.5   0.075       0  4756.6    0.05       0
  4972.8   0.033       0  4976.8    0.05       0
Bank Sta=4972.8,4976.8
Exp/Cntr=0.3,0.1

Type RM Length L Ch R = 1,3312,255,255,255
BEGIN DESCRIPTION:
Old Buffalo Creek 7.0
END DESCRIPTION:
XS GIS Cut Line= 3
      2333628.97      7037409.99      2334229.00      7037560.00
      2334329.00      7037610.00
#Sta/Elev= 30
  4385.4  660.86  4449.9  658.55  4457.6  659.03  4478.2  658.13  4485.9  656.87
  4491.1  657.84  4498.8  656.64  4509.1  658.46  4527.2  659.26  4668.3  658.94
  4774.6  658.34  4820.9  656.95  4890.5  656.75  4911.1  657.31  4921.4  656.49
  4939.5  652.23  4985.9  650.02  5012.3  650.60  5038.2  649.49  5038.5  648.99
  5042.0  648.99  5042.2  649.49  5048.6  652.66  5062.6  652.90  5079.4  654.63
  5085.0  653.97  5101.7  658.18  5107.3  658.44  5112.9  661.21  5115.7  661.21
#Mann=4,-1,0
  4385.4   0.075       0  4668.3    0.05       0  5038.2   0.033       0
  5042.2    0.05       0
Bank Sta=5038.2,5042.2
Exp/Cntr=0.3,0.1

Type RM Length L Ch R = 1,3057,282,282,282
BEGIN DESCRIPTION:
Old Buffalo Creek 6.0
END DESCRIPTION:
XS GIS Cut Line= 3
      2333664.24      7037940.38      2334279.00      7037760.00
      2334329.03      7037760.00
#Sta/Elev= 30
  4363.3  654.99  4383.1  653.70  4399.5  655.25  4449.9  654.20  4503.7  655.13
  4514.2  652.66  4521.9  649.74  4535.0  654.69  4593.9  654.23  4669.8  655.05
  4826.8  655.37  4868.5  652.92  4876.7  654.11  4899.8  654.28  4910.1  652.49
  4915.3  650.77  4931.0  649.13  4962.3  648.21  4972.7  649.33  4985.3  647.48
  4985.5  646.98  4989.3  647.48  4993.6  647.83  5001.4  650.39  5006.5  650.39
  5024.0  656.85  5034.0  657.92  5044.0  661.11  5051.5  664.66  5054.0  664.66
#Mann=4,-1,0
  4363.3   0.075       0  4669.8    0.05       0  4985.3   0.033       0
  4989.3    0.05       0
Bank Sta=4985.3,4989.3
Exp/Cntr=0.3,0.1

Type RM Length L Ch R = 1,2775,266,266,266
BEGIN DESCRIPTION:
Old Buffalo Creek 5.0
END DESCRIPTION:
XS GIS Cut Line= 3
      2333650.66      7038293.49      2334379.00      7038010.00
      2334628.98      7037910.01
#Sta/Elev= 30
  4222.5  662.41  4241.4  664.51  4276.6  663.57  4301.1  660.09  4306.6  657.16
  4355.5  650.20  4436.9  649.51  4593.0  647.65  4635.9  648.06  4743.3  647.87
  4789.5  645.91  4796.1  646.68  4801.4  644.45  4820.6  645.18  4825.9  642.13
  4862.6  640.95  4862.8  640.45  4866.6  640.95  4896.8  642.62  4904.8  645.44
  4918.2  646.78  4964.6  647.99  4982.6  644.47  5067.3  647.13  5090.2  649.02
  5111.8  652.92  5197.9  657.83  5234.3  665.62  5241.0  669.67  5273.3  670.45
#Mann=7,-1,0
  4222.5   0.075       0  4436.9    0.05       0  4593.0   0.075       0
  4635.9    0.12       0  4743.3    0.05       0  4862.6   0.033       0
  4866.6    0.05       0
Bank Sta=4862.6,4866.6
Exp/Cntr=0.3,0.1

Type RM Length L Ch R = 1,2509,531,531,531
BEGIN DESCRIPTION:
Old Buffalo Creek 4.0
END DESCRIPTION:
XS GIS Cut Line= 3
      2333709.53      7038560.58      2334429.00      7038260.00
      2334578.98      7038060.03
#Sta/Elev= 30
  4224.8  666.26  4239.9  667.33  4269.1  666.64  4278.4  665.32  4292.9  662.51
  4316.7  653.10  4340.5  647.61  4364.3  645.90  4405.1  645.88  4430.1  648.37
  4462.7  646.52  4484.3  647.58  4614.4  645.77  4653.3  643.62  4690.2  647.11
  4728.7  646.87  4754.0  644.99  4836.2  644.93  4850.8  639.48  4851.1  638.98
  4854.8  639.48  4865.5  639.57  4883.8  642.86  4928.7  644.46  4995.3  641.84
  5007.7  642.20  5026.4  643.87  5047.2  647.49  5068.1  649.18  5254.5  657.87
#Mann=6,-1,0
  4224.8   0.075       0  4405.1    0.05       0  4728.7    0.12       0
  4850.8   0.033       0  4854.8    0.12       0  4883.8    0.05       0
Bank Sta=4850.8,4854.8
Exp/Cntr=0.3,0.1

Type RM Length L Ch R = 1,1978,165,165,165
BEGIN DESCRIPTION:
Old Buffalo Creek 3.0
END DESCRIPTION:
XS GIS Cut Line= 3
      2333754.78      7038669.25      2334515.10      7038712.13
      2334628.98      7038510.03
#Sta/Elev= 30
  4274.3  659.38  4308.6  657.79  4328.6  653.50  4348.6  647.07  4358.7  646.06
  4412.4  646.10  4498.9  648.85  4641.3  648.57  4727.9  648.01  4839.4  644.97
  4899.5  641.98  4906.9  642.08  4911.9  645.72  4929.6  645.45  4959.6  638.70
  4969.6  637.15  4987.7  636.36  4987.9  635.86  4991.7  636.36  5019.7  645.00
  5029.7  646.44  5039.9  646.78  5074.8  644.25  5084.2  642.44  5157.3  647.96
  5173.2  647.85  5179.0  649.31  5194.9  648.59  5221.0  649.48  5267.8  651.33
#Mann=7,-1,0
  4274.3     0.1       0  4412.4   0.075       0  4641.3    0.05       0
  4987.7    0.05       0  4991.7    0.05       0  5074.8   0.075       0
  5221.0     0.1       0
Bank Sta=4987.7,4991.7
Exp/Cntr=0.3,0.1

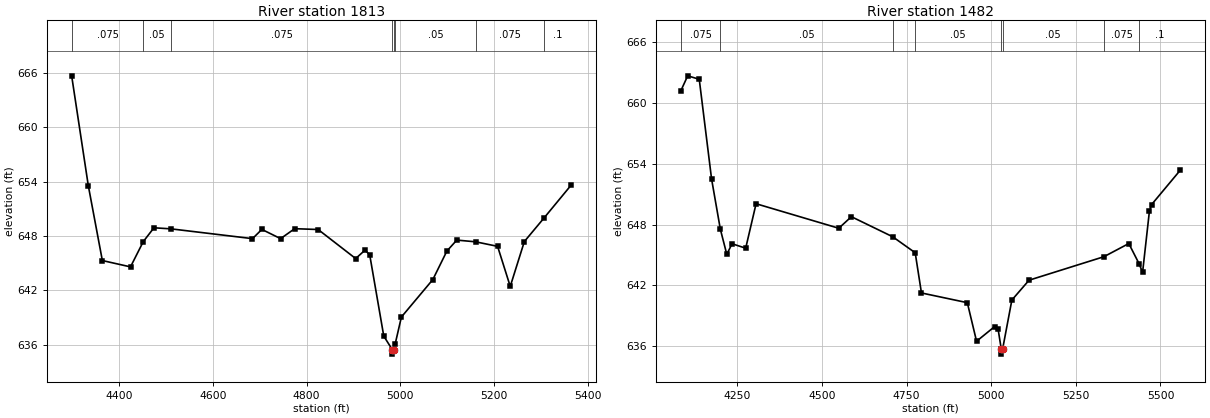
Type RM Length L Ch R = 1,1813,331,331,331
BEGIN DESCRIPTION:
Old Buffalo Creek 2.0
END DESCRIPTION:
XS GIS Cut Line= 3
      2333823.54      7038891.67      2334529.00      7038860.00
      2334728.98      7038560.02
#Sta/Elev= 30
  4298.8  665.70  4334.3  653.57  4364.3  645.29  4424.4  644.59  4451.6  647.38
  4474.4  648.91  4511.0  648.79  4684.7  647.71  4704.7  648.73  4744.7  647.71
  4774.7  648.81  4824.8  648.72  4904.9  645.51  4924.9  646.44  4934.9  645.92
  4964.9  636.94  4983.0  635.45  4983.2  634.95  4987.0  635.45  4989.1  636.04
  5002.5  639.05  5069.6  643.19  5099.6  646.34  5120.7  647.55  5160.9  647.36
  5207.8  646.86  5234.8  642.43  5264.9  647.39  5306.7  649.98  5365.5  653.67
#Mann=8,-1,0
  4298.8   0.075       0  4451.6    0.05       0  4511.0   0.075       0
  4983.0    0.05       0  4987.0   0.075       0  4989.1    0.05       0
  5160.9   0.075       0  5306.7     0.1       0
Bank Sta=4983,4987
Exp/Cntr=0.3,0.1

Type RM Length L Ch R = 1,1482,0,0,0
BEGIN DESCRIPTION:
Old Buffalo Creek 1.0
END DESCRIPTION:
XS GIS Cut Line= 3
      2333818.13      7039221.56      2334729.00      7039110.00
      2334829.00      7038559.99
#Sta/Elev= 30
  4082.3  661.17  4103.3  662.70  4137.4  662.36  4173.8  652.52  4199.7  647.56
  4218.8  645.07  4234.3  646.12  4274.6  645.68  4305.3  650.07  4549.6  647.65
  4586.9  648.79  4708.9  646.81  4775.4  645.23  4793.9  641.26  4929.4  640.30
  4956.7  636.49  5010.1  637.94  5020.3  637.70  5029.7  635.72  5030.0  635.22
  5033.7  635.72  5061.0  640.56  5111.8  642.52  5333.0  644.84  5406.5  646.14
  5436.8  644.15  5447.2  643.29  5467.5  649.37  5473.9  649.99  5559.0  653.40
#Mann=8,-1,0
  4082.3   0.075       0  4199.7    0.05       0  4708.9   0.075       0
  4775.4    0.05       0  5029.7   0.033       0  5033.7    0.05       0
  5333.0   0.075       0  5436.8     0.1       0
Bank Sta=5029.7,5033.7
Exp/Cntr=0.3,0.1

Chan Stop Cuts=-1