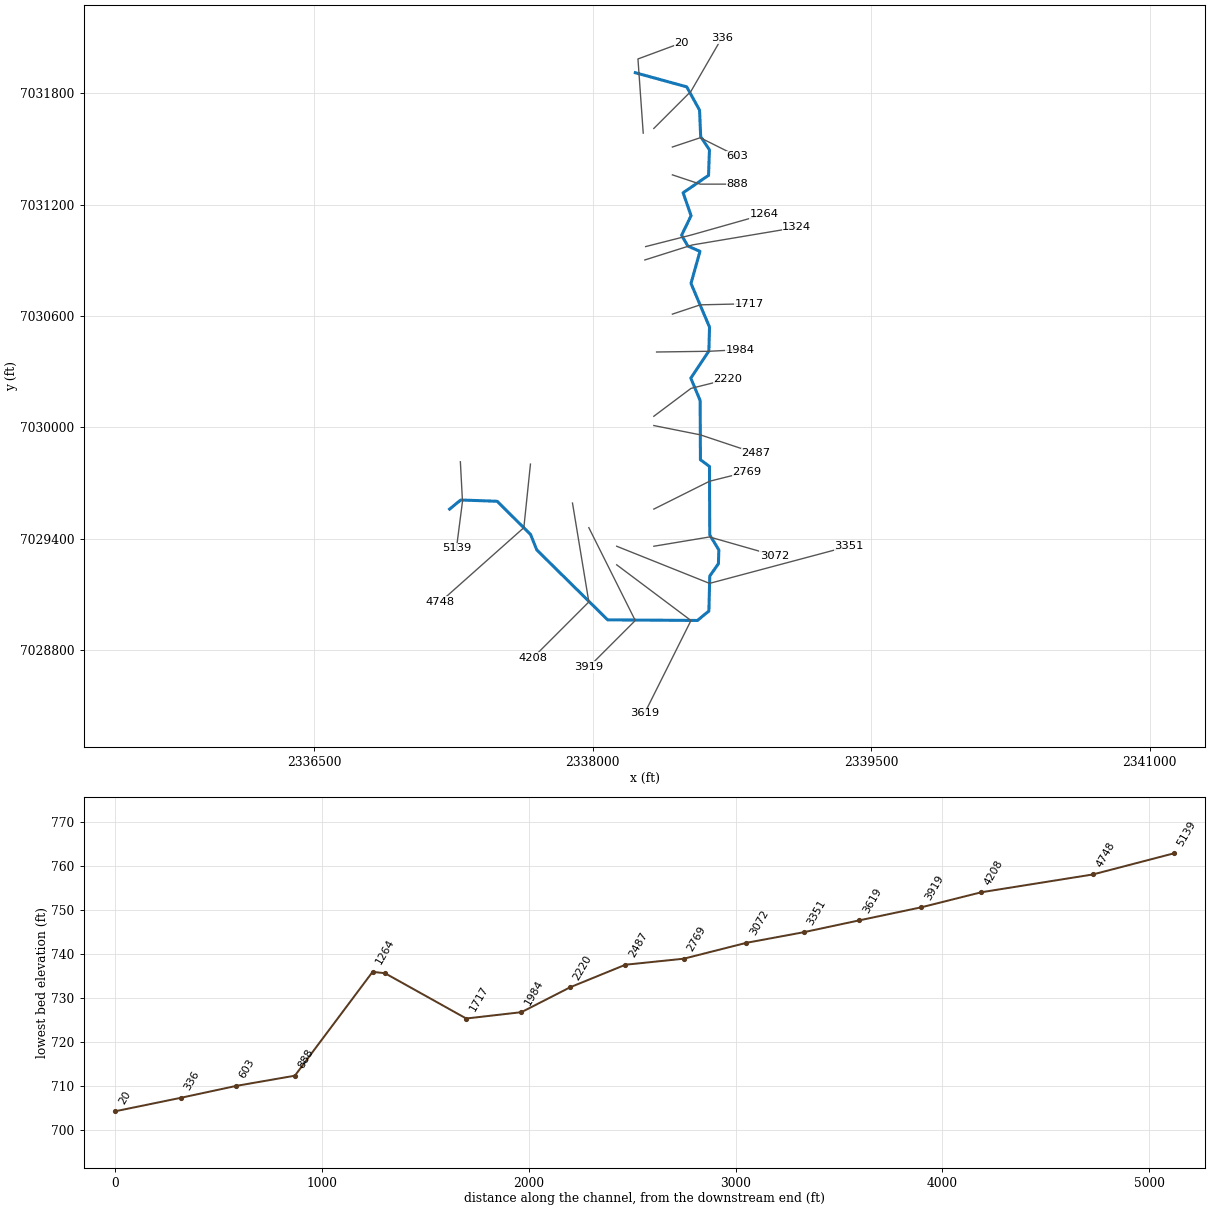
--- Powel Creek.prj (project) ---

Proj Title=Powel Creek Base Level Engineering
Current Plan=p01
Default Exp/Contr=0.3,0.1
English Units
Geom File=g01
Flow File=f01
Plan File=p01
BEGIN DESCRIPTION:
Powel Creek
END DESCRIPTION:

--- Powel Creek.p01 (plan) ---

Plan Title=Multiple Run
Short Identifier=Multiple
Geom File=g01
Flow File=f01
Subcritical Flow
K Sum by GR= 0
Std Step Tol= 0.01
Critical Tol= 0.01
Num of Std Step Trials= 20
Max Error Tol= 0.3
Flow Tol Ratio= 0.001
Split Flow NTrial= 30
Split Flow Tol= 0.02
Split Flow Ratio= 0.02
Log Output Level= 0
Friction Slope Method= 1
Unsteady Friction Slope Method= 2
Unsteady Bridges Friction Slope Method= 1
Parabolic Critical Depth
Global Vel Dist=  1 , 1 , 1
Global Log Level= 0
CheckData=True
Encroach Param= -1, 0, 0, 0
BEGIN DESCRIPTION:
Multiple Run
END DESCRIPTION:

--- Powel Creek.f01 (steady flow) ---

Flow Title=Multiple
Number of Profiles=7
Profile Names=10-year,25-year,50-year,1pct_min,100-year,1pct_plu,500-year
River Rch & RM= Powel Creek,Reach-1,5139
     356     469     557     329     657    1310     912
River Rch & RM= Powel Creek,Reach-1,20
     463     621     747     447     891    1780    1270
Boundary for River Rch & Prof#=Powel Creek,Reach-1,1
Up Type=0
Dn Type=3
Dn Slope=0.005
Boundary for River Rch & Prof#=Powel Creek,Reach-1,2
Up Type=0
Dn Type=3
Dn Slope=0.005
Boundary for River Rch & Prof#=Powel Creek,Reach-1,3
Up Type=0
Dn Type=3
Dn Slope=0.005
Boundary for River Rch & Prof#=Powel Creek,Reach-1,4
Up Type=0
Dn Type=3
Dn Slope=0.005
Boundary for River Rch & Prof#=Powel Creek,Reach-1,5
Up Type=0
Dn Type=3
Dn Slope=0.005
Boundary for River Rch & Prof#=Powel Creek,Reach-1,6
Up Type=0
Dn Type=3
Dn Slope=0.005
Boundary for River Rch & Prof#=Powel Creek,Reach-1,7
Up Type=0
Dn Type=3
Dn Slope=0.005

--- Powel Creek.g01 (geometry) ---

Geom Title=Existing Conditions

River Reach=Powel Creek,Reach-1
Reach XY= 30
      2337229.00      7029560.00      2337289.40      7029609.04
      2337485.19      7029602.19      2337665.37      7029423.21
      2337698.79      7029339.91      2338080.46      7028963.54
      2338563.98      7028960.32      2338625.57      7029011.22
      2338630.22      7029199.50      2338676.83      7029265.98
      2338679.09      7029339.90      2338630.22      7029420.50
      2338628.70      7029789.70      2338579.96      7029825.96
      2338578.48      7030144.78      2338528.15      7030265.05
      2338625.46      7030411.47      2338628.95      7030539.96
      2338529.09      7030775.39      2338577.47      7030948.12
      2338512.00      7030976.59      2338478.48      7031034.88
      2338529.57      7031139.95      2338486.70      7031263.67
      2338623.65      7031357.30      2338628.49      7031494.78
      2338581.27      7031565.94      2338575.24      7031708.44
      2338506.20      7031833.97      2338229.00      7031910.00

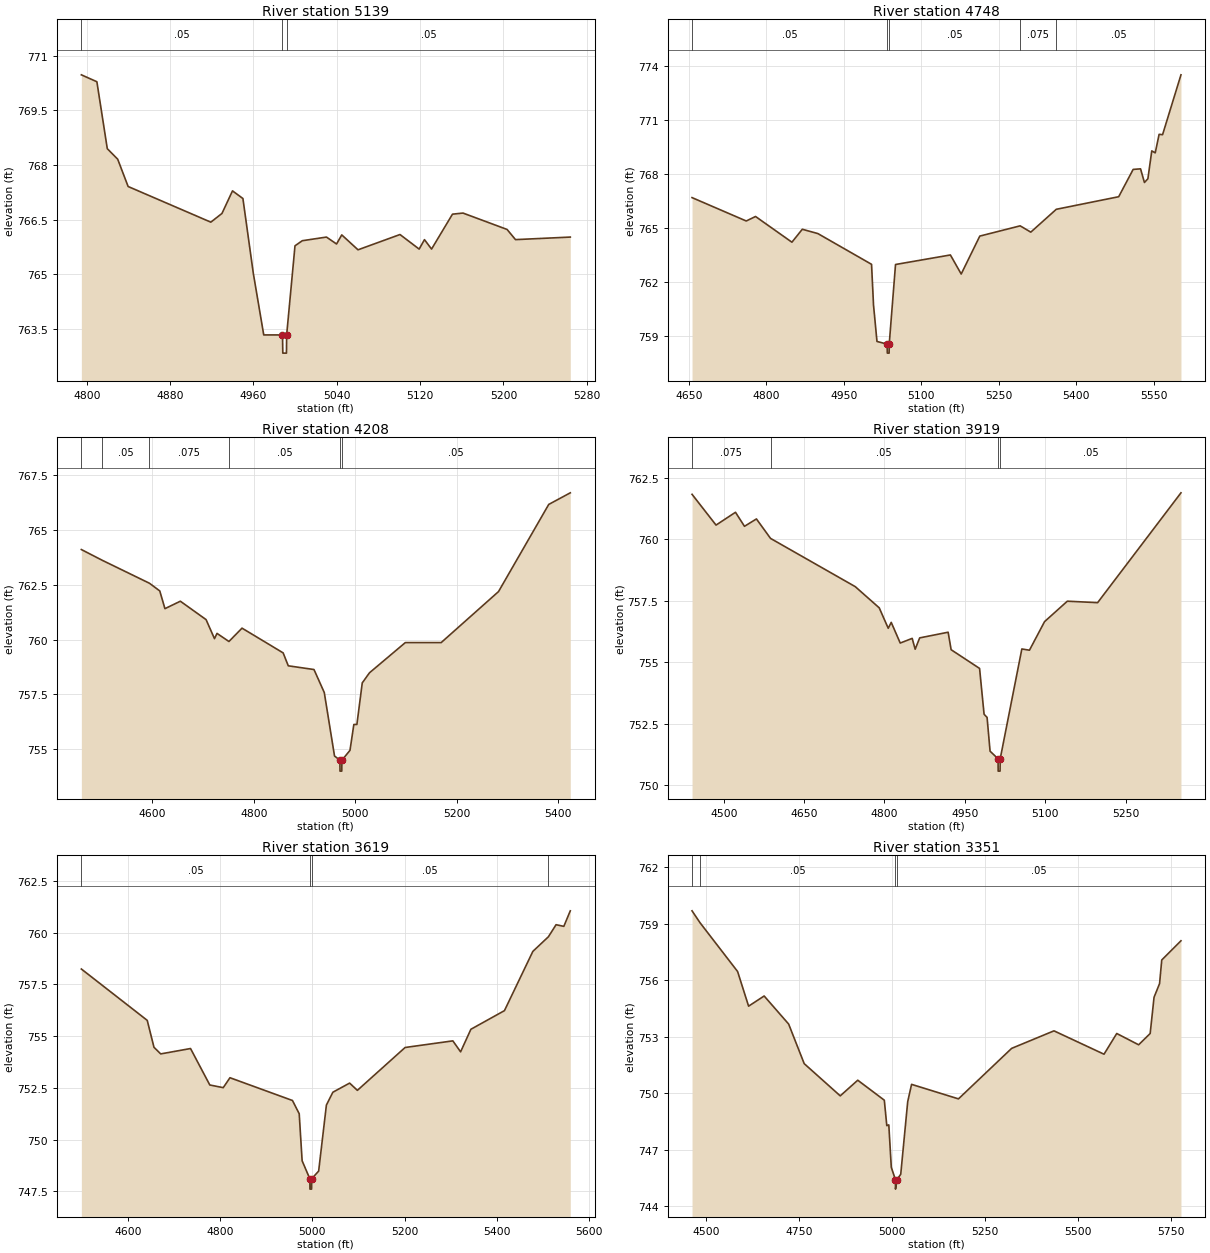
Type RM Length L Ch R = 1,5139,391,391,391
BEGIN DESCRIPTION:
Powel Creek 17.0
END DESCRIPTION:
XS GIS Cut Line= 3
      2337287.17      7029814.86      2337298.55      7029601.04
      2337265.81      7029347.87
#Sta/Elev= 30
  4794.8  770.48  4809.7  770.29  4819.7  768.45  4829.7  768.16  4839.7  767.41
  4919.1  766.43  4929.8  766.67  4939.9  767.29  4949.9  767.08  4959.9  765.02
  4969.9  763.33  4987.9  763.33  4988.2  762.83  4991.7  762.83  4991.9  763.33
  4999.9  765.78  5006.9  765.92  5030.1  766.02  5039.8  765.83  5044.8  766.08
  5060.4  765.67  5100.7  766.09  5119.1  765.69  5124.2  765.95  5131.0  765.69
  5151.1  766.65  5161.2  766.68  5203.5  766.23  5211.6  765.95  5264.2  766.02
#Mann=3,-1,0
  4794.8    0.05       0  4987.9    0.05       0  4991.9    0.05       0
Bank Sta=4987.9,4991.9
Exp/Cntr=0.3,0.1

Type RM Length L Ch R = 1,4748,540,540,540
BEGIN DESCRIPTION:
Powel Creek 16.0
END DESCRIPTION:
XS GIS Cut Line= 3
      2337664.54      7029802.23      2337629.00      7029460.00
      2337178.96      7029059.97
#Sta/Elev= 30
  4656.2  766.69  4761.1  765.39  4779.1  765.64  4849.5  764.21  4869.6  764.93
  4899.7  764.69  5003.6  762.98  5007.4  760.72  5014.1  758.69  5033.8  758.54
  5034.1  758.04  5037.6  758.04  5037.8  758.54  5050.0  762.97  5156.2  763.50
  5177.1  762.44  5213.1  764.55  5291.2  765.12  5311.8  764.77  5361.1  766.04
  5481.9  766.74  5509.9  768.26  5524.2  768.29  5531.7  767.53  5538.4  767.74
  5545.9  769.29  5552.6  769.18  5560.1  770.21  5566.8  770.19  5602.4  773.52
#Mann=5,-1,0
  4656.2    0.05       0  5033.8    0.05       0  5037.8    0.05       0
  5291.2   0.075       0  5361.1    0.05       0
Bank Sta=5033.8,5037.8
Exp/Cntr=0.3,0.1

Type RM Length L Ch R = 1,4208,289,289,289
BEGIN DESCRIPTION:
Powel Creek 15.0
END DESCRIPTION:
XS GIS Cut Line= 3
      2337890.96      7029592.56      2337979.00      7029060.00
      2337678.97      7028759.97
#Sta/Elev= 30
  4460.2  764.11  4501.3  763.62  4594.5  762.57  4614.8  762.22  4625.0  761.41
  4655.4  761.75  4706.1  760.91  4722.7  760.04  4727.7  760.28  4751.2  759.91
  4777.0  760.52  4858.1  759.39  4868.2  758.80  4918.9  758.63  4939.2  757.58
  4959.4  754.68  4970.0  754.49  4970.2  753.99  4973.7  753.99  4974.0  754.49
  4989.9  754.94  4997.5  756.12  5003.5  756.12  5014.1  758.02  5028.3  758.48
  5099.0  759.86  5169.7  759.86  5282.8  762.19  5381.8  766.17  5424.3  766.70
#Mann=6,-1,0
  4460.2   0.075       0  4501.3    0.05       0  4594.5   0.075       0
  4751.2    0.05       0  4970.0    0.05       0  4974.0    0.05       0
Bank Sta=4970,4974
Exp/Cntr=0.3,0.1

Type RM Length L Ch R = 1,3919,300,300,300
BEGIN DESCRIPTION:
Powel Creek 14.0
END DESCRIPTION:
XS GIS Cut Line= 3
      2337978.98      7029460.03      2338229.00      7028960.00
      2337979.00      7028710.00
#Sta/Elev= 30
  4440.9  761.82  4485.7  760.57  4522.0  761.09  4538.8  760.52  4561.1  760.82
  4587.4  760.03  4745.6  758.07  4790.3  757.21  4807.1  756.38  4812.7  756.62
  4829.5  755.78  4851.8  755.97  4857.4  755.53  4865.8  755.99  4918.9  756.22
  4924.5  755.51  4977.6  754.75  4986.0  752.89  4991.6  752.76  4997.2  751.39
  5012.1  751.08  5012.3  750.58  5015.8  750.58  5016.1  751.08  5056.5  755.54
  5070.7  755.49  5098.9  756.65  5141.4  757.48  5197.9  757.42  5353.5  761.88
#Mann=4,-1,0
  4440.9   0.075       0  4587.4    0.05       0  5012.1    0.05       0
  5016.1    0.05       0
Bank Sta=5012.1,5016.1
Exp/Cntr=0.3,0.1

Type RM Length L Ch R = 1,3619,268,268,268
BEGIN DESCRIPTION:
Powel Creek 13.0
END DESCRIPTION:
XS GIS Cut Line= 3
      2338128.97      7029260.02      2338529.00      7028960.00
      2338278.98      7028459.96
#Sta/Elev= 30
  4499.5  758.24  4642.2  755.76  4656.8  754.46  4671.4  754.14  4736.0  754.40
  4777.7  752.64  4806.8  752.51  4821.4  752.99  4956.8  751.89  4971.4  751.25
  4977.7  748.98  4994.4  748.11  4994.7  747.61  4998.2  747.61  4998.4  748.11
  5013.5  748.48  5030.3  751.67  5044.3  752.29  5080.6  752.73  5097.4  752.38
  5200.8  754.45  5304.2  754.77  5321.0  754.24  5343.3  755.33  5416.0  756.23
  5477.5  759.09  5511.3  759.80  5527.8  760.38  5544.6  760.30  5558.6  761.05
#Mann=4,-1,0
  4499.5    0.05       0  4994.4    0.05       0  4998.4    0.05       0
  5511.3   0.075       0
Bank Sta=4994.4,4998.4
Exp/Cntr=0.3,0.1

Type RM Length L Ch R = 1,3351,279,279,279
BEGIN DESCRIPTION:
Powel Creek 12.0
END DESCRIPTION:
XS GIS Cut Line= 3
      2338128.99      7029360.01      2338629.00      7029160.00
      2339378.96      7029359.99
#Sta/Elev= 30
  4461.9  759.69  4483.3  759.06  4584.4  756.47  4614.0  754.63  4655.8  755.17
  4721.7  753.68  4763.5  751.58  4860.4  749.87  4907.5  750.70  4978.9  749.64
  4985.6  748.29  4991.0  748.33  4997.7  746.08  5008.8  745.42  5009.0  744.92
  5012.8  745.42  5023.1  745.71  5041.8  749.56  5052.2  750.48  5178.3  749.71
  5321.3  752.39  5435.1  753.32  5569.7  752.08  5603.9  753.18  5662.8  752.58
  5693.8  753.18  5704.2  755.10  5719.1  755.83  5724.9  757.08  5776.6  758.10
#Mann=4,-1,0
  4461.9   0.075       0  4483.3    0.05       0  5008.8    0.05       0
  5012.8    0.05       0
Bank Sta=5008.8,5012.8
Exp/Cntr=0.3,0.1

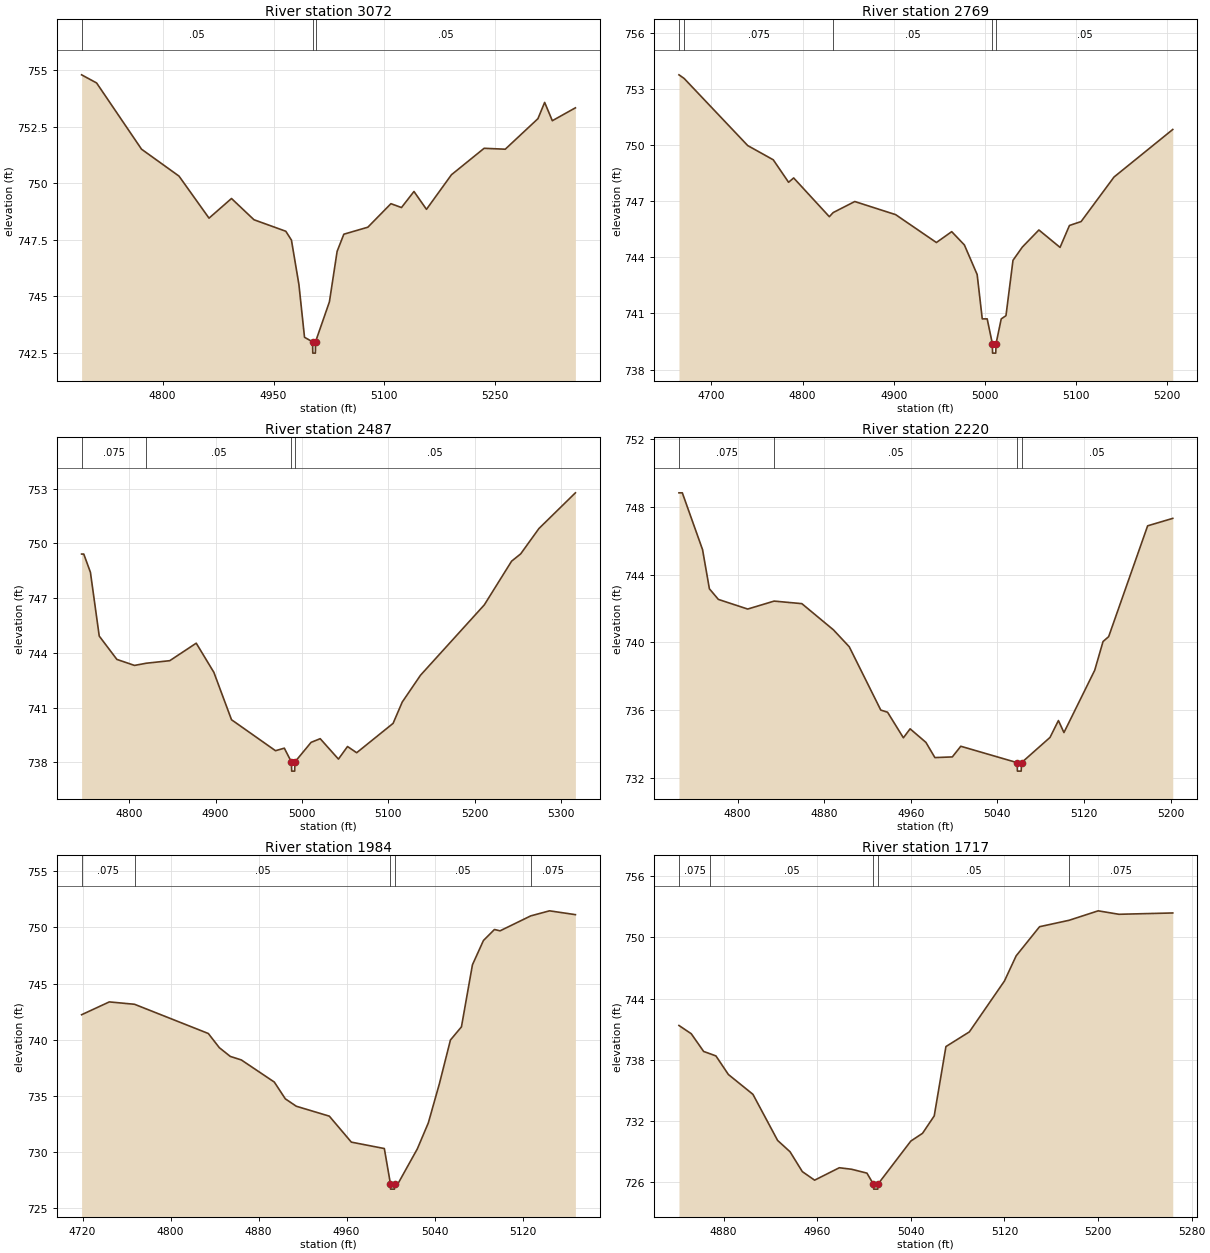
Type RM Length L Ch R = 1,3072,303,303,303
BEGIN DESCRIPTION:
Powel Creek 11.0
END DESCRIPTION:
XS GIS Cut Line= 3
      2338328.99      7029360.00      2338629.00      7029410.00
      2338978.95      7029310.01
#Sta/Elev= 30
  4690.3  754.80  4710.6  754.44  4771.4  751.51  4822.1  750.32  4862.7  748.46
  4893.1  749.33  4923.5  748.39  4966.6  747.88  4974.2  747.49  4984.3  745.53
  4991.9  743.19  5002.8  742.99  5003.1  742.49  5006.6  742.49  5006.8  742.99
  5025.6  744.76  5036.0  746.99  5045.1  747.75  5077.6  748.06  5108.8  749.10
  5123.1  748.93  5140.0  749.64  5156.9  748.85  5190.7  750.38  5234.9  751.55
  5263.5  751.51  5307.7  752.86  5316.8  753.58  5327.2  752.77  5358.4  753.34
#Mann=3,-1,0
  4690.3    0.05       0  5002.8    0.05       0  5006.8    0.05       0
Bank Sta=5002.8,5006.8
Exp/Cntr=0.3,0.1

Type RM Length L Ch R = 1,2769,282,282,282
BEGIN DESCRIPTION:
Powel Creek 10.0
END DESCRIPTION:
XS GIS Cut Line= 3
      2338329.02      7029560.01      2338629.00      7029710.00
      2338828.96      7029759.99
#Sta/Elev= 30
  4664.5  753.75  4670.1  753.56  4739.9  749.97  4767.9  749.21  4784.7  748.01
  4790.3  748.24  4829.4  746.17  4833.6  746.39  4857.3  746.98  4902.1  746.28
  4946.8  744.79  4963.6  745.37  4977.5  744.66  4991.5  743.08  4997.1  740.71
  5002.5  740.71  5008.2  739.38  5008.4  738.88  5011.9  738.88  5012.2  739.38
  5017.9  740.71  5023.1  740.88  5030.8  743.84  5041.1  744.55  5059.2  745.46
  5082.4  744.53  5092.7  745.70  5105.5  745.91  5141.6  748.29  5206.0  750.83
#Mann=5,-1,0
  4664.5    0.05       0  4670.1   0.075       0  4833.6    0.05       0
  5008.2   0.033       0  5012.2    0.05       0
Bank Sta=5008.2,5012.2
Exp/Cntr=0.3,0.1

Type RM Length L Ch R = 1,2487,267,267,267
BEGIN DESCRIPTION:
Powel Creek 9.0
END DESCRIPTION:
XS GIS Cut Line= 3
      2338329.01      7030010.00      2338579.00      7029960.00
      2338879.03      7029859.99
#Sta/Elev= 30
  4745.1  749.42  4747.6  749.42  4755.3  748.42  4765.5  744.92  4785.9  743.64
  4806.3  743.31  4819.9  743.43  4847.1  743.57  4877.7  744.53  4898.1  742.93
  4918.5  740.33  4969.4  738.63  4979.6  738.77  4987.8  738.01  4988.1  737.51
  4991.6  737.51  4991.8  738.01  5010.6  739.09  5021.1  739.29  5042.2  738.17
  5052.7  738.86  5063.3  738.52  5105.4  740.13  5116.0  741.30  5137.1  742.77
  5210.9  746.63  5242.5  749.03  5253.0  749.43  5274.1  750.82  5316.3  752.78
#Mann=4,-1,0
  4745.1   0.075       0  4819.9    0.05       0  4987.8   0.033       0
  4991.8    0.05       0
Bank Sta=4987.8,4991.8
Exp/Cntr=0.3,0.1

Type RM Length L Ch R = 1,2220,236,236,236
BEGIN DESCRIPTION:
Powel Creek 8.0
END DESCRIPTION:
XS GIS Cut Line= 3
      2338329.02      7030060.02      2338529.00      7030210.00
      2338728.97      7030259.99
#Sta/Elev= 30
  4745.9  748.84  4749.0  748.84  4767.7  745.48  4774.0  743.17  4782.3  742.54
  4809.4  741.97  4833.8  742.44  4859.4  742.29  4888.6  740.74  4903.2  739.74
  4932.3  736.00  4938.6  735.87  4953.2  734.36  4959.4  734.89  4974.0  734.09
  4982.3  733.19  4998.4  733.23  5006.2  733.86  5058.3  732.89  5058.5  732.39
  5062.0  732.39  5062.3  732.89  5088.6  734.38  5096.4  735.38  5101.5  734.67
  5129.9  738.35  5137.6  740.05  5142.8  740.34  5178.8  746.89  5202.0  747.33
#Mann=4,-1,0
  4745.9   0.075       0  4833.8    0.05       0  5058.3   0.033       0
  5062.3    0.05       0
Bank Sta=5058.3,5062.3
Exp/Cntr=0.3,0.1

Type RM Length L Ch R = 1,1984,267,267,267
BEGIN DESCRIPTION:
Powel Creek 7.0
END DESCRIPTION:
XS GIS Cut Line= 3
      2338343.83      7030406.02      2338629.00      7030410.00
      2338792.48      7030418.60
#Sta/Elev= 30
  4719.1  742.23  4744.3  743.37  4767.2  743.16  4834.3  740.56  4844.3  739.30
  4854.3  738.52  4864.3  738.21  4894.3  736.24  4904.3  734.75  4914.3  734.09
  4944.3  733.21  4964.3  730.90  4994.3  730.33  4999.8  727.22  5000.0  726.72
  5003.5  726.72  5003.8  727.22  5006.8  727.22  5024.3  730.30  5034.3  732.61
  5044.4  736.11  5054.4  739.98  5064.4  741.15  5074.4  746.67  5084.4  748.83
  5094.4  749.81  5099.5  749.69  5127.4  751.02  5144.5  751.47  5168.0  751.13
#Mann=5,-1,0
  4719.1   0.075       0  4767.2    0.05       0  4999.8    0.05       0
  5003.8    0.05       0  5127.4   0.075       0
Bank Sta=4999.8,5003.8
Exp/Cntr=0.3,0.1

Type RM Length L Ch R = 1,1717,393,393,393
BEGIN DESCRIPTION:
Powel Creek 6.0
END DESCRIPTION:
XS GIS Cut Line= 3
      2338429.01      7030610.00      2338579.00      7030660.00
      2338842.73      7030665.98
#Sta/Elev= 30
  4841.9  741.35  4852.4  740.54  4863.0  738.80  4868.8  738.56  4873.5  738.36
  4884.1  736.54  4905.1  734.59  4926.2  730.06  4936.8  728.95  4947.3  727.00
  4957.8  726.16  4978.9  727.38  4989.5  727.23  5002.5  726.85  5008.0  725.78
  5008.3  725.28  5011.8  725.28  5012.0  725.78  5040.0  730.00  5050.0  730.76
  5060.0  732.47  5070.0  739.28  5090.0  740.72  5120.0  745.72  5130.0  748.19
  5150.0  751.05  5175.2  751.68  5200.1  752.61  5217.8  752.27  5263.8  752.40
#Mann=5,-1,0
  4841.9   0.075       0  4868.8    0.05       0  5008.0   0.033       0
  5012.0    0.05       0  5175.2   0.075       0
Bank Sta=5008,5012
Exp/Cntr=0.3,0.1

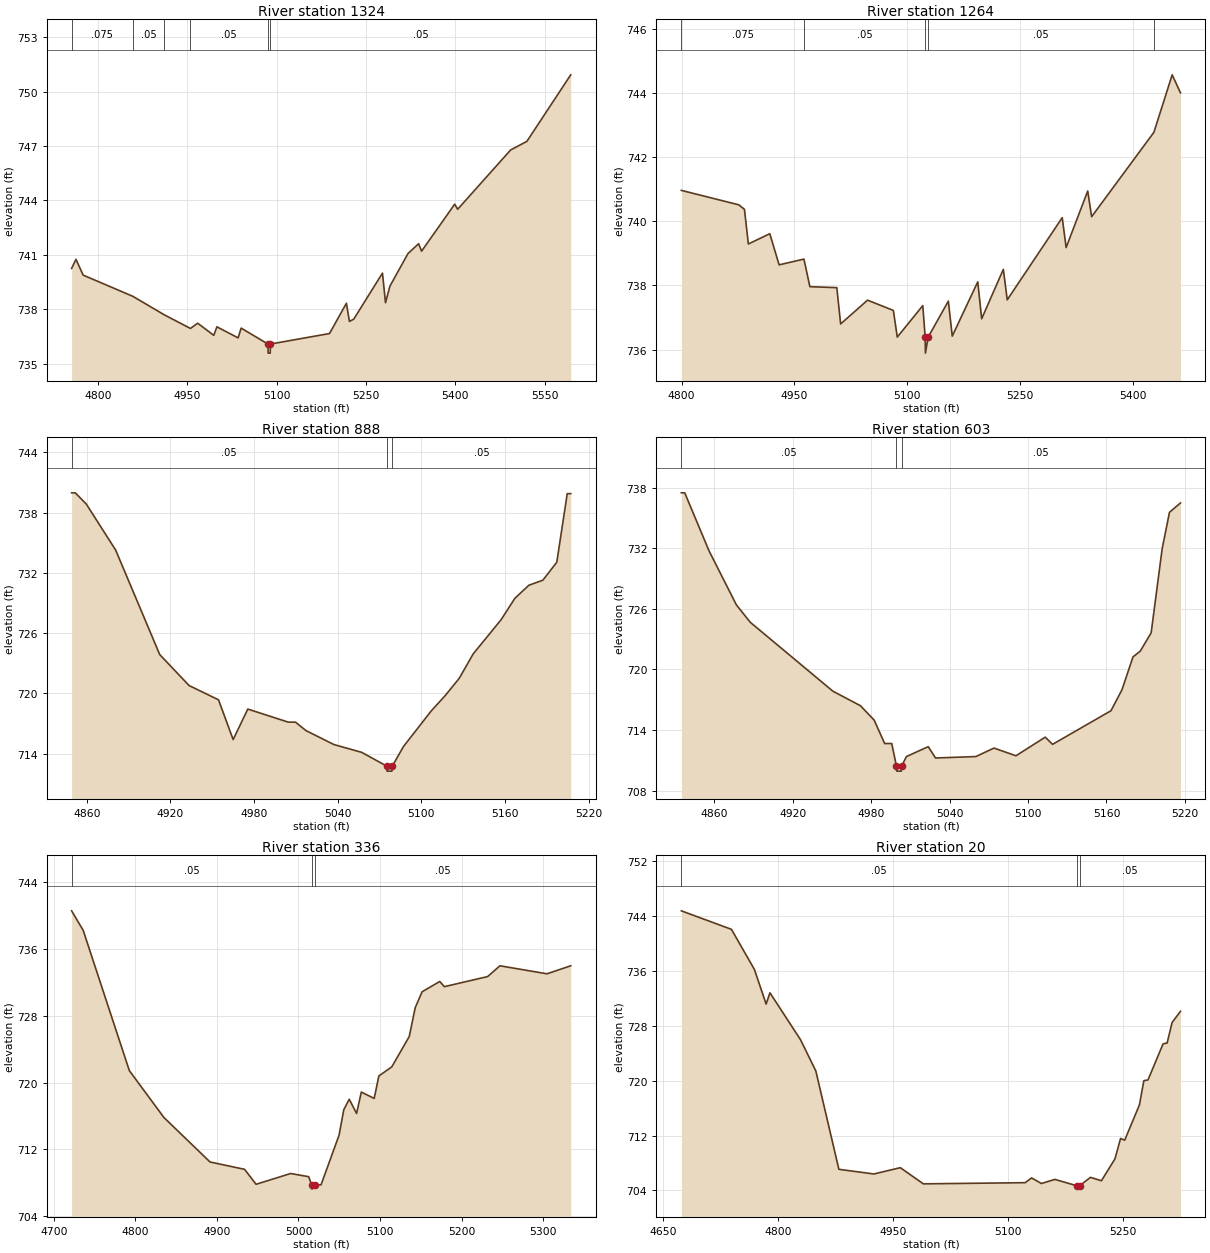
Type RM Length L Ch R = 1,1324,60,60,60
BEGIN DESCRIPTION:
Powel Creek 5.0
END DESCRIPTION:
XS GIS Cut Line= 3
      2338280.55      7030901.68      2338535.92      7030982.44
      2339098.51      7031076.89
#Sta/Elev= 30
  4755.7  740.25  4763.0  740.75  4775.1  739.88  4858.6  738.71  4911.4  737.69
  4955.3  736.94  4967.4  737.23  4994.5  736.56  4999.7  737.03  5035.4  736.42
  5040.4  736.96  5085.5  736.08  5085.8  735.58  5089.3  735.58  5089.5  736.08
  5188.9  736.66  5217.2  738.33  5222.3  737.33  5229.5  737.45  5277.8  739.99
  5282.9  738.36  5290.3  739.27  5320.7  741.07  5338.5  741.61  5343.5  741.20
  5399.1  743.79  5404.1  743.51  5493.1  746.78  5520.3  747.25  5594.0  750.92
#Mann=6,-1,0
  4755.7   0.075       0  4858.6    0.05       0  4911.4   0.075       0
  4955.3    0.05       0  5085.5    0.05       0  5089.5    0.05       0
Bank Sta=5085.5,5089.5
Exp/Cntr=0.3,0.1

Type RM Length L Ch R = 1,1264,376,376,376
BEGIN DESCRIPTION:
Powel Creek 4.0
END DESCRIPTION:
XS GIS Cut Line= 3
      2338284.98      7030973.72      2338533.74      7031037.00
      2338925.29      7031147.80
#Sta/Elev= 30
  4799.6  740.96  4876.0  740.51  4883.5  740.37  4888.7  739.29  4917.2  739.61
  4929.6  738.64  4962.6  738.82  4970.5  737.96  5006.3  737.93  5011.4  736.80
  5047.2  737.54  5081.5  737.22  5086.7  736.39  5120.6  737.37  5123.8  736.39
  5124.1  735.89  5127.8  736.39  5154.6  737.51  5159.8  736.42  5193.7  738.11
  5198.9  736.96  5227.7  738.50  5232.9  737.55  5306.0  740.11  5311.2  739.18
  5339.9  740.94  5345.1  740.14  5427.9  742.77  5452.2  744.56  5463.2  744.00
#Mann=5,-1,0
  4799.6   0.075       0  4962.6    0.05       0  5123.8    0.05       0
  5127.8    0.05       0  5427.9   0.075       0
Bank Sta=5123.8,5127.8
Exp/Cntr=0.3,0.1

Type RM Length L Ch R = 1,888,285,285,285
BEGIN DESCRIPTION:
Powel Creek 3.0
END DESCRIPTION:
XS GIS Cut Line= 3
      2338429.04      7031359.99      2338579.00      7031310.00
      2338779.03      7031310.00
#Sta/Elev= 30
  4849.1  739.98  4851.7  739.98  4859.6  738.87  4880.7  734.28  4912.3  723.88
  4933.4  720.79  4954.5  719.37  4965.0  715.41  4975.5  718.45  5004.5  717.15
  5009.7  717.15  5017.2  716.31  5037.2  714.92  5057.2  714.14  5075.2  712.77
  5075.4  712.27  5078.9  712.27  5079.2  712.77  5087.2  714.72  5107.2  718.28
  5117.2  719.80  5127.2  721.51  5137.2  723.94  5157.2  727.34  5167.2  729.49
  5177.2  730.78  5187.2  731.28  5197.2  733.07  5204.7  739.90  5207.2  739.90
#Mann=3,-1,0
  4849.1    0.05       0  5075.2   0.033       0  5079.2    0.05       0
Bank Sta=5075.2,5079.2
Exp/Cntr=0.3,0.1

Type RM Length L Ch R = 1,603,267,267,267
BEGIN DESCRIPTION:
Powel Creek 2.0
END DESCRIPTION:
XS GIS Cut Line= 3
      2338429.02      7031510.01      2338579.00      7031560.00
      2338779.00      7031460.00
#Sta/Elev= 30
  4834.9  737.48  4837.5  737.48  4856.0  731.76  4877.0  726.39  4887.6  724.67
  4950.8  717.85  4971.9  716.41  4982.4  714.98  4990.4  712.67  4995.8  712.67
  4999.4  710.44  4999.6  709.94  5003.1  709.94  5003.4  710.44  5007.0  711.38
  5023.7  712.36  5029.3  711.24  5060.1  711.38  5074.0  712.22  5090.8  711.46
  5113.2  713.30  5118.8  712.59  5163.5  715.92  5171.9  718.00  5180.3  721.24
  5185.9  721.82  5194.2  723.63  5202.6  731.94  5208.2  735.55  5216.6  736.48
#Mann=3,-1,0
  4834.9    0.05       0  4999.4   0.033       0  5003.4    0.05       0
Bank Sta=4999.4,5003.4
Exp/Cntr=0.3,0.1

Type RM Length L Ch R = 1,336,316,316,316
BEGIN DESCRIPTION:
Powel Creek 1.0
END DESCRIPTION:
XS GIS Cut Line= 3
      2338328.97      7031609.97      2338529.00      7031810.00
      2338693.84      7032095.20
#Sta/Elev= 30
  4721.7  740.56  4735.9  738.22  4792.5  721.43  4834.9  715.82  4891.5  710.49
  4933.9  709.61  4948.0  707.82  4990.4  709.11  5012.5  708.73  5016.2  707.74
  5016.5  707.24  5020.2  707.74  5027.7  707.76  5049.8  713.70  5055.6  716.75
  5062.3  718.00  5071.3  716.30  5077.1  718.86  5092.9  718.10  5098.6  720.79
  5114.4  721.87  5135.9  725.51  5143.2  728.96  5151.7  730.87  5173.3  732.10
  5179.0  731.48  5232.1  732.69  5247.1  733.98  5304.9  733.02  5334.0  733.98
#Mann=3,-1,0
  4721.7    0.05       0  5016.2   0.033       0  5020.2    0.05       0
Bank Sta=5016.2,5020.2
Exp/Cntr=0.3,0.1

Type RM Length L Ch R = 1,20,0,0,0
BEGIN DESCRIPTION:
Powel Creek 0.5
END DESCRIPTION:
XS GIS Cut Line= 3
      2338271.86      7031584.81      2338243.49      7031984.13
      2338479.22      7032071.43
#Sta/Elev= 30
  4673.6  744.79  4739.0  742.09  4769.0  736.24  4784.3  731.19  4789.3  732.83
  4829.2  725.99  4849.2  721.43  4879.3  707.08  4925.0  706.40  4959.5  707.32
  4989.6  704.96  5122.5  705.13  5130.9  705.82  5143.8  705.01  5161.3  705.61
  5189.7  704.69  5189.9  704.19  5193.7  704.69  5207.8  705.91  5222.1  705.41
  5239.8  708.61  5247.1  711.58  5252.5  711.33  5271.7  716.47  5277.5  720.01
  5282.9  720.12  5302.6  725.38  5307.9  725.51  5314.4  728.50  5325.3  730.13
#Mann=3,-1,0
  4673.6    0.05       0  5189.7    0.05       0  5193.7    0.05       0
Bank Sta=5189.7,5193.7
Exp/Cntr=0.3,0.1

Chan Stop Cuts=-1