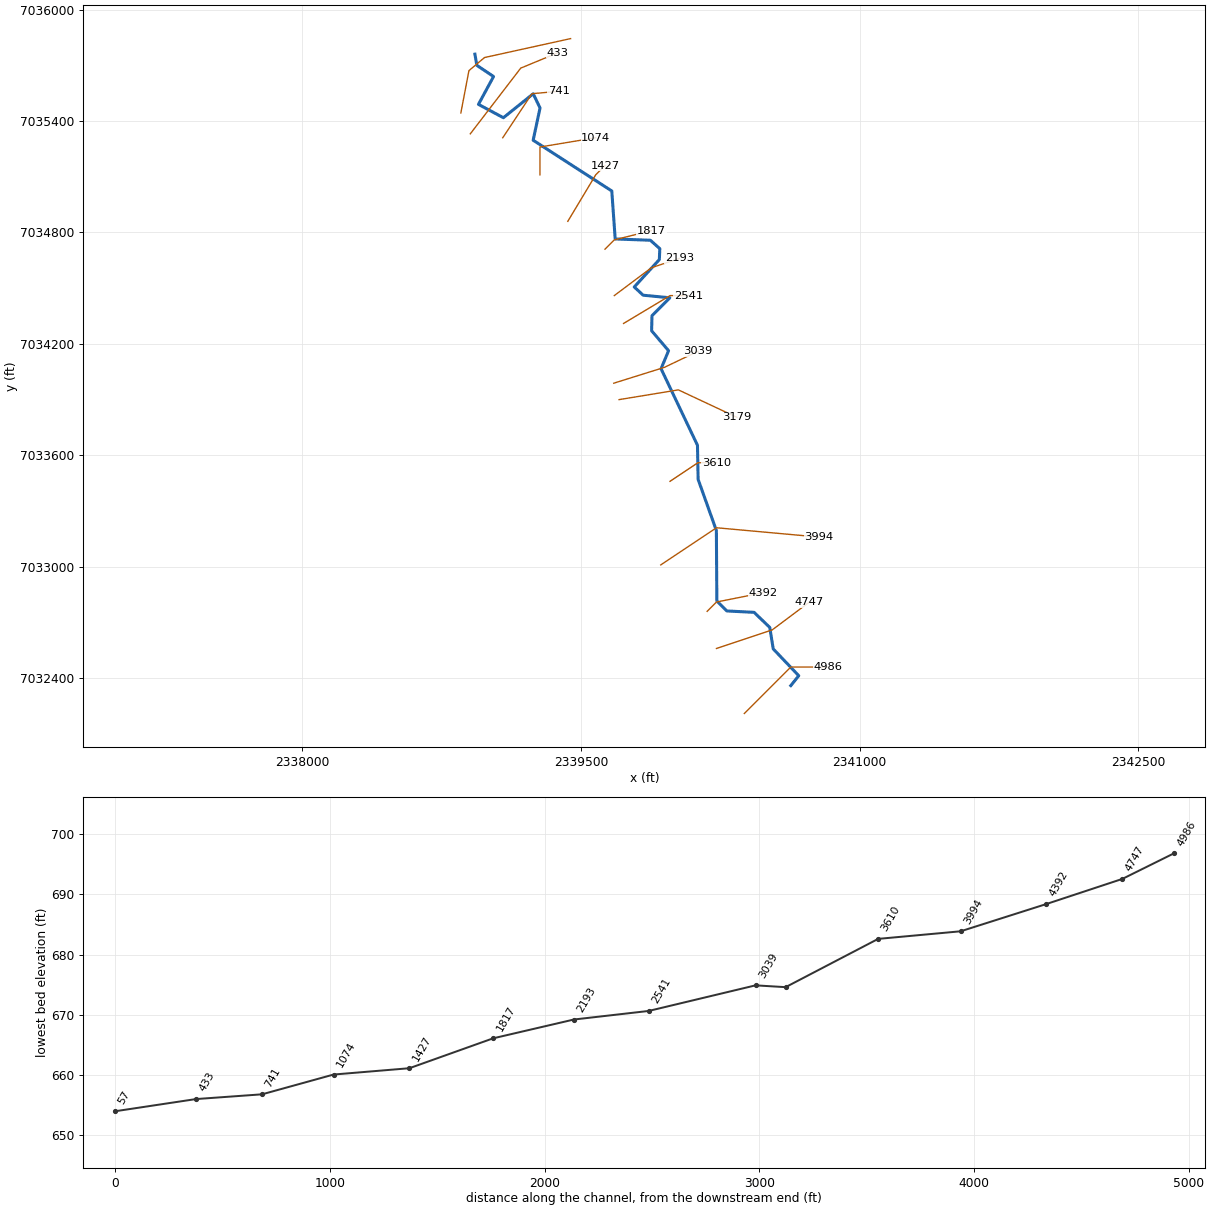
--- Powel Creek Tributary 1.prj (project) ---

Proj Title=Powel Creek Tributary 1 Base Level Engineering
Current Plan=p01
Default Exp/Contr=0.3,0.1
English Units
Geom File=g01
Flow File=f01
Plan File=p01
BEGIN DESCRIPTION:
Powel Creek Tributary 1
END DESCRIPTION:

--- Powel Creek Tributary 1.p01 (plan) ---

Plan Title=Multiple Run
Short Identifier=Multiple
Geom File=g01
Flow File=f01
Subcritical Flow
K Sum by GR= 0
Std Step Tol= 0.01
Critical Tol= 0.01
Num of Std Step Trials= 20
Max Error Tol= 0.3
Flow Tol Ratio= 0.001
Split Flow NTrial= 30
Split Flow Tol= 0.02
Split Flow Ratio= 0.02
Log Output Level= 0
Friction Slope Method= 1
Unsteady Friction Slope Method= 2
Unsteady Bridges Friction Slope Method= 1
Parabolic Critical Depth
Global Vel Dist=  1 , 1 , 1
Global Log Level= 0
CheckData=True
Encroach Param= -1, 0, 0, 0
BEGIN DESCRIPTION:
Multiple Run
END DESCRIPTION:

--- Powel Creek Tributary 1.f01 (steady flow) ---

Flow Title=Multiple
Number of Profiles=7
Profile Names=10-year,25-year,50-year,1pct_min,100-year,1pct_plu,500-year
River Rch & RM= Powel Creek Trib,Reach-1,4986
     500     671     810     485     968    1930    1380
River Rch & RM= Powel Creek Trib,Reach-1,4392
     623     849    1030     623    1240    2480    1800
Boundary for River Rch & Prof#=Powel Creek Trib,Reach-1,1
Up Type=0
Dn Type=3
Dn Slope=0.005
Boundary for River Rch & Prof#=Powel Creek Trib,Reach-1,2
Up Type=0
Dn Type=3
Dn Slope=0.005
Boundary for River Rch & Prof#=Powel Creek Trib,Reach-1,3
Up Type=0
Dn Type=3
Dn Slope=0.005
Boundary for River Rch & Prof#=Powel Creek Trib,Reach-1,4
Up Type=0
Dn Type=3
Dn Slope=0.005
Boundary for River Rch & Prof#=Powel Creek Trib,Reach-1,5
Up Type=0
Dn Type=3
Dn Slope=0.005
Boundary for River Rch & Prof#=Powel Creek Trib,Reach-1,6
Up Type=0
Dn Type=3
Dn Slope=0.005
Boundary for River Rch & Prof#=Powel Creek Trib,Reach-1,7
Up Type=0
Dn Type=3
Dn Slope=0.005

--- Powel Creek Tributary 1.g01 (geometry) ---

Geom Title=Existing Conditions

River Reach=Powel Creek Trib,Reach-1
Reach XY= 30
      2340629.00      7032360.00      2340671.75      7032413.33
      2340534.53      7032557.57      2340515.61      7032673.33
      2340431.46      7032754.54      2340284.65      7032761.98
      2340230.97      7032815.65      2340228.48      7033194.78
      2340130.22      7033470.51      2340126.74      7033654.06
      2339930.84      7034066.13      2339971.17      7034163.40
      2339879.90      7034270.59      2339882.00      7034351.65
      2339978.03      7034448.26      2339834.46      7034462.07
      2339786.47      7034506.38      2339921.55      7034653.97
      2339924.05      7034712.58      2339873.38      7034758.02
      2339684.00      7034765.00      2339665.64      7035023.35
      2339242.52      7035296.59      2339279.55      7035470.29
      2339242.76      7035546.77      2339082.41      7035417.77
      2338948.05      7035489.61      2339029.39      7035639.63
      2338939.41      7035699.78      2338929.00      7035760.00

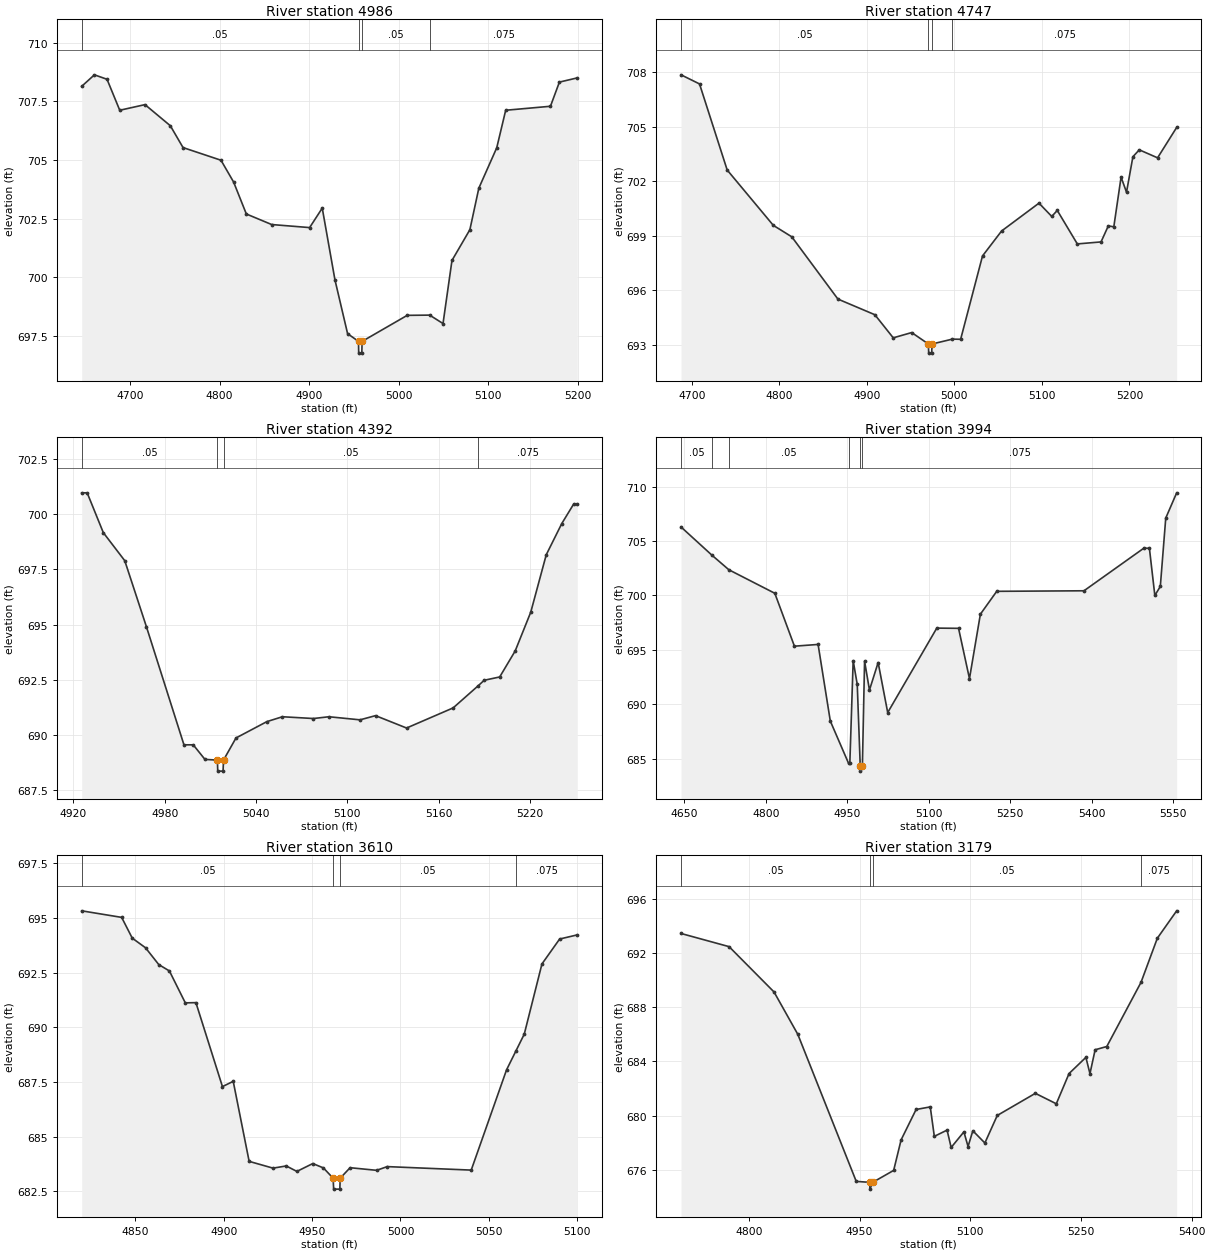
Type RM Length L Ch R = 1,4986,239,239,239
BEGIN DESCRIPTION:
Powel Creek Tributary 1 13.0
END DESCRIPTION:
XS GIS Cut Line= 3
      2340378.98      7032209.98      2340629.00      7032460.00
      2340829.01      7032460.00
#Sta/Elev= 30
  4646.0  708.14  4660.2  708.63  4674.3  708.44  4688.5  707.12  4716.7  707.36
  4745.0  706.46  4759.2  705.53  4801.6  704.99  4815.7  704.06  4829.9  702.70
  4858.2  702.25  4900.6  702.12  4914.7  702.95  4928.9  699.89  4943.0  697.60
  4955.2  697.27  4955.4  696.77  4958.9  696.77  4959.2  697.27  5009.6  698.38
  5034.7  698.39  5049.6  698.03  5059.6  700.72  5079.6  702.03  5089.6  703.80
  5109.6  705.52  5119.6  707.12  5169.6  707.29  5179.6  708.32  5199.6  708.50
#Mann=4,-1,0
  4646.0    0.05       0  4955.2    0.05       0  4959.2    0.05       0
  5034.7   0.075       0
Bank Sta=4955.2,4959.2
Exp/Cntr=0.3,0.1

Type RM Length L Ch R = 1,4747,355,355,355
BEGIN DESCRIPTION:
Powel Creek Tributary 1 12.0
END DESCRIPTION:
XS GIS Cut Line= 3
      2340229.00      7032560.00      2340529.00      7032660.00
      2340728.98      7032809.98
#Sta/Elev= 30
  4687.7  707.84  4708.8  707.34  4740.4  702.61  4793.1  699.57  4814.2  698.94
  4866.9  695.52  4909.1  694.66  4930.1  693.39  4951.2  693.68  4970.3  693.05
  4970.6  692.55  4974.1  692.55  4974.3  693.05  4997.7  693.32  5007.1  693.31
  5032.1  697.89  5053.9  699.26  5096.6  700.79  5111.2  700.06  5117.5  700.39
  5140.4  698.55  5167.5  698.66  5175.8  699.54  5182.1  699.49  5190.4  702.22
  5196.6  701.39  5203.9  703.34  5211.2  703.72  5232.1  703.28  5253.9  704.95
#Mann=4,-1,0
  4687.7    0.05       0  4970.3    0.07       0  4974.3    0.05       0
  4997.7   0.075       0
Bank Sta=4970.3,4974.3
Exp/Cntr=0.3,0.1

Type RM Length L Ch R = 1,4392,398,398,398
BEGIN DESCRIPTION:
Powel Creek Tributary 1 11.0
END DESCRIPTION:
XS GIS Cut Line= 3
      2340178.97      7032759.97      2340229.00      7032810.00
      2340478.99      7032860.00
#Sta/Elev= 30
  4925.5  700.96  4929.1  700.96  4939.7  699.16  4953.8  697.89  4968.0  694.91
  4992.7  689.56  4998.8  689.56  5006.5  688.90  5014.7  688.87  5014.9  688.37
  5018.4  688.37  5018.7  688.87  5026.9  689.87  5047.2  690.61  5057.4  690.83
  5077.8  690.75  5088.0  690.83  5108.4  690.69  5118.6  690.88  5139.0  690.32
  5169.6  691.23  5186.2  692.24  5190.0  692.48  5200.2  692.63  5210.4  693.81
  5220.6  695.56  5230.8  698.16  5241.0  699.57  5248.7  700.44  5251.2  700.44
#Mann=4,-1,0
  4925.5    0.05       0  5014.7    0.05       0  5018.7    0.05       0
  5186.2   0.075       0
Bank Sta=5014.7,5018.7
Exp/Cntr=0.3,0.1

Type RM Length L Ch R = 1,3994,384,384,384
BEGIN DESCRIPTION:
Powel Creek Tributary 1 10.0
END DESCRIPTION:
XS GIS Cut Line= 3
      2339929.03      7033010.02      2340229.00      7033210.00
      2340779.01      7033160.00
#Sta/Elev= 30
  4643.7  706.29  4700.8  703.69  4731.8  702.36  4816.4  700.20  4852.5  695.34
  4896.1  695.50  4918.6  688.46  4952.1  684.59  4954.6  684.64  4960.7  694.01
  4968.2  691.83  4973.7  684.36  4973.9  683.86  4977.7  684.36  4981.7  693.97
  4990.7  691.31  5006.7  693.84  5024.3  689.24  5114.7  697.00  5154.8  696.98
  5174.9  692.36  5195.0  698.28  5225.1  700.38  5385.8  700.43  5496.2  704.35
  5506.3  704.33  5516.3  700.00  5526.4  700.83  5536.4  707.11  5556.5  709.43
#Mann=6,-1,0
  4643.7    0.05       0  4700.8   0.075       0  4731.8    0.05       0
  4952.1   0.075       0  4973.7    0.07       0  4977.7   0.075       0
Bank Sta=4973.7,4977.7
Exp/Cntr=0.3,0.1

Type RM Length L Ch R = 1,3610,431,431,431
BEGIN DESCRIPTION:
Powel Creek Tributary 1 9.0
END DESCRIPTION:
XS GIS Cut Line= 3
      2339978.98      7033459.99      2340129.00      7033560.00
      2340229.00      7033560.00
#Sta/Elev= 30
  4819.7  695.33  4842.3  695.03  4848.3  694.08  4855.8  693.64  4863.3  692.87
  4869.3  692.58  4878.3  691.12  4884.3  691.13  4899.3  687.29  4905.4  687.53
  4914.4  683.87  4927.9  683.56  4935.4  683.66  4941.4  683.41  4950.4  683.77
  4956.4  683.57  4961.9  683.10  4962.2  682.60  4965.7  682.60  4965.9  683.10
  4971.5  683.58  4986.5  683.46  4992.5  683.63  5040.0  683.47  5060.0  688.06
  5065.4  688.94  5070.0  689.69  5080.0  692.90  5090.0  694.04  5100.0  694.23
#Mann=4,-1,0
  4819.7    0.05       0  4961.9   0.033       0  4965.9    0.05       0
  5065.4   0.075       0
Bank Sta=4961.9,4965.9
Exp/Cntr=0.3,0.1

Type RM Length L Ch R = 1,3179,140,140,140
BEGIN DESCRIPTION:
Powel Creek Tributary 1 8.0
END DESCRIPTION:
XS GIS Cut Line= 3
      2339704.71      7033899.87      2340023.97      7033952.33
      2340339.07      7033804.48
#Sta/Elev= 30
  4708.1  693.43  4773.2  692.46  4834.1  689.12  4866.3  686.00  4945.5  675.16
  4963.8  675.09  4964.0  674.59  4967.8  675.09  4996.2  675.97  5006.3  678.22
  5026.6  680.46  5045.8  680.65  5051.3  678.48  5068.6  678.94  5074.1  677.66
  5091.4  678.81  5097.0  677.73  5103.5  678.89  5119.8  677.99  5136.6  680.02
  5188.2  681.65  5216.6  680.88  5233.9  683.11  5256.7  684.30  5262.2  683.10
  5269.2  684.86  5285.0  685.10  5331.4  689.83  5353.5  693.08  5379.7  695.10
#Mann=4,-1,0
  4708.1    0.05       0  4963.8    0.05       0  4967.8    0.05       0
  5331.4   0.075       0
Bank Sta=4963.8,4967.8
Exp/Cntr=0.3,0.1

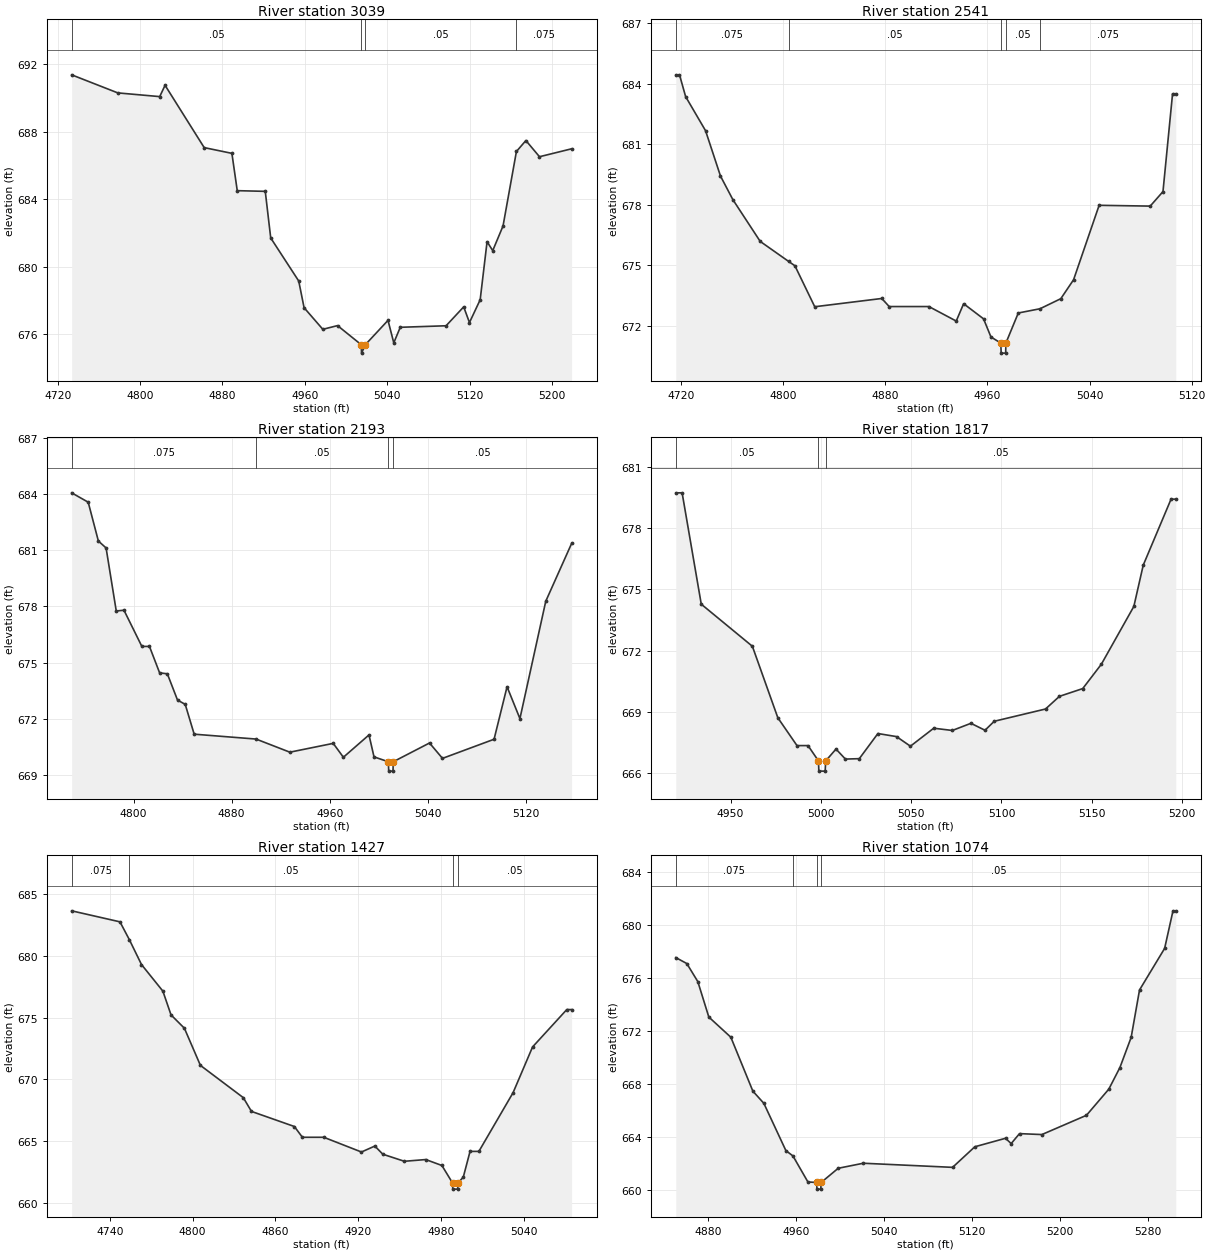
Type RM Length L Ch R = 1,3039,498,498,498
BEGIN DESCRIPTION:
Powel Creek Tributary 1 7.0
END DESCRIPTION:
XS GIS Cut Line= 3
      2339676.21      7033988.28      2339949.03      7034073.72
      2340129.03      7034160.01
#Sta/Elev= 30
  4733.6  691.37  4778.4  690.30  4819.1  690.08  4824.3  690.75  4862.3  687.06
  4889.2  686.72  4894.4  684.51  4921.6  684.47  4926.9  681.71  4954.1  679.16
  4959.3  677.58  4977.5  676.30  4991.8  676.52  5014.8  675.39  5015.1  674.89
  5018.8  675.39  5040.8  676.83  5046.4  675.50  5052.7  676.42  5097.2  676.51
  5114.3  677.63  5119.9  676.70  5130.3  678.05  5137.0  681.49  5142.5  680.96
  5152.5  682.42  5165.5  686.83  5174.7  687.48  5187.9  686.52  5219.1  686.99
#Mann=4,-1,0
  4733.6    0.05       0  5014.8    0.05       0  5018.8    0.05       0
  5165.5   0.075       0
Bank Sta=5014.8,5018.8
Exp/Cntr=0.3,0.1

Type RM Length L Ch R = 1,2541,348,348,348
BEGIN DESCRIPTION:
Powel Creek Tributary 1 6.0
END DESCRIPTION:
XS GIS Cut Line= 3
      2339729.03      7034310.02      2339979.00      7034460.00
      2340078.98      7034460.00
#Sta/Elev= 30
  4716.0  684.44  4718.9  684.44  4723.7  683.36  4739.3  681.67  4751.0  679.42
  4760.7  678.25  4782.1  676.18  4804.3  675.19  4809.3  674.97  4824.8  672.94
  4877.3  673.35  4883.1  672.95  4914.2  672.95  4935.6  672.23  4941.4  673.09
  4957.0  672.34  4962.8  671.44  4970.5  671.14  4970.8  670.64  4974.3  670.64
  4974.5  671.14  4984.2  672.63  5001.2  672.84  5017.5  673.34  5027.5  674.28
  5047.5  677.97  5087.5  677.93  5097.5  678.65  5105.0  683.50  5107.5  683.50
#Mann=5,-1,0
  4716.0   0.075       0  4804.3    0.05       0  4970.5   0.033       0
  4974.5    0.05       0  5001.2   0.075       0
Bank Sta=4970.5,4974.5
Exp/Cntr=0.3,0.1

Type RM Length L Ch R = 1,2193,376,376,376
BEGIN DESCRIPTION:
Powel Creek Tributary 1 5.0
END DESCRIPTION:
XS GIS Cut Line= 3
      2339679.03      7034460.02      2339879.00      7034610.00
      2340029.02      7034660.01
#Sta/Elev= 30
  4749.4  684.06  4762.9  683.56  4771.2  681.49  4777.5  681.12  4785.8  677.76
  4792.1  677.80  4806.7  675.87  4812.9  675.87  4821.2  674.46  4827.5  674.41
  4835.8  673.01  4842.1  672.78  4849.4  671.19  4899.9  670.93  4927.5  670.23
  4962.9  670.70  4971.2  669.96  4992.1  671.15  4996.2  669.98  5007.9  669.72
  5008.2  669.22  5011.7  669.22  5011.9  669.72  5041.5  670.72  5052.1  669.90
  5094.2  670.92  5104.8  673.72  5115.3  672.02  5136.4  678.28  5157.5  681.36
#Mann=4,-1,0
  4749.4   0.075       0  4899.9    0.05       0  5007.9   0.033       0
  5011.9    0.05       0
Bank Sta=5007.9,5011.9
Exp/Cntr=0.3,0.1

Type RM Length L Ch R = 1,1817,390,390,390
BEGIN DESCRIPTION:
Powel Creek Tributary 1 4.0
END DESCRIPTION:
XS GIS Cut Line= 3
      2339629.03      7034710.03      2339679.00      7034760.00
      2339878.98      7034809.99
#Sta/Elev= 30
  4919.7  679.72  4923.2  679.72  4933.8  674.27  4962.1  672.21  4976.2  668.71
  4986.8  667.35  4992.9  667.35  4998.7  666.60  4998.9  666.10  5002.4  666.10
  5002.7  666.60  5008.4  667.18  5013.6  666.69  5021.3  666.71  5031.6  667.94
  5041.9  667.79  5049.6  667.32  5062.5  668.20  5072.8  668.09  5083.1  668.44
  5090.9  668.10  5096.0  668.54  5124.4  669.14  5132.1  669.76  5145.0  670.14
  5155.3  671.33  5173.3  674.16  5178.5  676.18  5193.9  679.41  5196.5  679.41
#Mann=3,-1,0
  4919.7    0.05       0  4998.7    0.05       0  5002.7    0.05       0
Bank Sta=4998.7,5002.7
Exp/Cntr=0.3,0.1

Type RM Length L Ch R = 1,1427,353,353,353
BEGIN DESCRIPTION:
Powel Creek Tributary 1 3.0
END DESCRIPTION:
XS GIS Cut Line= 3
      2339428.98      7034859.96      2339579.00      7035110.00
      2339629.00      7035160.00
#Sta/Elev= 30
  4712.4  683.63  4747.4  682.74  4754.2  681.30  4763.0  679.29  4778.5  677.14
  4784.4  675.22  4794.1  674.14  4805.7  671.14  4836.8  668.53  4842.7  667.42
  4873.8  666.20  4879.6  665.33  4895.1  665.33  4922.4  664.14  4932.1  664.62
  4937.9  663.96  4953.5  663.39  4969.0  663.53  4980.7  663.05  4988.4  661.64
  4988.6  661.14  4992.1  661.14  4992.4  661.64  4996.2  662.11  5001.1  664.19
  5007.5  664.19  5032.3  668.94  5046.4  672.63  5071.2  675.65  5074.7  675.65
#Mann=4,-1,0
  4712.4   0.075       0  4754.2    0.05       0  4988.4   0.033       0
  4992.4    0.05       0
Bank Sta=4988.4,4992.4
Exp/Cntr=0.3,0.1

Type RM Length L Ch R = 1,1074,333,333,333
BEGIN DESCRIPTION:
Powel Creek Tributary 1 2.0
END DESCRIPTION:
XS GIS Cut Line= 3
      2339279.00      7035110.02      2339279.00      7035260.00
      2339578.98      7035310.00
#Sta/Elev= 30
  4850.8  677.53  4860.8  677.08  4870.8  675.72  4880.8  673.05  4900.8  671.53
  4920.8  667.47  4930.8  666.55  4950.8  662.99  4957.2  662.59  4970.8  660.63
  4978.8  660.59  4979.0  660.09  4982.5  660.09  4982.8  660.59  4998.3  661.66
  5021.1  662.04  5102.2  661.73  5122.4  663.28  5150.3  663.92  5155.4  663.52
  5163.0  664.27  5183.3  664.20  5223.8  665.65  5244.1  667.62  5254.2  669.25
  5264.4  671.52  5272.0  675.09  5294.8  678.22  5302.4  681.05  5304.9  681.05
#Mann=4,-1,0
  4850.8   0.075       0  4957.2    0.05       0  4978.8   0.033       0
  4982.8    0.05       0
Bank Sta=4978.8,4982.8
Exp/Cntr=0.3,0.1

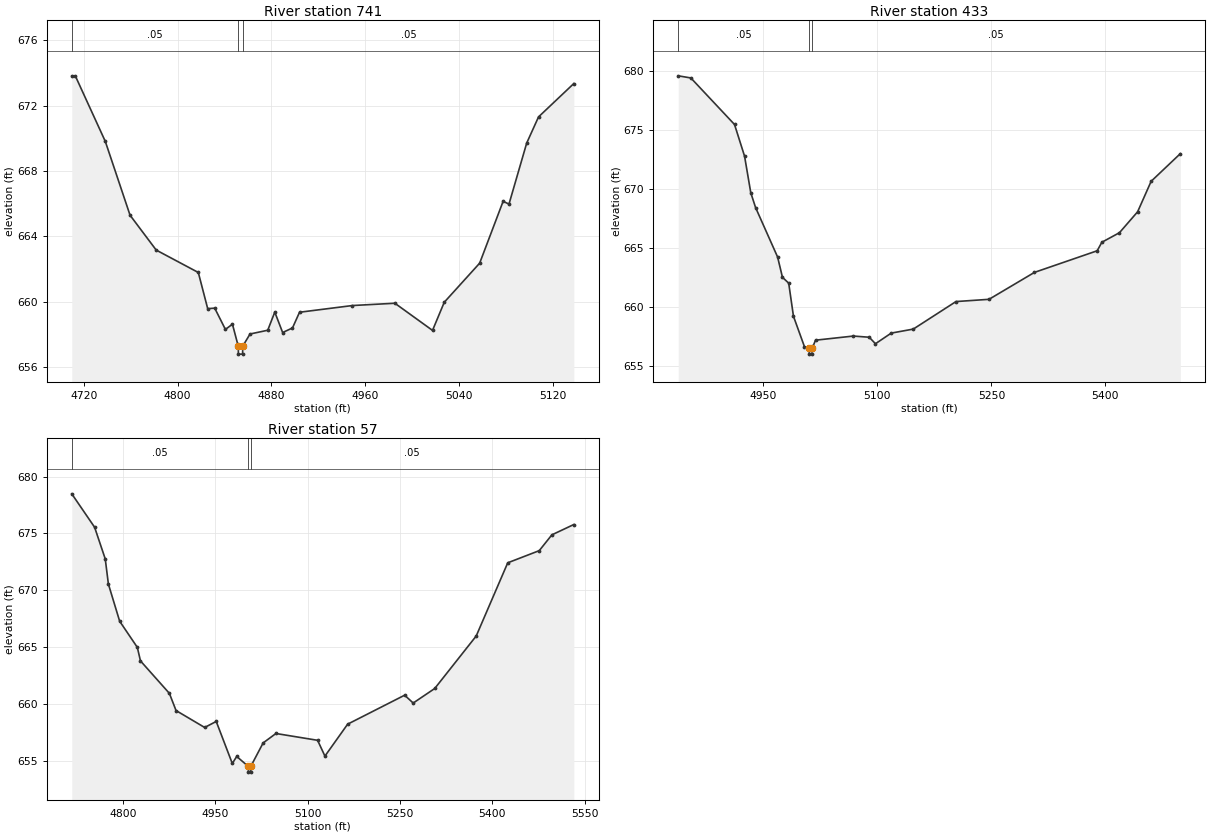
Type RM Length L Ch R = 1,741,308,308,308
BEGIN DESCRIPTION:
Powel Creek Tributary 1 1.0
END DESCRIPTION:
XS GIS Cut Line= 3
      2339078.97      7035309.96      2339235.62      7035547.00
      2339379.01      7035560.00
#Sta/Elev= 30
  4709.8  673.82  4712.8  673.82  4738.4  669.81  4759.5  665.30  4781.8  663.17
  4817.7  661.80  4825.7  659.59  4831.7  659.62  4840.8  658.32  4846.8  658.64
  4851.7  657.31  4851.9  656.81  4855.4  656.81  4855.7  657.31  4861.8  658.04
  4876.9  658.27  4882.9  659.38  4889.6  658.13  4898.0  658.41  4904.0  659.37
  4949.1  659.78  4985.3  659.92  5017.4  658.26  5027.4  659.98  5057.6  662.37
  5077.6  666.15  5082.6  665.98  5097.7  669.71  5107.8  671.31  5137.9  673.35
#Mann=3,-1,0
  4709.8    0.05       0  4851.7   0.033       0  4855.7    0.05       0
Bank Sta=4851.7,4855.7
Exp/Cntr=0.3,0.1

Type RM Length L Ch R = 1,433,376,376,376
BEGIN DESCRIPTION:
Powel Creek Tributary 1 0.5
END DESCRIPTION:
XS GIS Cut Line= 3
      2338904.38      7035331.17      2339175.67      7035684.89
      2339374.47      7035767.10
#Sta/Elev= 30
  4837.8  679.58  4854.4  679.40  4911.9  675.46  4925.1  672.78  4933.3  669.68
  4939.6  668.43  4968.6  664.24  4975.0  662.52  4983.2  662.03  4989.5  659.22
  5004.0  656.64  5010.2  656.52  5010.4  656.02  5013.9  656.02  5014.2  656.52
  5018.5  657.20  5068.3  657.55  5089.2  657.45  5097.4  656.90  5118.2  657.80
  5147.2  658.14  5203.4  660.47  5246.9  660.66  5306.7  662.94  5389.3  664.77
  5395.4  665.49  5418.6  666.30  5442.5  668.07  5460.3  670.65  5498.7  672.99
#Mann=3,-1,0
  4837.8    0.05       0  5010.2   0.033       0  5014.2    0.05       0
Bank Sta=5010.2,5014.2
Exp/Cntr=0.3,0.1

Type RM Length L Ch R = 1,57,0,0,0
BEGIN DESCRIPTION:
Powel Creek Tributary 1 0.3
END DESCRIPTION:
XS GIS Cut Line= 4
      2338853.43      7035443.56      2338896.90      7035671.40
      2338980.83      7035741.84      2339443.93      7035843.75
#Sta/Elev= 30
  4716.9  678.49  4754.0  675.55  4771.3  672.76  4776.4  670.55  4794.7  667.28
  4823.4  664.98  4828.5  663.79  4875.5  660.93  4886.3  659.42  4932.8  657.93
  4951.6  658.46  4977.7  654.76  4984.9  655.38  5003.7  654.50  5004.0  654.00
  5007.5  654.00  5007.7  654.50  5027.8  656.57  5048.6  657.40  5116.3  656.80
  5128.2  655.41  5165.1  658.22  5257.7  660.77  5271.6  660.08  5306.6  661.36
  5374.0  665.98  5425.2  672.42  5476.4  673.49  5496.9  674.88  5532.6  675.79
#Mann=3,-1,0
  4716.9    0.05       0  5003.7   0.033       0  5007.7    0.05       0
Bank Sta=5003.7,5007.7
Exp/Cntr=0.3,0.1

Chan Stop Cuts=-1