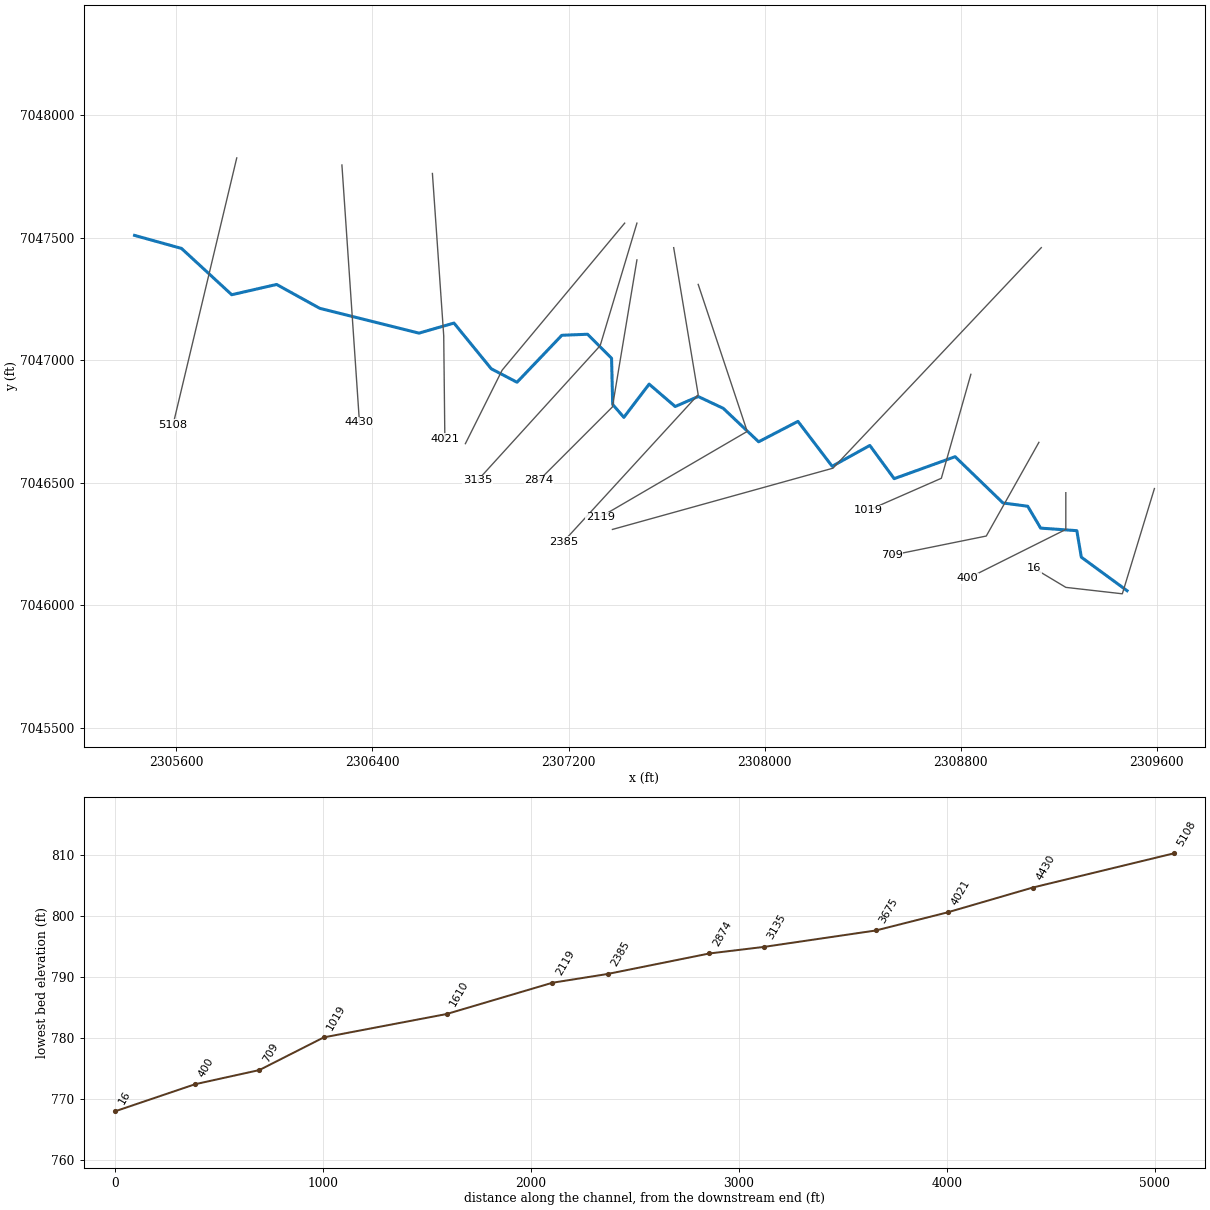
--- S104.prj (project) ---

Proj Title=S104 Base Level Engineering
Current Plan=p01
Default Exp/Contr=0.3,0.1
English Units
Geom File=g01
Flow File=f01
Plan File=p01
BEGIN DESCRIPTION:
S104
END DESCRIPTION:

--- S104.p01 (plan) ---

Plan Title=Multiple Run
Short Identifier=Multiple
Geom File=g01
Flow File=f01
Subcritical Flow
K Sum by GR= 0
Std Step Tol= 0.01
Critical Tol= 0.01
Num of Std Step Trials= 20
Max Error Tol= 0.3
Flow Tol Ratio= 0.001
Split Flow NTrial= 30
Split Flow Tol= 0.02
Split Flow Ratio= 0.02
Log Output Level= 0
Friction Slope Method= 1
Unsteady Friction Slope Method= 2
Unsteady Bridges Friction Slope Method= 1
Parabolic Critical Depth
Global Vel Dist=  1 , 1 , 1
Global Log Level= 0
CheckData=True
Encroach Param= -1, 0, 0, 0
BEGIN DESCRIPTION:
Multiple Run
END DESCRIPTION:

--- S104.f01 (steady flow) ---

Flow Title=Multiple
Number of Profiles=7
Profile Names=10-year,25-year,50-year,1pct_min,100-year,1pct_plu,500-year
River Rch & RM= S104,Reach-1,5108
     219     280     327     190     379     757     509
River Rch & RM= S104,Reach-1,4430
     246     317     372     217     433     865     587
River Rch & RM= S104,Reach-1,3675
     299     394     470     279     557    1110     783
River Rch & RM= S104,Reach-1,2385
     576     786     958     579    1160    2300    1680
River Rch & RM= S104,Reach-1,709
     604     827    1010     612    1220    2440    1780
River Rch & RM= S104,Reach-1,16
    1200    1700    2130    1310    2620    5220    3970
Boundary for River Rch & Prof#=S104,Reach-1,1
Up Type=0
Dn Type=3
Dn Slope=0.005
Boundary for River Rch & Prof#=S104,Reach-1,2
Up Type=0
Dn Type=3
Dn Slope=0.005
Boundary for River Rch & Prof#=S104,Reach-1,3
Up Type=0
Dn Type=3
Dn Slope=0.005
Boundary for River Rch & Prof#=S104,Reach-1,4
Up Type=0
Dn Type=3
Dn Slope=0.005
Boundary for River Rch & Prof#=S104,Reach-1,5
Up Type=0
Dn Type=3
Dn Slope=0.005
Boundary for River Rch & Prof#=S104,Reach-1,6
Up Type=0
Dn Type=3
Dn Slope=0.005
Boundary for River Rch & Prof#=S104,Reach-1,7
Up Type=0
Dn Type=3
Dn Slope=0.005

--- S104.g01 (geometry) ---

Geom Title=Existing Conditions

River Reach=S104,Reach-1
Reach XY= 30
      2305429.00      7047510.00      2305620.66      7047456.82
      2305825.59      7047267.81      2306008.70      7047309.73
      2306184.94      7047212.27      2306589.55      7047111.11
      2306732.42      7047152.20      2306884.61      7046965.59
      2306989.69      7046910.69      2307172.55      7047102.36
      2307277.51      7047106.55      2307375.47      7047008.55
      2307380.06      7046820.09      2307425.56      7046767.39
      2307528.78      7046903.00      2307635.05      7046811.67
      2307729.00      7046852.44      2307831.29      7046804.19
      2307975.59      7046667.77      2308136.01      7046751.01
      2308275.58      7046567.76      2308429.30      7046652.80
      2308528.69      7046517.23      2308777.37      7046606.87
      2308972.88      7046417.88      2309073.51      7046404.71
      2309126.33      7046315.41      2309273.92      7046304.96
      2309292.42      7046196.73      2309479.00      7046060.00

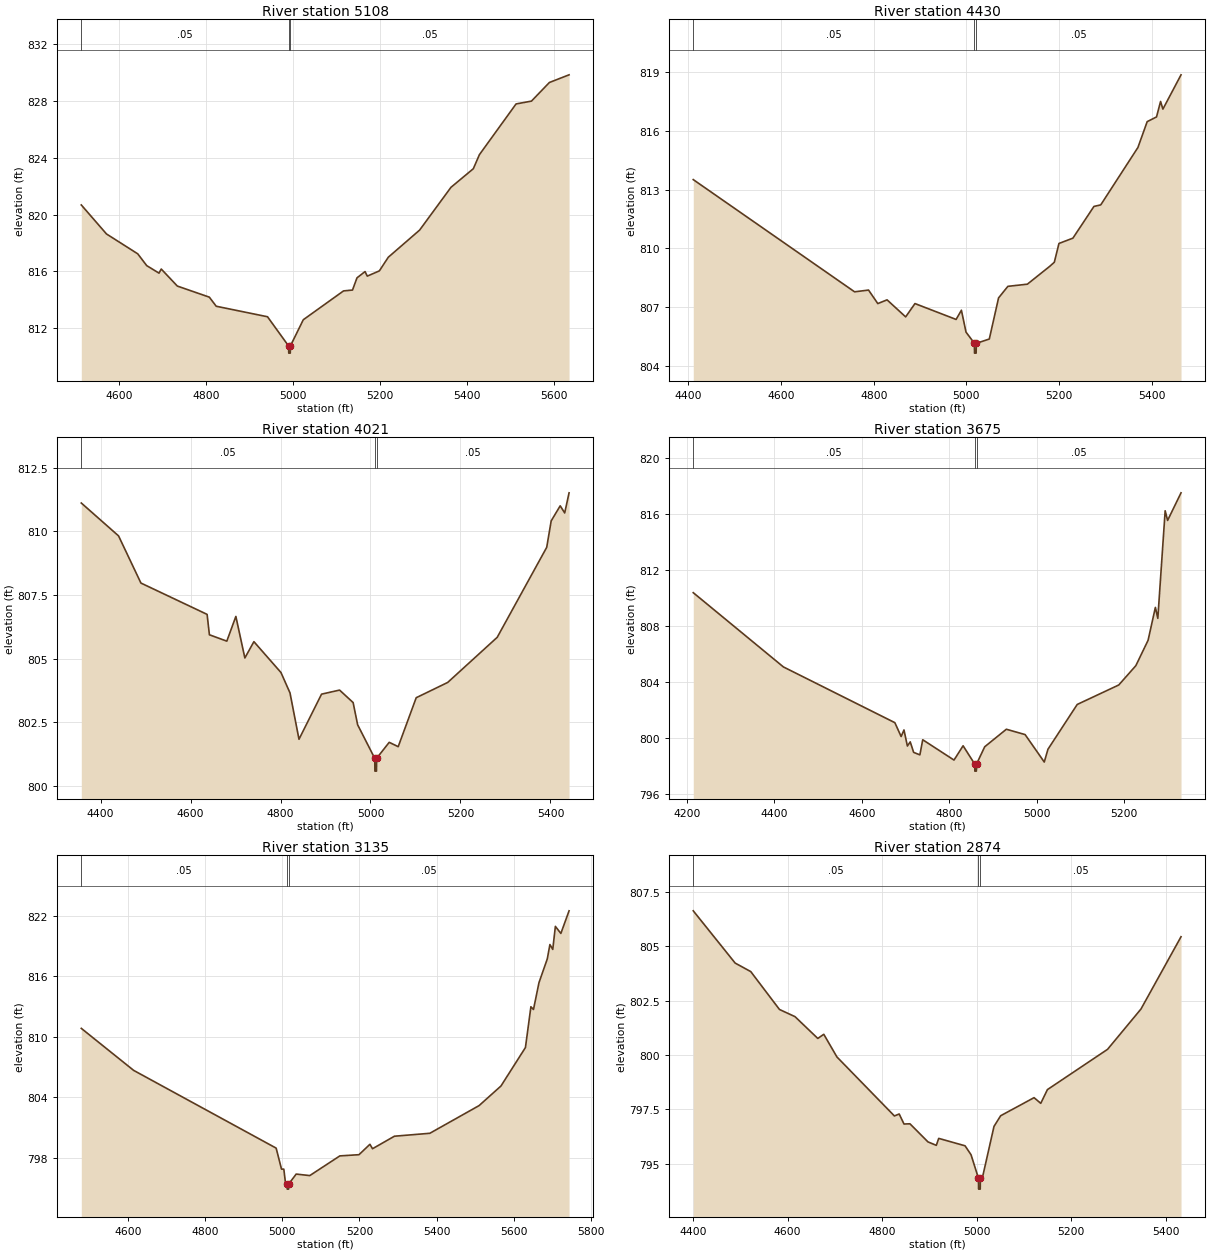
Type RM Length L Ch R = 1,5108,678,678,678
BEGIN DESCRIPTION:
S 104 10.0
END DESCRIPTION:
XS GIS Cut Line= 2
      2305846.08      7047826.17      2305585.86      7046736.00
#Sta/Elev= 30
  4513.5  820.68  4571.3  818.64  4643.2  817.24  4663.8  816.41  4692.1  815.88
  4697.2  816.17  4734.2  814.97  4807.7  814.19  4823.5  813.55  4941.4  812.81
  4989.9  810.75  4990.2  810.25  4993.7  810.25  4993.9  810.75  5023.6  812.60
  5116.1  814.63  5136.7  814.69  5147.0  815.55  5165.5  815.99  5170.6  815.67
  5198.4  816.04  5218.9  817.00  5290.9  818.91  5362.9  821.92  5414.3  823.23
  5428.3  824.22  5512.5  827.79  5547.9  827.99  5589.1  829.30  5634.3  829.84
#Mann=3,-1,0
  4513.5    0.05       0  4989.9   0.033       0  4993.9    0.05       0
Bank Sta=4989.9,4993.9
Exp/Cntr=0.3,0.1

Type RM Length L Ch R = 1,4430,409,409,409
BEGIN DESCRIPTION:
S 104 9.0
END DESCRIPTION:
XS GIS Cut Line= 2
      2306275.20      7047797.28      2306346.75      7046747.21
#Sta/Elev= 30
  4410.6  813.51  4758.7  807.78  4788.8  807.87  4808.8  807.18  4828.8  807.37
  4868.9  806.50  4889.0  807.18  4977.8  806.37  4989.2  806.84  4999.2  805.72
  5017.3  805.15  5017.5  804.65  5021.0  804.65  5021.3  805.15  5049.4  805.37
  5069.4  807.47  5089.5  808.06  5131.5  808.17  5179.7  809.08  5189.7  809.29
  5199.7  810.25  5229.8  810.52  5275.2  812.14  5289.9  812.22  5370.1  815.15
  5390.1  816.47  5410.2  816.71  5419.0  817.50  5424.0  817.11  5463.1  818.86
#Mann=3,-1,0
  4410.6    0.05       0  5017.3   0.033       0  5021.3    0.05       0
Bank Sta=5017.3,5021.3
Exp/Cntr=0.3,0.1

Type RM Length L Ch R = 1,4021,346,346,346
BEGIN DESCRIPTION:
S104 8.0
END DESCRIPTION:
XS GIS Cut Line= 3
      2306644.47      7047762.64      2306690.62      7047100.31
      2306695.24      7046680.27
#Sta/Elev= 30
  4357.3  811.11  4440.1  809.82  4489.8  807.97  4636.9  806.74  4642.0  805.94
  4680.7  805.69  4700.8  806.66  4720.8  805.03  4740.9  805.67  4801.0  804.46
  4821.1  803.66  4841.1  801.84  4891.2  803.61  4931.3  803.77  4961.4  803.28
  4971.4  802.41  5009.5  801.09  5009.8  800.59  5013.3  800.59  5013.5  801.09
  5041.6  801.72  5061.6  801.55  5101.6  803.47  5171.6  804.07  5281.6  805.84
  5391.6  809.37  5401.6  810.41  5421.6  811.00  5431.6  810.72  5441.3  811.51
#Mann=3,-1,0
  4357.3    0.05       0  5009.5   0.033       0  5013.5    0.05       0
Bank Sta=5009.5,5013.5
Exp/Cntr=0.3,0.1

Type RM Length L Ch R = 1,3675,540,540,540
BEGIN DESCRIPTION:
S104 7.0
END DESCRIPTION:
XS GIS Cut Line= 3
      2307428.99      7047559.99      2306929.00      7046960.00
      2306779.01      7046660.02
#Sta/Elev= 30
  4214.1  810.35  4420.4  805.05  4675.5  801.07  4689.9  800.08  4696.4  800.55
  4704.2  799.40  4710.7  799.70  4718.5  798.95  4732.8  798.77  4739.3  799.85
  4810.9  798.40  4831.7  799.42  4858.4  798.11  4858.6  797.61  4862.1  797.61
  4862.4  798.11  4881.2  799.35  4930.7  800.60  4973.6  800.22  5017.5  798.26
  5025.9  799.17  5092.9  802.37  5188.0  803.76  5227.1  805.14  5255.1  806.95
  5271.8  809.30  5277.4  808.52  5294.2  816.20  5299.8  815.51  5330.5  817.48
#Mann=3,-1,0
  4214.1    0.05       0  4858.4   0.033       0  4862.4    0.05       0
Bank Sta=4858.4,4862.4
Exp/Cntr=0.3,0.1

Type RM Length L Ch R = 1,3135,261,261,261
BEGIN DESCRIPTION:
S104 6.0
END DESCRIPTION:
XS GIS Cut Line= 3
      2307479.01      7047560.04      2307329.00      7047060.00
      2306828.97      7046509.97
#Sta/Elev= 30
  4478.5  810.83  4614.3  806.67  4984.0  798.97  4997.9  796.89  5003.9  796.89
  5007.7  795.68  5012.4  795.41  5012.7  794.91  5016.2  794.91  5016.4  795.41
  5036.0  796.40  5071.2  796.25  5149.2  798.20  5198.9  798.32  5227.3  799.35
  5234.0  798.91  5290.8  800.15  5382.7  800.44  5510.4  803.18  5567.2  805.12
  5630.7  808.93  5644.9  812.97  5651.6  812.70  5665.8  815.35  5687.4  817.71
  5694.2  819.13  5701.6  818.65  5708.4  820.93  5722.6  820.23  5743.9  822.47
#Mann=3,-1,0
  4478.5    0.05       0  5012.4   0.033       0  5016.4    0.05       0
Bank Sta=5012.4,5016.4
Exp/Cntr=0.3,0.1

Type RM Length L Ch R = 1,2874,489,489,489
BEGIN DESCRIPTION:
S104 5.0
END DESCRIPTION:
XS GIS Cut Line= 3
      2307479.00      7047410.00      2307379.00      7046810.00
      2307079.03      7046510.03
#Sta/Elev= 30
  4400.3  806.62  4489.0  804.22  4522.0  803.83  4582.8  802.09  4615.7  801.76
  4663.9  800.76  4676.6  800.95  4704.4  799.91  4826.1  797.20  4836.2  797.29
  4846.4  796.83  4859.0  796.84  4897.1  796.01  4914.8  795.85  4919.9  796.17
  4975.6  795.83  4988.3  795.42  5004.0  794.34  5004.3  793.84  5007.8  793.84
  5008.0  794.34  5012.1  794.34  5036.9  796.72  5051.0  797.21  5121.7  798.04
  5135.9  797.78  5150.0  798.41  5277.3  800.26  5348.0  802.11  5432.8  805.43
#Mann=3,-1,0
  4400.3    0.05       0  5004.0   0.033       0  5008.0    0.05       0
Bank Sta=5004,5008
Exp/Cntr=0.3,0.1

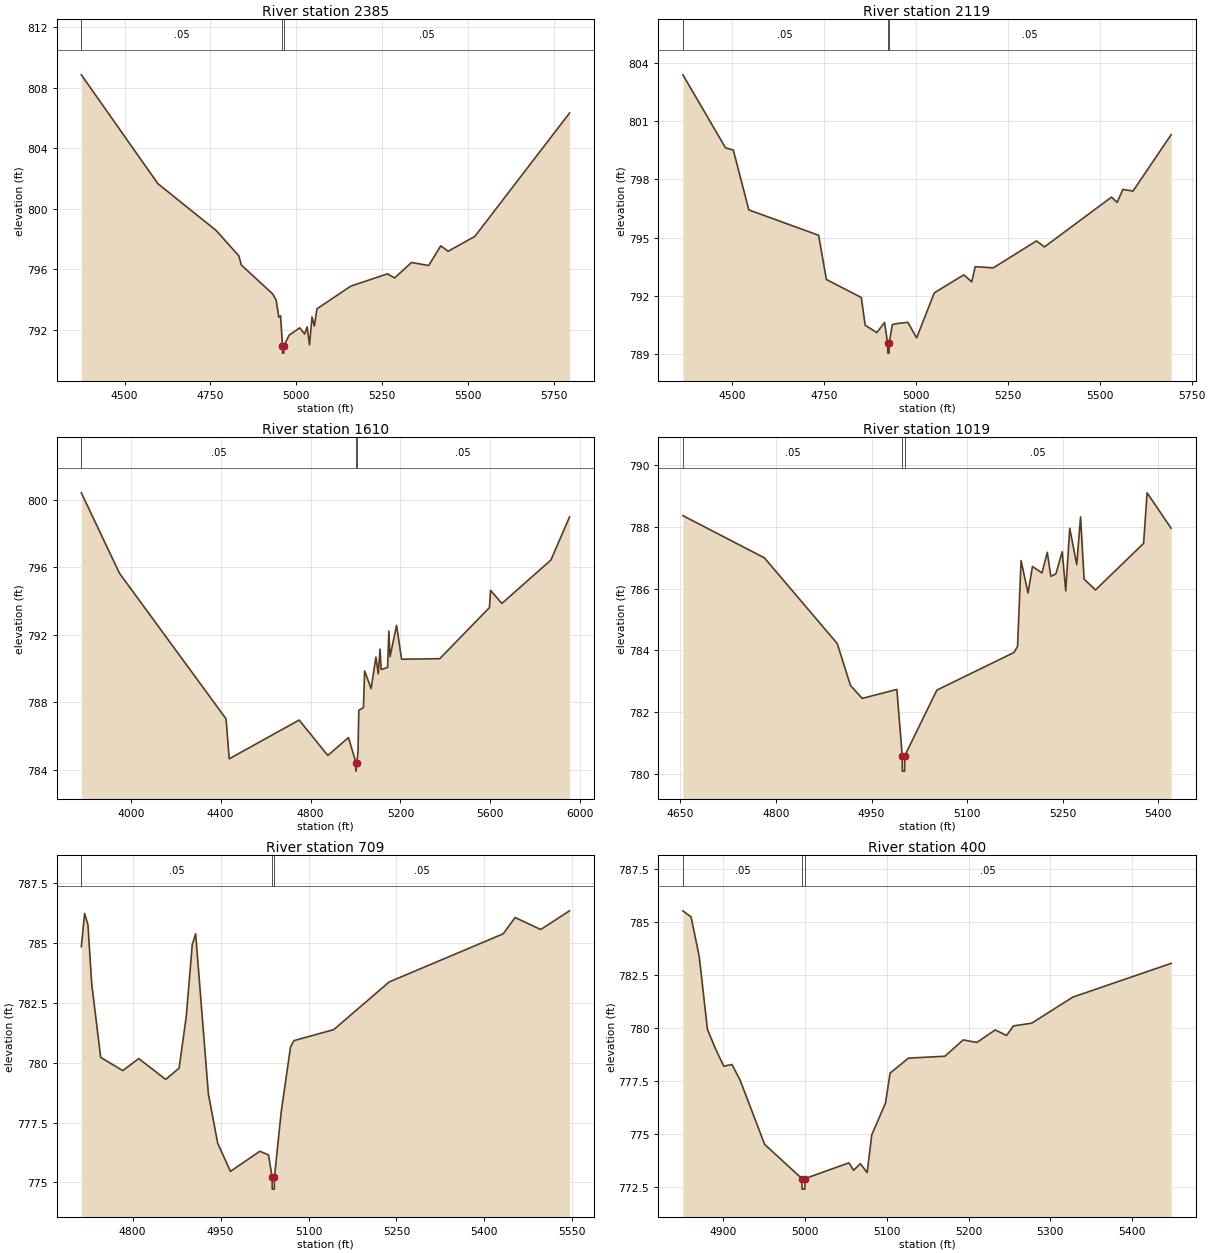
Type RM Length L Ch R = 1,2385,266,266,266
BEGIN DESCRIPTION:
S104 4.0
END DESCRIPTION:
XS GIS Cut Line= 3
      2307629.00      7047460.00      2307729.00      7046860.00
      2307179.01      7046260.01
#Sta/Elev= 30
  4374.0  808.84  4597.0  801.66  4766.8  798.57  4832.7  796.90  4840.3  796.29
  4931.6  794.38  4941.7  793.97  4949.3  792.85  4954.4  792.94  4960.0  790.98
  4960.3  790.48  4963.8  790.48  4964.0  790.98  4979.7  791.67  5010.3  792.15
  5024.5  791.74  5031.9  792.21  5038.7  791.03  5046.1  792.87  5052.9  792.26
  5060.3  793.40  5158.9  794.90  5265.6  795.71  5286.6  795.44  5335.9  796.46
  5385.9  796.26  5421.0  797.56  5442.6  797.20  5520.3  798.18  5796.2  806.32
#Mann=3,-1,0
  4374.0    0.05       0  4960.0   0.033       0  4964.0    0.05       0
Bank Sta=4960,4964
Exp/Cntr=0.3,0.1

Type RM Length L Ch R = 1,2119,509,509,509
BEGIN DESCRIPTION:
S104 3.0
END DESCRIPTION:
XS GIS Cut Line= 3
      2307729.01      7047309.97      2307929.00      7046710.00
      2307329.04      7046360.02
#Sta/Elev= 30
  4367.2  803.40  4483.1  799.63  4504.2  799.52  4546.4  796.43  4736.1  795.12
  4757.2  792.84  4852.1  791.91  4862.6  790.48  4894.2  790.10  4915.3  790.62
  4923.8  789.54  4924.1  789.04  4927.6  789.04  4927.8  789.54  4936.4  790.51
  4946.9  790.56  4978.5  790.63  5002.5  789.83  5050.5  792.15  5130.7  793.08
  5152.2  792.72  5161.7  793.50  5210.9  793.44  5328.3  794.83  5349.8  794.52
  5532.2  797.09  5547.5  796.82  5563.2  797.49  5590.5  797.40  5694.2  800.31
#Mann=3,-1,0
  4367.2    0.05       0  4923.8   0.033       0  4927.8    0.05       0
Bank Sta=4923.8,4927.8
Exp/Cntr=0.3,0.1

Type RM Length L Ch R = 1,1610,591,591,591
BEGIN DESCRIPTION:
S104 2.0
END DESCRIPTION:
XS GIS Cut Line= 3
      2309129.02      7047460.02      2308279.00      7046560.00
      2307379.04      7046310.01
#Sta/Elev= 30
  3780.3  800.42  3950.0  795.65  4424.2  787.01  4438.3  784.64  4749.4  786.94
  4876.9  784.84  4968.7  785.90  5002.3  784.41  5002.6  783.91  5006.3  784.41
  5011.2  785.09  5014.8  787.52  5035.4  787.68  5040.6  789.85  5069.6  788.81
  5090.9  790.68  5101.3  789.68  5109.1  791.15  5114.3  789.94  5142.8  790.06
  5148.5  792.22  5153.7  790.70  5182.8  792.56  5205.1  790.55  5374.8  790.58
  5595.8  793.61  5601.0  794.63  5651.4  793.86  5869.3  796.43  5952.3  798.99
#Mann=3,-1,0
  3780.3    0.05       0  5002.3   0.033       0  5006.3    0.05       0
Bank Sta=5002.3,5006.3
Exp/Cntr=0.3,0.1

Type RM Length L Ch R = 1,1019,310,310,310
BEGIN DESCRIPTION:
S104 1.5
END DESCRIPTION:
XS GIS Cut Line= 3
      2308841.60      7046943.03      2308721.14      7046518.79
      2308423.33      7046388.17
#Sta/Elev= 30
  4654.0  788.37  4781.9  787.00  4896.2  784.22  4917.0  782.86  4935.4  782.44
  4989.8  782.73  4998.2  780.58  4998.4  780.08  5001.9  780.08  5002.2  780.58
  5052.6  782.71  5173.7  783.93  5179.2  784.13  5184.7  786.91  5195.6  785.86
  5202.6  786.72  5217.5  786.51  5225.9  787.18  5231.4  786.40  5239.3  786.48
  5249.3  787.20  5254.8  785.93  5261.1  787.96  5272.1  786.78  5278.1  788.33
  5283.6  786.31  5301.5  785.96  5377.0  787.47  5382.5  789.11  5420.2  787.96
#Mann=3,-1,0
  4654.0    0.05       0  4998.2   0.033       0  5002.2    0.05       0
Bank Sta=4998.2,5002.2
Exp/Cntr=0.3,0.1

Type RM Length L Ch R = 1,709,309,309,309
BEGIN DESCRIPTION:
S104 1.2
END DESCRIPTION:
XS GIS Cut Line= 3
      2309119.22      7046665.46      2308904.46      7046283.08
      2308518.07      7046204.76
#Sta/Elev= 30
  4712.4  784.84  4718.0  786.23  4723.7  785.76  4730.1  783.30  4745.4  780.22
  4783.0  779.67  4810.4  780.17  4856.3  779.30  4879.2  779.77  4891.4  781.93
  4901.6  784.93  4907.4  785.38  4929.1  778.70  4945.0  776.64  4966.7  775.46
  5016.9  776.30  5031.7  776.15  5037.8  775.22  5038.1  774.72  5041.6  774.72
  5041.8  775.22  5053.4  777.95  5069.3  780.66  5075.1  780.92  5143.0  781.38
  5237.5  783.37  5432.0  785.38  5452.4  786.06  5496.0  785.56  5545.2  786.34
#Mann=3,-1,0
  4712.4    0.05       0  5037.8   0.033       0  5041.8    0.05       0
Bank Sta=5037.8,5041.8
Exp/Cntr=0.3,0.1

Type RM Length L Ch R = 1,400,384,384,384
BEGIN DESCRIPTION:
S104 1.0
END DESCRIPTION:
XS GIS Cut Line= 3
      2309229.00      7046459.98      2309229.00      7046310.00
      2308828.99      7046110.00
#Sta/Elev= 30
  4850.5  785.53  4860.5  785.24  4870.5  783.37  4880.5  779.94  4890.5  779.01
  4900.5  778.20  4910.5  778.28  4920.5  777.54  4950.5  774.51  4996.0  772.90
  4996.2  772.40  4999.7  772.40  5000.0  772.90  5053.6  773.64  5059.2  773.29
  5067.6  773.60  5075.9  773.18  5081.5  774.96  5098.3  776.46  5103.9  777.87
  5126.3  778.58  5171.0  778.67  5193.3  779.44  5210.1  779.32  5232.5  779.91
  5246.4  779.65  5254.8  780.10  5277.2  780.23  5327.5  781.46  5447.7  783.05
#Mann=3,-1,0
  4850.5    0.05       0  4996.0   0.033       0  5000.0    0.05       0
Bank Sta=4996,5000
Exp/Cntr=0.3,0.1

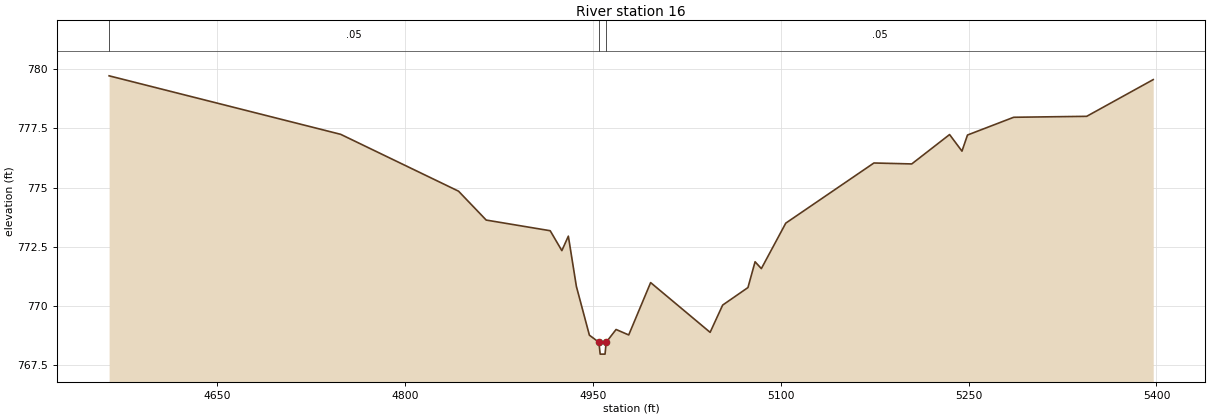
Type RM Length L Ch R = 1,16,0,0,0
BEGIN DESCRIPTION:
S104 0.5
END DESCRIPTION:
XS GIS Cut Line= 4
      2309590.61      7046476.88      2309459.67      7046047.38
      2309229.20      7046073.57      2309098.23      7046152.15
#Sta/Elev= 30
  4563.7  779.72  4748.6  777.25  4842.7  774.85  4864.8  773.63  4915.9  773.18
  4925.2  772.34  4930.4  772.95  4936.8  770.83  4947.2  768.77  4954.8  768.47
  4955.8  767.97  4959.7  767.97  4960.6  768.47  4968.5  769.01  4978.6  768.78
  4996.1  770.99  5043.6  768.89  5053.6  770.04  5073.8  770.78  5079.5  771.87
  5084.5  771.58  5104.0  773.50  5174.4  776.04  5204.6  776.00  5234.8  777.24
  5244.7  776.54  5249.1  777.22  5286.0  777.97  5344.3  778.01  5397.4  779.56
#Mann=3,-1,0
  4563.7    0.05       0  4954.8   0.033       0  4960.6    0.05       0
Bank Sta=4954.8,4960.6
Exp/Cntr=0.3,0.1

Chan Stop Cuts=-1