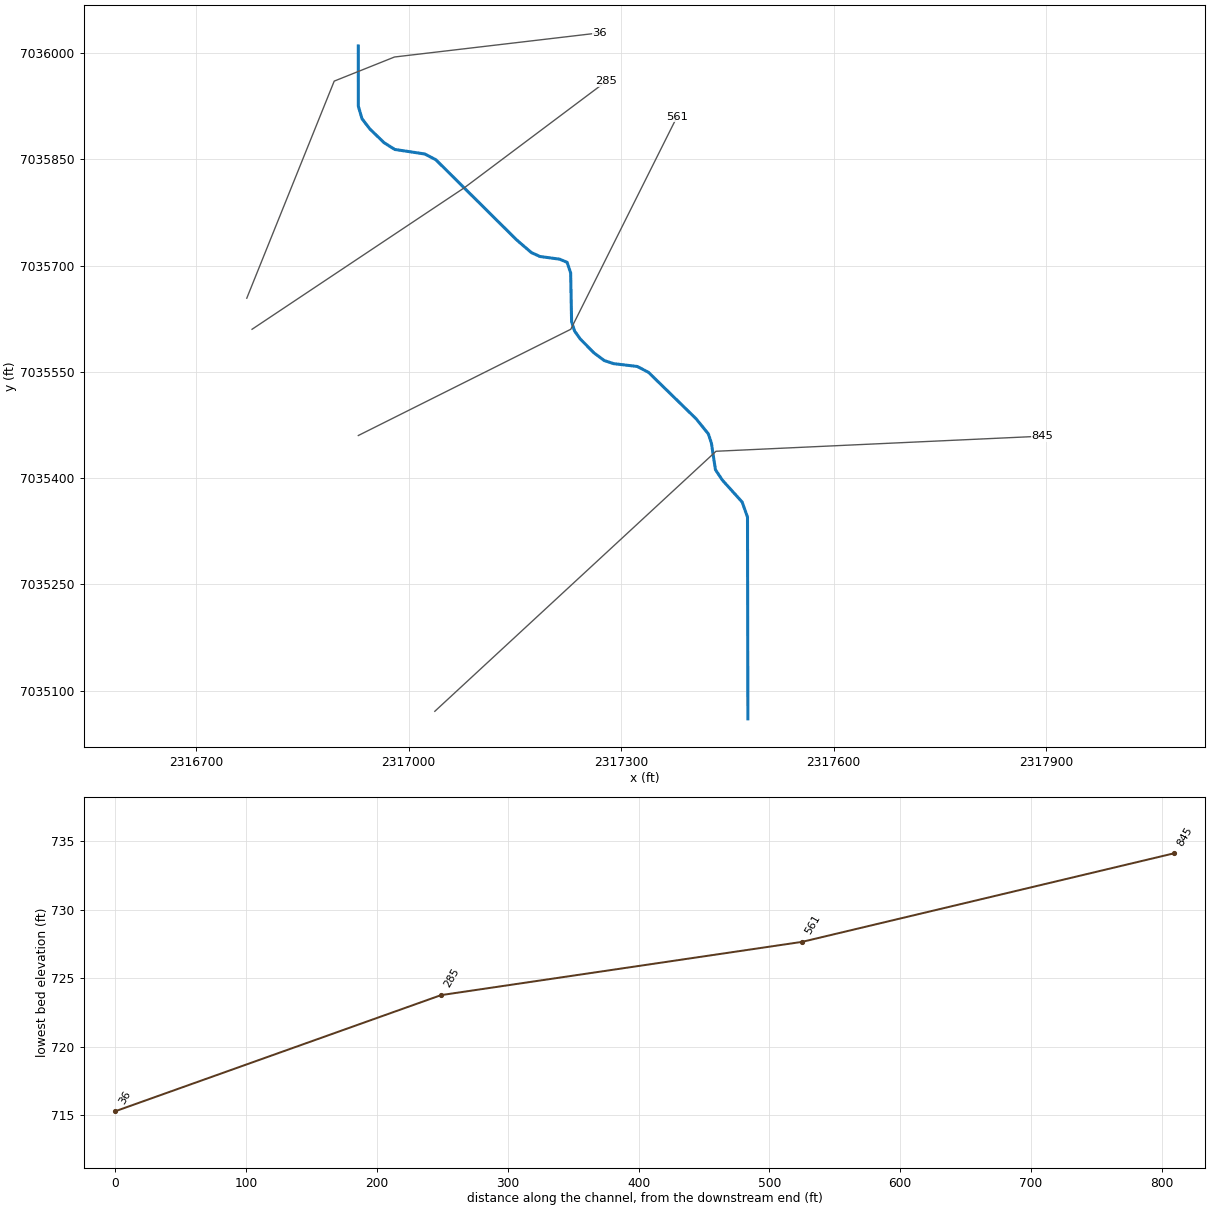
--- S116.prj (project) ---

Proj Title=S116 Base Level Engineering
Current Plan=p01
Default Exp/Contr=0.3,0.1
English Units
Geom File=g01
Flow File=f01
Plan File=p01
BEGIN DESCRIPTION:
S116
END DESCRIPTION:

--- S116.p01 (plan) ---

Plan Title=Multiple Run
Short Identifier=Multiple
Geom File=g01
Flow File=f01
Subcritical Flow
K Sum by GR= 0
Std Step Tol= 0.01
Critical Tol= 0.01
Num of Std Step Trials= 20
Max Error Tol= 0.3
Flow Tol Ratio= 0.001
Split Flow NTrial= 30
Split Flow Tol= 0.02
Split Flow Ratio= 0.02
Log Output Level= 0
Friction Slope Method= 1
Unsteady Friction Slope Method= 2
Unsteady Bridges Friction Slope Method= 1
Parabolic Critical Depth
Global Vel Dist=  1 , 1 , 1
Global Log Level= 0
CheckData=True
Encroach Param= -1, 0, 0, 0
BEGIN DESCRIPTION:
Multiple Run
END DESCRIPTION:

--- S116.f01 (steady flow) ---

Flow Title=Multiple
Number of Profiles=7
Profile Names=10-year,25-year,50-year,1pct_min,100-year,1pct_plu,500-year
River Rch & RM= S116,Reach-1,845
     193     243     282     163     325     648     428
Boundary for River Rch & Prof#=S116,Reach-1,1
Up Type=0
Dn Type=3
Dn Slope=0.01
Boundary for River Rch & Prof#=S116,Reach-1,2
Up Type=0
Dn Type=3
Dn Slope=0.01
Boundary for River Rch & Prof#=S116,Reach-1,3
Up Type=0
Dn Type=3
Dn Slope=0.01
Boundary for River Rch & Prof#=S116,Reach-1,4
Up Type=0
Dn Type=3
Dn Slope=0.01
Boundary for River Rch & Prof#=S116,Reach-1,5
Up Type=0
Dn Type=3
Dn Slope=0.01
Boundary for River Rch & Prof#=S116,Reach-1,6
Up Type=0
Dn Type=3
Dn Slope=0.01
Boundary for River Rch & Prof#=S116,Reach-1,7
Up Type=0
Dn Type=3
Dn Slope=0.01

--- S116.g01 (geometry) ---

Geom Title=Existing Conditions

River Reach=S116,Reach-1
Reach XY= 30
      2317479.00      7035060.00      2317478.49      7035344.79
      2317470.91      7035366.08      2317443.05      7035396.97
      2317433.22      7035411.75      2317427.50      7035449.39
      2317423.18      7035462.31      2317406.01      7035483.52
      2317338.68      7035549.22      2317322.92      7035557.45
      2317289.47      7035561.48      2317276.43      7035565.74
      2317261.88      7035576.47      2317242.27      7035596.38
      2317234.45      7035607.38      2317230.15      7035620.44
      2317228.78      7035689.73      2317223.74      7035704.52
      2317213.22      7035708.95      2317185.52      7035712.73
      2317173.30      7035718.30      2317152.31      7035736.35
      2317038.66      7035849.21      2317022.91      7035857.45
      2316980.41      7035863.87      2316965.38      7035873.44
      2316945.26      7035892.82      2316934.23      7035907.22
      2316929.05      7035924.89      2316929.00      7036010.00

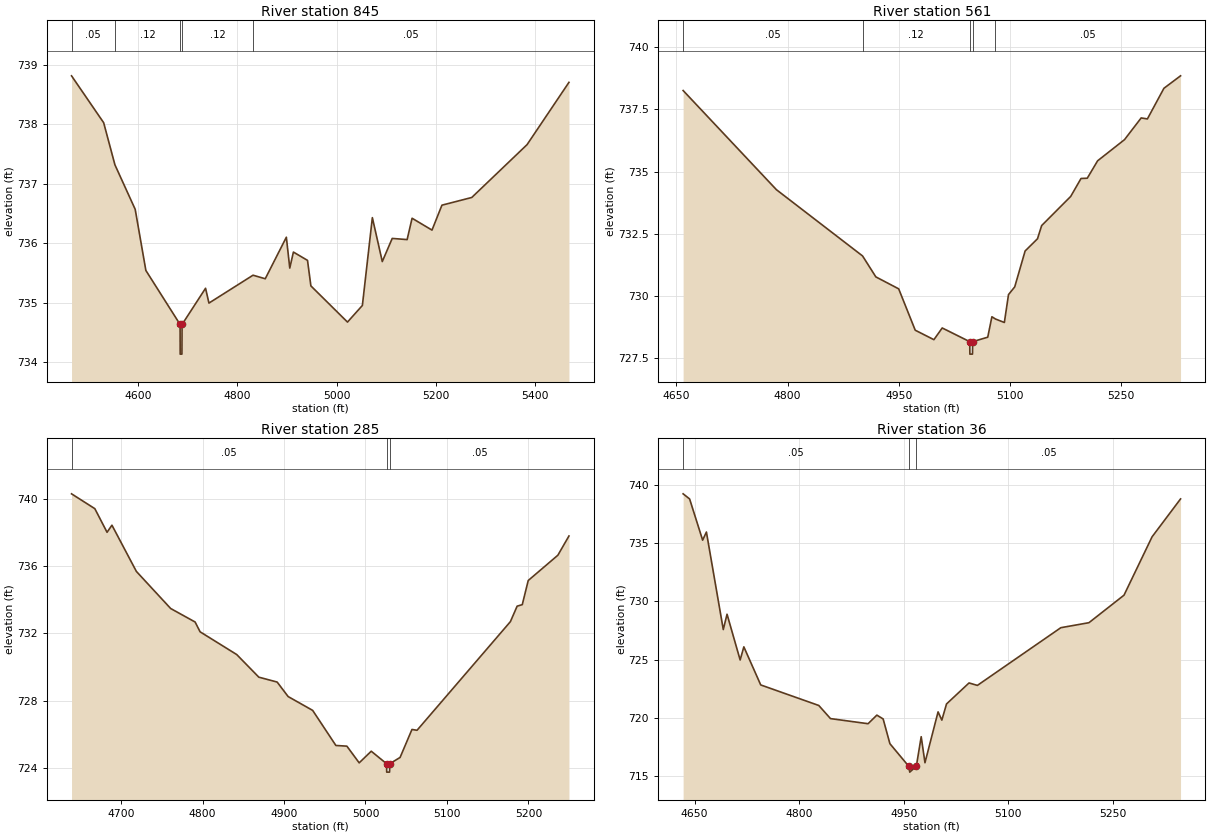
Type RM Length L Ch R = 1,845,284,284,284
BEGIN DESCRIPTION:
S116 3.0
END DESCRIPTION:
XS GIS Cut Line= 3
      2317037.03      7035070.64      2317434.04      7035437.76
      2317894.51      7035459.08
#Sta/Elev= 30
  4465.8  738.82  4530.5  738.03  4553.2  737.32  4594.0  736.57  4615.5  735.54
  4684.4  734.63  4684.6  734.13  4688.1  734.13  4688.4  734.63  4735.7  735.24
  4742.5  734.99  4831.3  735.46  4855.9  735.40  4898.4  736.10  4905.3  735.58
  4912.6  735.85  4941.0  735.71  4947.8  735.28  5021.5  734.67  5051.5  734.95
  5071.6  736.43  5091.6  735.69  5111.6  736.08  5141.6  736.06  5151.6  736.42
  5191.7  736.22  5211.7  736.64  5271.8  736.77  5383.1  737.66  5467.5  738.71
#Mann=5,-1,0
  4465.8    0.05       0  4553.2    0.12       0  4684.4   0.033       0
  4688.4    0.12       0  4831.3    0.05       0
Bank Sta=4684.4,4688.4
Exp/Cntr=0.3,0.1

Type RM Length L Ch R = 1,561,276,276,276
BEGIN DESCRIPTION:
S116 2.0
END DESCRIPTION:
XS GIS Cut Line= 3
      2316929.03      7035460.01      2317229.00      7035610.00
      2317379.00      7035910.01
#Sta/Elev= 30
  4659.2  738.25  4785.0  734.27  4901.2  731.61  4919.1  730.77  4949.9  730.29
  4972.2  728.63  4997.4  728.25  5008.6  728.72  5045.7  728.17  5045.9  727.67
  5049.4  727.67  5049.7  728.17  5070.0  728.35  5075.6  729.17  5080.4  729.08
  5092.4  728.94  5098.0  730.06  5106.4  730.37  5120.4  731.81  5137.1  732.30
  5142.7  732.83  5181.9  734.00  5195.8  734.72  5204.2  734.73  5218.2  735.43
  5254.5  736.28  5276.9  737.15  5285.3  737.11  5307.6  738.34  5330.0  738.84
#Mann=5,-1,0
  4659.2    0.05       0  4901.2    0.12       0  5045.7    0.07       0
  5049.7    0.12       0  5080.4    0.05       0
Bank Sta=5045.7,5049.7
Exp/Cntr=0.3,0.1

Type RM Length L Ch R = 1,285,249,249,249
BEGIN DESCRIPTION:
S116 1.0
END DESCRIPTION:
XS GIS Cut Line= 3
      2316778.99      7035610.00      2317079.00      7035810.00
      2317279.03      7035960.02
#Sta/Elev= 30
  4639.2  740.28  4667.8  739.40  4682.8  738.00  4688.8  738.42  4718.8  735.68
  4760.9  733.48  4790.9  732.68  4797.0  732.10  4842.0  730.75  4869.1  729.41
  4891.6  729.12  4905.1  728.26  4935.2  727.44  4963.7  725.36  4977.2  725.32
  4992.3  724.33  5007.1  725.02  5025.9  724.28  5026.1  723.78  5029.6  723.78
  5029.9  724.28  5042.5  724.65  5057.1  726.31  5063.3  726.26  5177.9  732.70
  5186.2  733.62  5192.5  733.71  5199.8  735.14  5236.2  736.64  5249.8  737.78
#Mann=3,-1,0
  4639.2    0.05       0  5025.9   0.033       0  5029.9    0.05       0
Bank Sta=5025.9,5029.9
Exp/Cntr=0.3,0.1

Type RM Length L Ch R = 1,36,0,0,0
BEGIN DESCRIPTION:
Stream116 0.1
END DESCRIPTION:
XS GIS Cut Line= 4
      2316771.56      7035653.87      2316895.00      7035960.35
      2316980.13      7035994.40      2317269.54      7036028.45
#Sta/Elev= 30
  4633.5  739.27  4642.8  738.83  4661.5  735.28  4666.9  735.98  4691.1  727.58
  4696.5  728.90  4715.3  724.96  4720.6  726.09  4744.8  722.81  4828.1  721.04
  4844.9  719.91  4898.8  719.47  4911.4  720.21  4920.4  719.88  4930.1  717.75
  4957.2  715.80  4958.6  715.30  4968.0  715.80  4975.0  718.35  4980.4  716.11
  4999.2  720.49  5004.6  719.78  5011.3  721.17  5043.6  722.98  5055.6  722.77
  5175.3  727.74  5215.6  728.17  5265.9  730.54  5306.2  735.57  5347.0  738.83
#Mann=3,-1,0
  4633.5    0.05       0  4957.2   0.033       0  4968.0    0.05       0
Bank Sta=4957.2,4968
Exp/Cntr=0.3,0.1

Chan Stop Cuts=-1