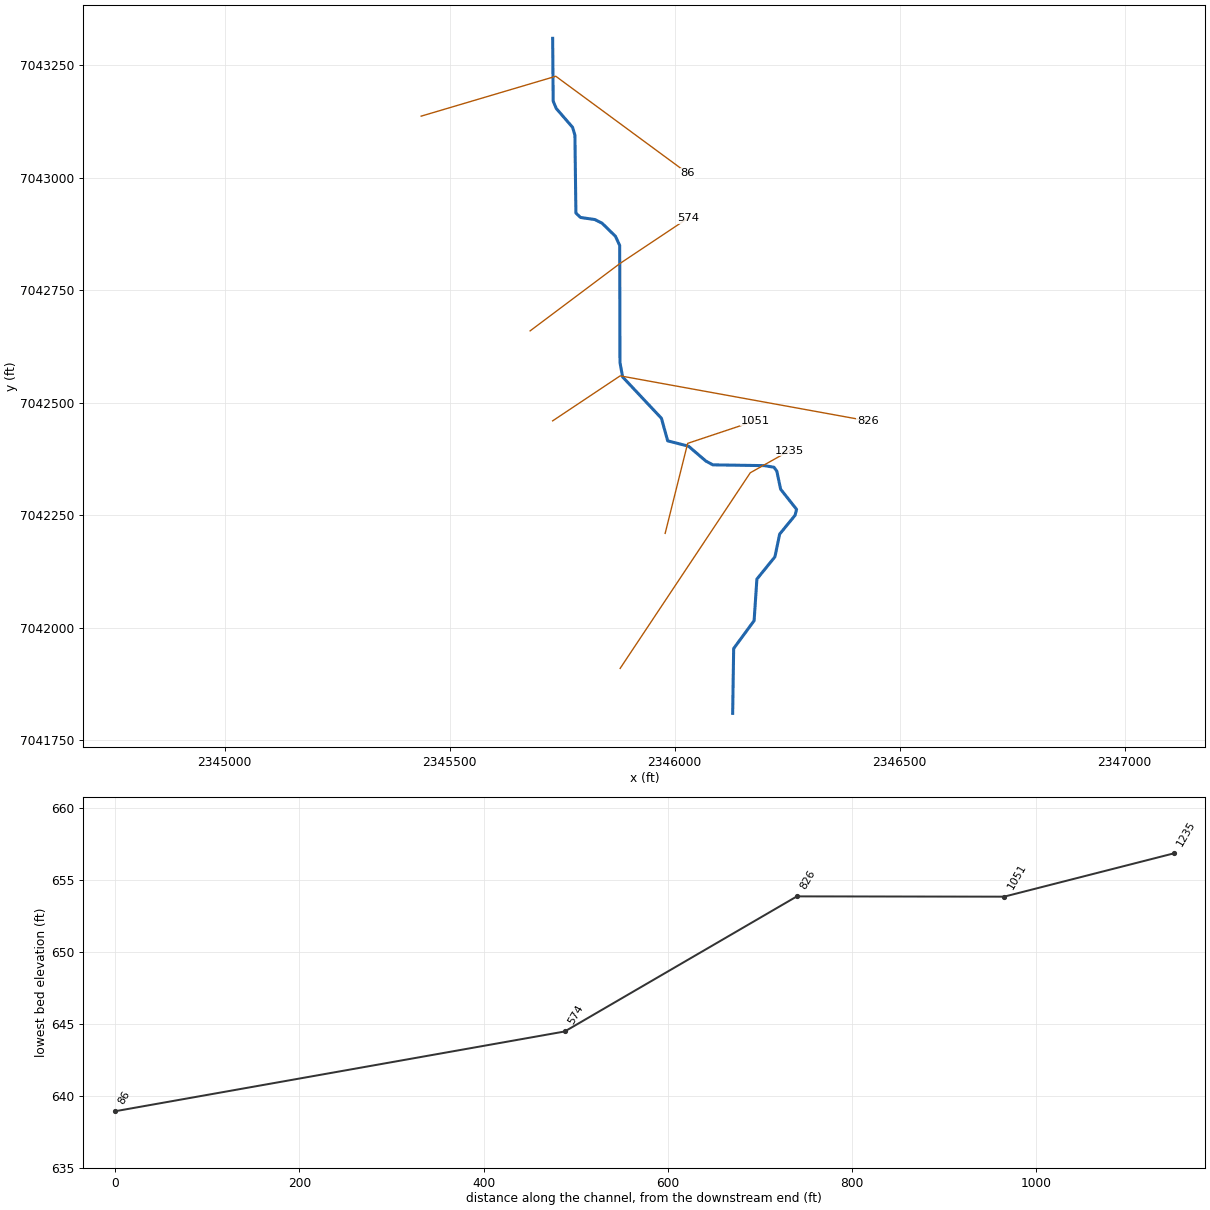
--- S147.prj (project) ---

Proj Title=S147 Base Level Engineering
Current Plan=p01
Default Exp/Contr=0.3,0.1
English Units
Geom File=g01
Flow File=f01
Plan File=p01
BEGIN DESCRIPTION:
S147
END DESCRIPTION:

--- S147.p01 (plan) ---

Plan Title=Multiple Run
Short Identifier=Multiple
Geom File=g01
Flow File=f01
Subcritical Flow
K Sum by GR= 0
Std Step Tol= 0.01
Critical Tol= 0.01
Num of Std Step Trials= 20
Max Error Tol= 0.3
Flow Tol Ratio= 0.001
Split Flow NTrial= 30
Split Flow Tol= 0.02
Split Flow Ratio= 0.02
Log Output Level= 0
Friction Slope Method= 1
Unsteady Friction Slope Method= 2
Unsteady Bridges Friction Slope Method= 1
Parabolic Critical Depth
Global Vel Dist=  1 , 1 , 1
Global Log Level= 0
CheckData=True
Encroach Param= -1, 0, 0, 0
BEGIN DESCRIPTION:
Multiple Run
END DESCRIPTION:

--- S147.f01 (steady flow) ---

Flow Title=Multiple
Number of Profiles=7
Profile Names=10-year,25-year,50-year,1pct_min,100-year,1pct_plu,500-year
River Rch & RM= S147,Reach-1,1235
     256     330     387     227     452     902     614
Boundary for River Rch & Prof#=S147,Reach-1,1
Up Type=0
Dn Type=3
Dn Slope=0.005
Boundary for River Rch & Prof#=S147,Reach-1,2
Up Type=0
Dn Type=3
Dn Slope=0.005
Boundary for River Rch & Prof#=S147,Reach-1,3
Up Type=0
Dn Type=3
Dn Slope=0.005
Boundary for River Rch & Prof#=S147,Reach-1,4
Up Type=0
Dn Type=3
Dn Slope=0.005
Boundary for River Rch & Prof#=S147,Reach-1,5
Up Type=0
Dn Type=3
Dn Slope=0.005
Boundary for River Rch & Prof#=S147,Reach-1,6
Up Type=0
Dn Type=3
Dn Slope=0.005
Boundary for River Rch & Prof#=S147,Reach-1,7
Up Type=0
Dn Type=3
Dn Slope=0.005

--- S147.g01 (geometry) ---

Geom Title=Existing Conditions

River Reach=S147,Reach-1
Reach XY= 30
      2346129.00      7041810.00      2346131.22      7041954.08
      2346176.65      7042015.97      2346182.83      7042108.42
      2346222.91      7042157.83      2346233.42      7042208.36
      2346267.61      7042250.10      2346271.00      7042263.35
      2346235.58      7042308.11      2346227.11      7042348.31
      2346220.74      7042356.92      2346199.44      7042360.51
      2346084.92      7042362.24      2346069.28      7042370.78
      2346030.84      7042403.72      2345984.61      7042415.59
      2345970.70      7042465.74      2345884.47      7042557.55
      2345878.57      7042589.82      2345877.99      7042849.71
      2345868.60      7042870.10      2345838.75      7042899.25
      2345822.68      7042907.35      2345790.74      7042912.00
      2345780.65      7042921.83      2345778.48      7043094.78
      2345773.26      7043112.34      2345737.13      7043153.94
      2345730.17      7043170.48      2345729.00      7043310.00

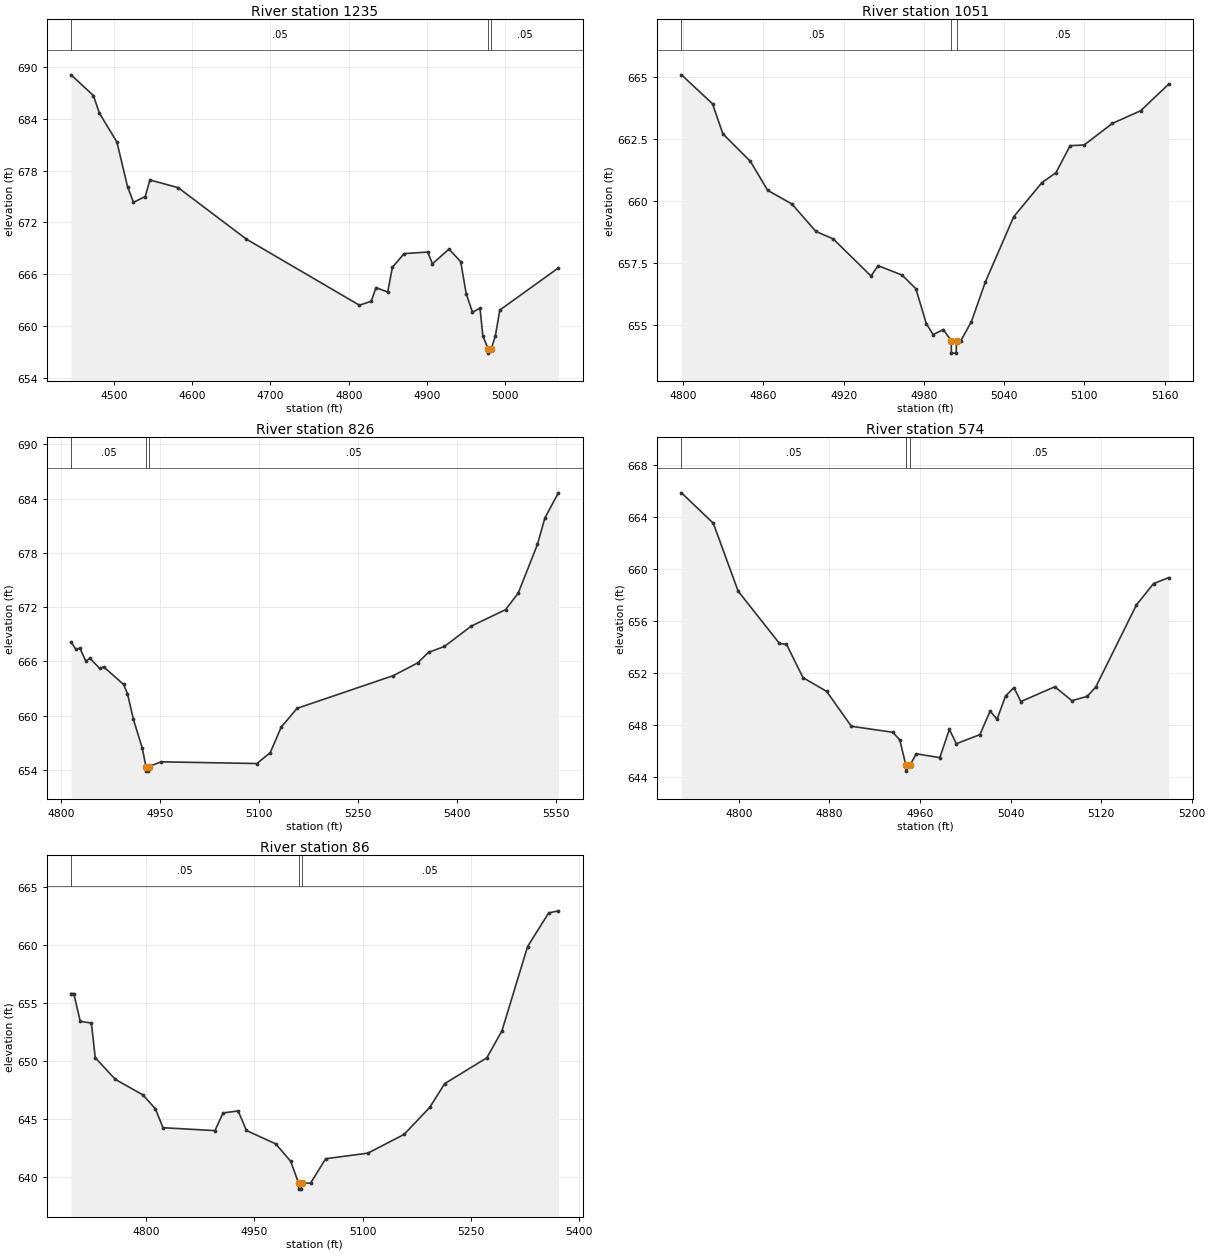
Type RM Length L Ch R = 1,1235,184,184,184
BEGIN DESCRIPTION:
S147 5.0
END DESCRIPTION:
XS GIS Cut Line= 3
      2345878.99      7041909.98      2346168.18      7042344.68
      2346255.42      7042393.75
#Sta/Elev= 30
  4445.5  689.10  4474.1  686.70  4481.6  684.68  4504.1  681.31  4517.6  676.16
  4525.2  674.33  4540.2  675.00  4546.2  676.92  4582.3  676.03  4669.5  670.06
  4813.7  662.41  4828.8  662.87  4834.8  664.45  4849.8  663.94  4855.8  666.81
  4870.8  668.39  4900.9  668.57  4906.9  667.21  4928.0  668.91  4943.0  667.46
  4950.0  663.74  4958.0  661.61  4967.6  662.06  4971.3  658.84  4978.0  657.36
  4978.3  656.86  4982.0  657.36  4987.2  658.84  4992.9  661.85  5067.7  666.73
#Mann=3,-1,0
  4445.5    0.05       0  4978.0   0.033       0  4982.0    0.05       0
Bank Sta=4978,4982
Exp/Cntr=0.3,0.1

Type RM Length L Ch R = 1,1051,225,225,225
BEGIN DESCRIPTION:
S147 4.0
END DESCRIPTION:
XS GIS Cut Line= 3
      2345979.00      7042210.00      2346029.00      7042410.00
      2346179.03      7042460.01
#Sta/Elev= 30
  4798.8  665.08  4822.0  663.91  4829.7  662.70  4850.3  661.59  4863.2  660.42
  4881.3  659.87  4899.3  658.76  4912.2  658.46  4940.5  656.96  4945.7  657.38
  4963.7  657.00  4974.0  656.45  4981.8  655.04  4986.9  654.60  4994.6  654.80
  5000.4  654.35  5000.6  653.85  5004.1  653.85  5004.4  654.35  5007.6  654.35
  5015.5  655.12  5026.0  656.73  5047.1  659.35  5068.2  660.73  5078.7  661.13
  5089.3  662.22  5099.8  662.25  5120.9  663.12  5142.0  663.63  5163.1  664.71
#Mann=3,-1,0
  4798.8    0.05       0  5000.4   0.033       0  5004.4    0.05       0
Bank Sta=5000.4,5004.4
Exp/Cntr=0.3,0.1

Type RM Length L Ch R = 1,826,252,252,252
BEGIN DESCRIPTION:
S147 3.0
END DESCRIPTION:
XS GIS Cut Line= 3
      2345729.04      7042460.02      2345879.00      7042560.00
      2346429.05      7042459.99
#Sta/Elev= 30
  4815.0  668.13  4822.5  667.33  4828.5  667.45  4837.5  666.02  4843.5  666.34
  4858.5  665.23  4864.5  665.40  4894.6  663.46  4900.6  662.44  4909.6  659.60
  4923.1  656.40  4928.6  654.37  4928.9  653.87  4932.4  653.87  4932.6  654.37
  4951.7  654.90  5096.9  654.71  5117.2  655.91  5133.7  658.72  5157.9  660.81
  5304.0  664.43  5340.8  665.83  5357.3  667.00  5381.5  667.65  5422.1  669.90
  5474.2  671.72  5493.3  673.54  5522.5  678.92  5533.9  681.87  5554.3  684.63
#Mann=3,-1,0
  4815.0    0.05       0  4928.6   0.033       0  4932.6    0.05       0
Bank Sta=4928.6,4932.6
Exp/Cntr=0.3,0.1

Type RM Length L Ch R = 1,574,488,488,488
BEGIN DESCRIPTION:
S147 2.0
END DESCRIPTION:
XS GIS Cut Line= 3
      2345678.99      7042659.99      2345879.00      7042810.00
      2346029.01      7042910.01
#Sta/Elev= 30
  4749.5  665.88  4777.6  663.54  4799.5  658.32  4836.0  654.29  4842.2  654.23
  4856.8  651.66  4877.6  650.61  4899.5  647.92  4936.0  647.46  4942.2  646.88
  4947.5  644.97  4947.8  644.47  4951.5  644.97  4956.8  645.80  4977.6  645.51
  4986.0  647.68  4992.2  646.58  5013.0  647.28  5022.0  649.09  5028.1  648.46
  5035.6  650.25  5043.1  650.90  5049.1  649.82  5079.1  650.96  5094.2  649.89
  5107.7  650.22  5115.2  650.93  5151.2  657.26  5166.3  658.90  5179.8  659.36
#Mann=3,-1,0
  4749.5    0.05       0  4947.5   0.033       0  4951.5    0.05       0
Bank Sta=4947.5,4951.5
Exp/Cntr=0.3,0.1

Type RM Length L Ch R = 1,86,0,0,0
BEGIN DESCRIPTION:
S147 1.0
END DESCRIPTION:
XS GIS Cut Line= 3
      2345436.76      7043137.07      2345735.97      7043225.72
      2346028.97      7043010.03
#Sta/Elev= 30
  4695.6  655.83  4699.4  655.83  4708.4  653.42  4723.8  653.28  4729.2  650.28
  4757.0  648.41  4795.5  647.06  4812.7  645.85  4823.1  644.23  4895.2  643.98
  4906.5  645.51  4927.4  645.68  4938.9  643.99  4979.5  642.83  5000.2  641.33
  5011.3  639.42  5011.5  638.92  5015.0  638.92  5015.3  639.42  5027.9  639.45
  5048.8  641.55  5107.3  642.03  5157.5  643.65  5193.0  645.98  5213.8  648.04
  5272.2  650.27  5293.2  652.60  5328.7  659.88  5358.0  662.80  5371.5  662.98
#Mann=3,-1,0
  4695.6    0.05       0  5011.3   0.033       0  5015.3    0.05       0
Bank Sta=5011.3,5015.3
Exp/Cntr=0.3,0.1

Chan Stop Cuts=-1