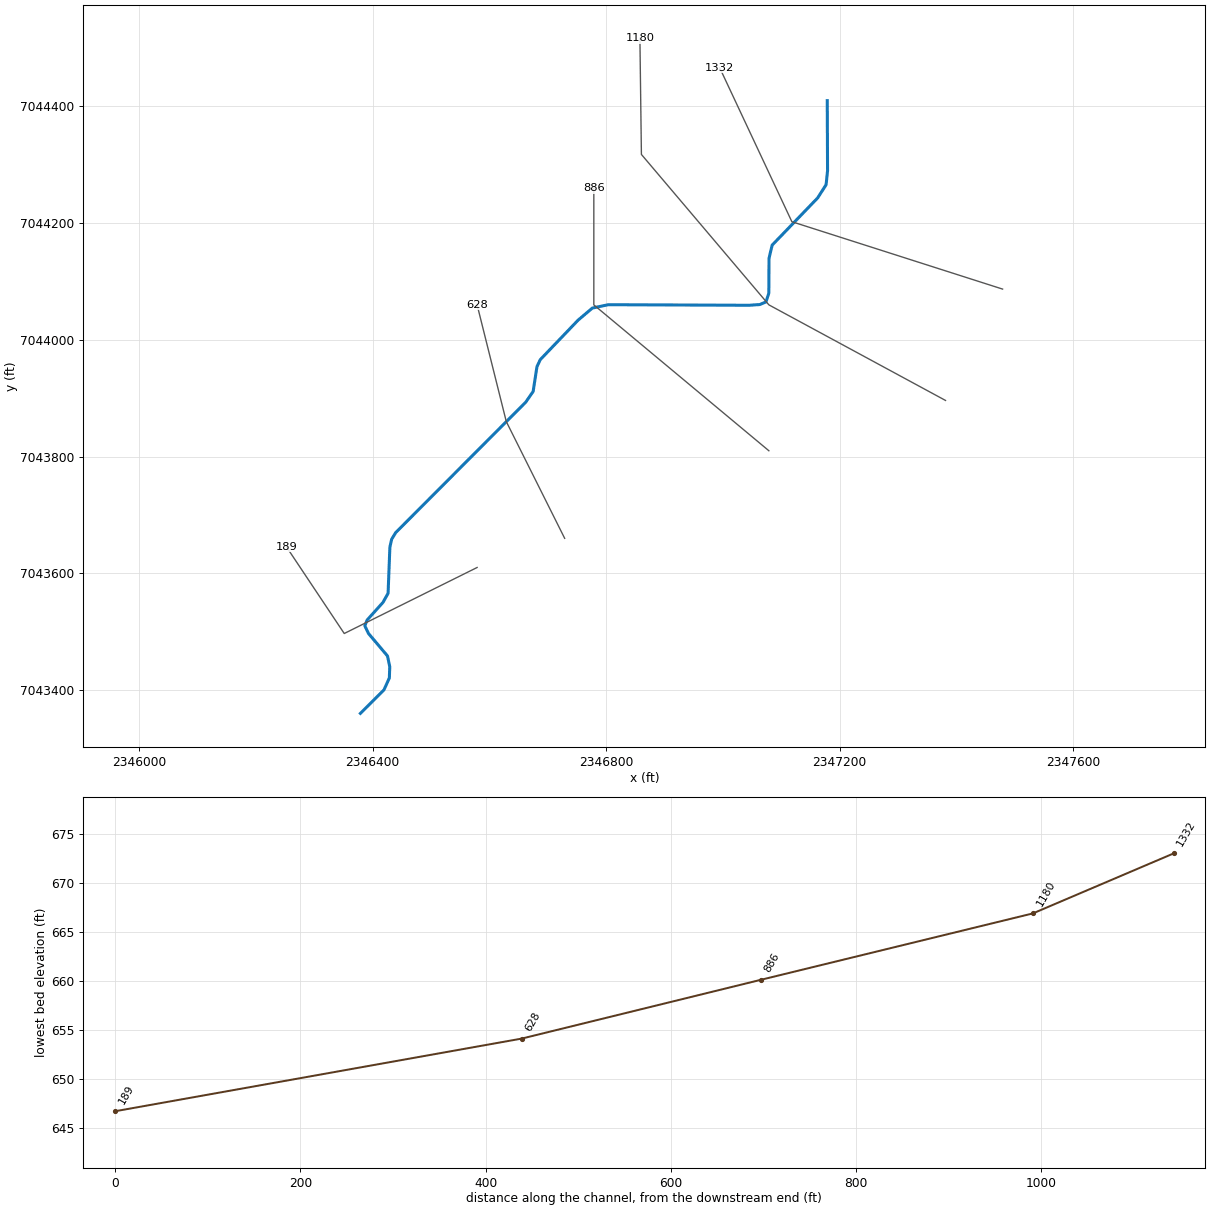
--- S151.prj (project) ---

Proj Title=S151 Base Level Engineering
Current Plan=p01
Default Exp/Contr=0.3,0.1
English Units
Geom File=g01
Flow File=f01
Plan File=p01
Y Axis Title=Elevation
X Axis Title(PF)=Main Channel Distance
X Axis Title(XS)=Station
BEGIN DESCRIPTION:
S151
END DESCRIPTION:
DSS Export Rating Curves= 0
DSS Export Rating Curve Sorted= 0
DSS Export Volume Flow Curves= 0
DXF OffsetX= 0
DXF OffsetY= 0
DXF ScaleX= 1
DXF ScaleY= 10

--- S151.p01 (plan) ---

Plan Title=Multiple Run
Program Version=4.10
Short Identifier=Multiple
Geom File=g01
Flow File=f01
Subcritical Flow
K Sum by GR= 0
Std Step Tol= 0.01
Critical Tol= 0.01
Num of Std Step Trials= 20
Max Error Tol= 0.3
Flow Tol Ratio= 0.001
Split Flow NTrial= 30
Split Flow Tol= 0.02
Split Flow Ratio= 0.02
Log Output Level= 0
Friction Slope Method= 0
Unsteady Friction Slope Method= 2
Unsteady Bridges Friction Slope Method= 1
Parabolic Critical Depth
Global Vel Dist= 1 , 1 , 1
Global Log Level= 0
CheckData=True
Encroach Param=-1 ,0,0, 0
BEGIN DESCRIPTION:
Multiple Run
END DESCRIPTION:
Computation Interval=1HOUR
Output Interval=1HOUR
Run HTab= 0
Run UNet= 0
Run PostProcess= 0
Run WQNet= 0
UNET Theta= 1
UNET Theta Warmup= 1
UNET ZTol= 0.02
UNET ZSATol= 0.05
UNET MxIter= 20
UNET MaxInSteps= 0
UNET DtIC= 0
UNET DtMin= 0
UNET MaxCRTS= 20
UNET WFStab= 2
UNET SFStab= 1
UNET WFX= 1
UNET SFX= 1
UNET DSS MLevel= 4
UNET DZMax Abort= 100
UNET Convert EG Bridges= 0
UNET Use Existing IB Tables=-1
UNET Froude Reduction=False
UNET Froude Limit= 1
UNET Froude Power= 10
UNET Time Slicing=0,0, 5
UNET Junction Losses=0
Instantaneous Interval=1HOUR
Write IC File= 0
Write IC File at Sim End=0
Echo Input=False
Echo Parameters=False
Echo Output=False
Write Detailed= 0
WQ AD Non Conservative
WQ ULTIMATE=-1
WQ Max Comp Step=1HOUR
WQ Output Interval=15MIN
WQ Output Selected Increments= 0
WQ Output face flow=0
WQ Output face velocity=0
WQ Output face area=0
WQ Output face dispersion=0
WQ Output cell volume=0
WQ Output cell surface area=0
WQ Output cell continuity=0
WQ Output cumulative cell continuity=0
WQ Output face conc=0
WQ Output face dconc_dx=0
WQ Output face courant=0
WQ Output face peclet=0
WQ Output face adv mass=0
WQ Output face disp mass=0
WQ Output cell mass=0
WQ Output cell source sink temp=0
WQ Output cell source sink nsm=0
WQ Output MaxMinRange=-1
WQ Daily Max Min Mean=-1
WQ Daily Range=0
WQ Daily Time=0
WQ Create Restart=0
WQ Fixed Restart=0
WQ System Summary=0
WQ Use Fixed Temperature=0
Sorting and Armoring Iterations= 10
XS Update Threshold= 0.02
Hydraulics Update Threshold= 0.02
Energy Slope Method= 1
Volume Change Method= 0
XS Weighting Method= 0
Number of US Weighted Cross Sections= 1
Number of DS Weighted Cross Sections= 1
Upstream XS Weight=0.25
Main XS Weight=0.5
Downstream XS Weight=0.25
Number of DS XS's Weighted with US Boundary= 1
Upstream Boundary Weight= 1
Weight of XSs Associated with US Boundary= 0
Number of US XS's Weighted with DS Boundary= 1
Downstream Boundary Weight= 0.5
Weight of XSs Associated with DS Boundary= 0.5
Sediment Output Level= 4
Mass or Volume Output= 0
Output Increment Type= 1
Profile and TS Output Increment= 10
XS Output Flag= 0
XS Output Increment= 10
Disregard all LS=0
Disregard all Conn=0
Disregard all Breaches=0
Disregard all Pumps=0

--- S151.f01 (steady flow) ---

Flow Title=Multiple
Number of Profiles=7
Profile Names=10-year,25-year,50-year,1pct_min,100-year,1pct_plu,500-year
River Rch & RM= S151,Reach-1,1332
     258     332     390     228     455     908     618
Boundary for River Rch & Prof#=S151,Reach-1,1
Up Type=0
Dn Type=3
Dn Slope=0.005
Boundary for River Rch & Prof#=S151,Reach-1,2
Up Type=0
Dn Type=3
Dn Slope=0.005
Boundary for River Rch & Prof#=S151,Reach-1,3
Up Type=0
Dn Type=3
Dn Slope=0.005
Boundary for River Rch & Prof#=S151,Reach-1,4
Up Type=0
Dn Type=3
Dn Slope=0.005
Boundary for River Rch & Prof#=S151,Reach-1,5
Up Type=0
Dn Type=3
Dn Slope=0.005
Boundary for River Rch & Prof#=S151,Reach-1,6
Up Type=0
Dn Type=3
Dn Slope=0.005
Boundary for River Rch & Prof#=S151,Reach-1,7
Up Type=0
Dn Type=3
Dn Slope=0.005

--- S151.g01 (geometry) ---

Geom Title=Existing Conditions

River Reach=S151,Reach-1
Reach XY= 30
      2347179.00      7044410.00      2347179.51      7044289.79
      2347176.98      7044265.84      2347162.54      7044243.25
      2347084.57      7044162.36      2347079.21      7044139.77
      2347078.88      7044080.01      2347073.92      7044065.03
      2347063.42      7044060.56      2347044.68      7044059.31
      2346803.87      7044060.30      2346776.53      7044054.55
      2346752.07      7044033.86      2346687.15      7043966.07
      2346681.53      7043953.96      2346675.02      7043911.65
      2346662.35      7043893.33      2346439.52      7043669.79
      2346432.61      7043658.50      2346429.51      7043644.78
      2346426.45      7043565.90      2346417.75      7043550.22
      2346390.48      7043519.90      2346386.56      7043509.99
      2346392.97      7043496.76      2346425.40      7043458.42
      2346429.31      7043439.94      2346428.61      7043420.68
      2346419.36      7043400.21      2346379.00      7043360.00

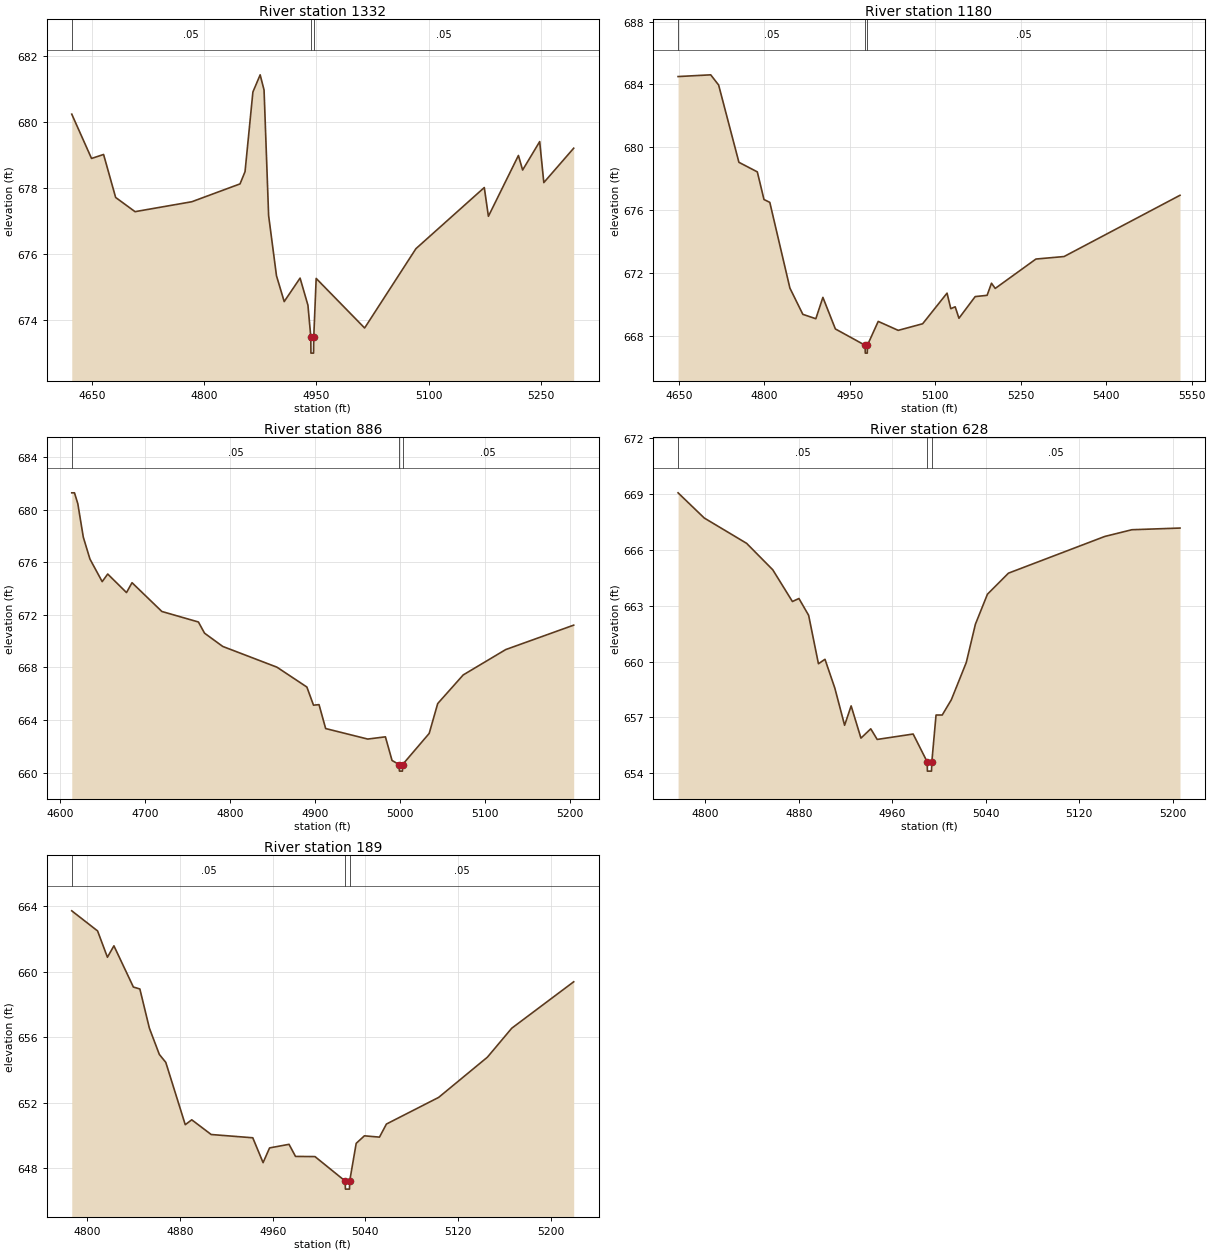
Type RM Length L Ch R = 1,1332,152,152,152
BEGIN DESCRIPTION:
S151 5.0
END DESCRIPTION:
XS GIS Cut Line= 3
      2347479.45      7044087.05      2347118.37      7044202.49
      2346994.75      7044466.16
#Sta/Elev= 30
  4623.2  680.24  4649.6  678.90  4665.7  679.02  4681.8  677.72  4707.7  677.29
  4783.5  677.59  4847.9  678.13  4854.6  678.50  4865.1  680.91  4874.8  681.43
  4880.0  680.97  4886.1  677.17  4896.6  675.35  4906.9  674.57  4928.1  675.28
  4938.6  674.46  4942.4  673.51  4942.6  673.01  4946.1  673.01  4946.4  673.51
  4949.6  675.27  5014.3  673.77  5082.8  676.17  5174.1  678.02  5179.6  677.15
  5219.7  678.99  5225.3  678.55  5248.1  679.41  5253.6  678.17  5293.5  679.21
#Mann=3,-1,0
  4623.2    0.05       0  4942.4   0.033       0  4946.4    0.05       0
Bank Sta=4942.4,4946.4
Exp/Cntr=0.3,0.1

Type RM Length L Ch R = 1,1180,294,294,294
BEGIN DESCRIPTION:
S151 4.0
END DESCRIPTION:
XS GIS Cut Line= 4
      2347381.65      7043896.23      2347079.00      7044060.00
      2346860.53      7044317.79      2346857.97      7044516.74
#Sta/Elev= 30
  4648.6  684.50  4705.9  684.61  4719.8  683.96  4755.4  679.04  4787.7  678.43
  4799.4  676.67  4809.6  676.49  4844.9  671.03  4867.6  669.36  4890.4  669.08
  4902.8  670.44  4924.7  668.43  4976.9  667.39  4977.2  666.89  4980.7  666.89
  4980.9  667.39  4999.9  668.91  5035.0  668.34  5077.9  668.76  5120.7  670.71
  5127.3  669.72  5135.0  669.84  5141.6  669.11  5170.1  670.49  5191.0  670.57
  5198.7  671.34  5205.3  671.01  5276.7  672.88  5326.1  673.04  5529.6  676.94
#Mann=3,-1,0
  4648.6    0.05       0  4976.9    0.04       0  4980.9    0.05       0
Bank Sta=4976.9,4980.9
Exp/Cntr=0.3,0.1

Type RM Length L Ch R = 1,886,258,258,258
BEGIN DESCRIPTION:
S151 3.0
END DESCRIPTION:
XS GIS Cut Line= 3
      2347078.97      7043810.03      2346779.00      7044060.00
      2346779.00      7044260.03
#Sta/Elev= 30
  4614.0  681.29  4617.2  681.29  4621.1  680.47  4627.6  677.91  4635.4  676.25
  4649.8  674.53  4656.3  675.11  4678.4  673.70  4684.9  674.45  4720.0  672.26
  4763.0  671.46  4770.2  670.61  4791.6  669.60  4855.4  668.02  4890.6  666.51
  4898.4  665.13  4904.9  665.17  4912.7  663.35  4962.2  662.55  4983.0  662.72
  4990.8  660.92  4999.2  660.61  4999.5  660.11  5003.0  660.11  5003.2  660.61
  5034.5  662.98  5044.5  665.25  5074.5  667.43  5124.5  669.36  5204.5  671.22
#Mann=3,-1,0
  4614.0    0.05       0  4999.2   0.033       0  5003.2    0.05       0
Bank Sta=4999.2,5003.2
Exp/Cntr=0.3,0.1

Type RM Length L Ch R = 1,628,439,439,439
BEGIN DESCRIPTION:
S151 2.0
END DESCRIPTION:
XS GIS Cut Line= 3
      2346729.02      7043659.96      2346629.00      7043860.00
      2346579.00      7044059.99
#Sta/Elev= 30
  4776.6  669.05  4799.0  667.70  4835.3  666.34  4857.7  664.92  4874.5  663.22
  4880.1  663.38  4888.4  662.48  4896.8  659.88  4902.4  660.12  4910.8  658.58
  4919.2  656.58  4924.8  657.62  4933.2  655.89  4941.6  656.39  4947.1  655.82
  4977.9  656.11  4989.9  654.62  4990.1  654.12  4993.6  654.12  4993.9  654.62
  4997.5  657.13  5002.8  657.13  5010.6  657.95  5023.4  659.95  5031.2  662.00
  5041.5  663.61  5059.5  664.74  5142.0  666.71  5165.2  667.07  5206.4  667.16
#Mann=3,-1,0
  4776.6    0.05       0  4989.9   0.033       0  4993.9    0.05       0
Bank Sta=4989.9,4993.9
Exp/Cntr=0.3,0.1

Type RM Length L Ch R = 1,189,0,0,0
BEGIN DESCRIPTION:
S151 1.0
END DESCRIPTION:
XS GIS Cut Line= 3
      2346578.99      7043609.99      2346351.30      7043496.85
      2346251.92      7043645.91
#Sta/Elev= 30
  4786.5  663.73  4808.8  662.50  4817.3  660.89  4822.9  661.59  4839.7  659.07
  4845.3  658.95  4853.5  656.56  4862.1  654.95  4867.7  654.46  4884.5  650.65
  4890.1  650.95  4906.9  650.05  4942.8  649.85  4951.7  648.33  4957.3  649.23
  4974.1  649.45  4979.7  648.71  4996.5  648.70  5022.5  647.21  5022.8  646.71
  5026.3  646.71  5026.5  647.21  5032.1  649.51  5039.2  649.97  5052.2  649.89
  5058.2  650.69  5103.3  652.32  5145.4  654.78  5166.4  656.55  5219.9  659.39
#Mann=3,-1,0
  4786.5    0.05       0  5022.5   0.033       0  5026.5    0.05       0
Bank Sta=5022.5,5026.5
Exp/Cntr=0.3,0.1

Chan Stop Cuts=-1