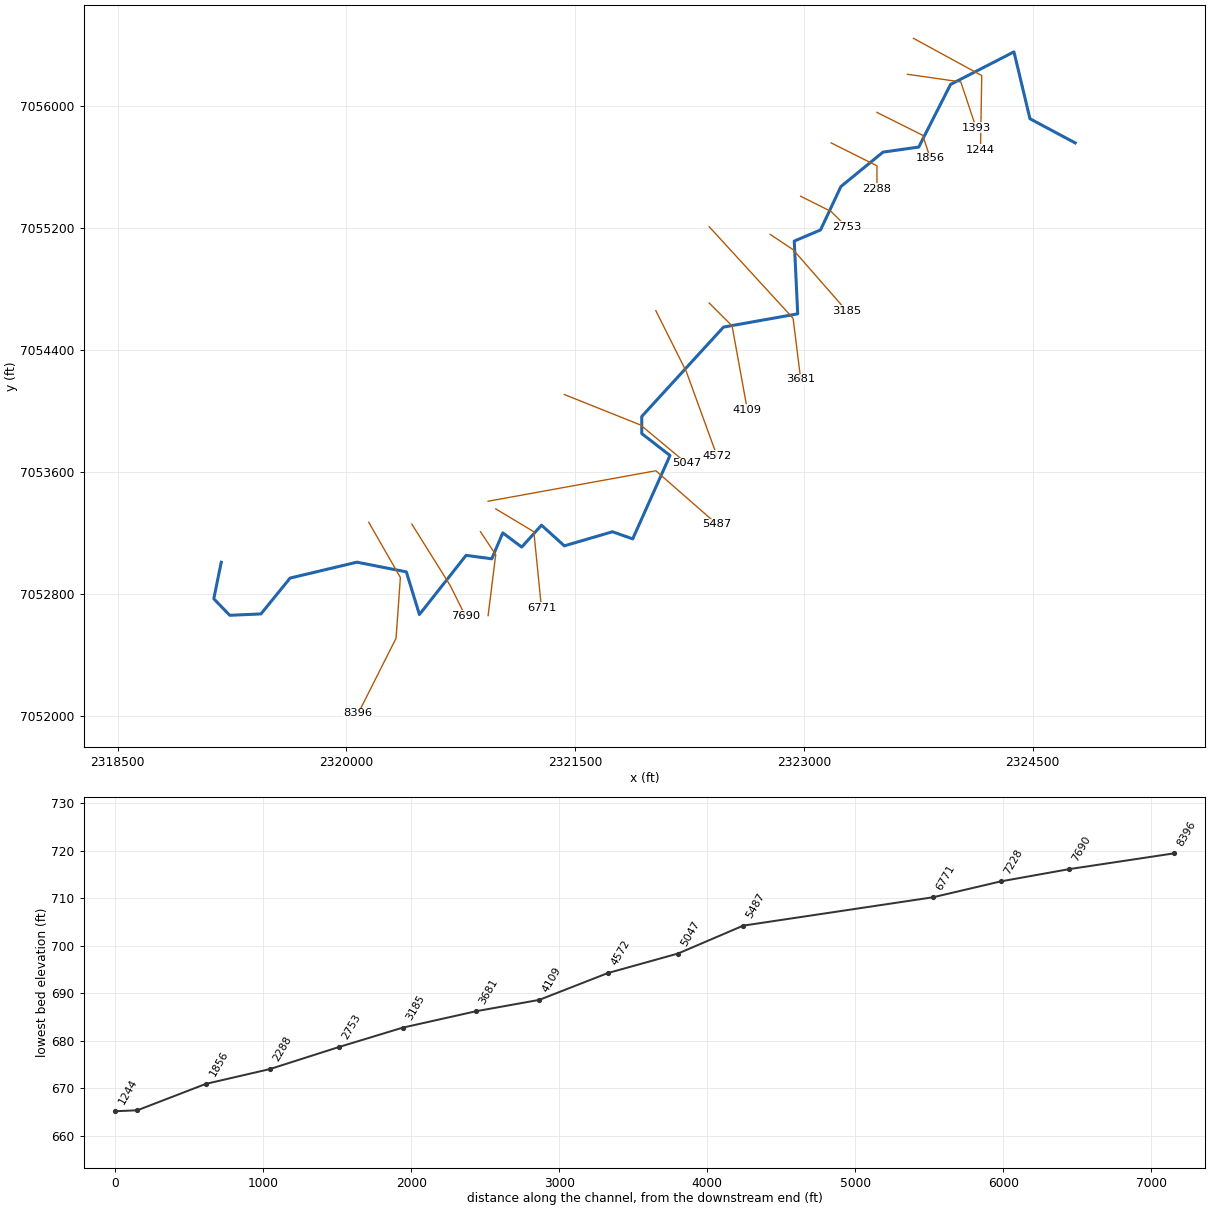
--- S26.prj (project) ---

Proj Title=S26 Base Level Engineering
Current Plan=p01
Default Exp/Contr=0.3,0.1
English Units
Geom File=g01
Flow File=f01
Plan File=p01
BEGIN DESCRIPTION:
S26
END DESCRIPTION:

--- S26.p01 (plan) ---

Plan Title=Multiple Run
Short Identifier=Multiple
Geom File=g01
Flow File=f01
Subcritical Flow
K Sum by GR= 0
Std Step Tol= 0.01
Critical Tol= 0.01
Num of Std Step Trials= 20
Max Error Tol= 0.3
Flow Tol Ratio= 0.001
Split Flow NTrial= 30
Split Flow Tol= 0.02
Split Flow Ratio= 0.02
Log Output Level= 0
Friction Slope Method= 1
Unsteady Friction Slope Method= 2
Unsteady Bridges Friction Slope Method= 1
Parabolic Critical Depth
Global Vel Dist=  1 , 1 , 1
Global Log Level= 0
CheckData=True
Encroach Param= -1, 0, 0, 0
BEGIN DESCRIPTION:
Multiple Run
END DESCRIPTION:

--- S26.f01 (steady flow) ---

Flow Title=Multiple
Number of Profiles=7
Profile Names=10-year,25-year,50-year,1pct_min,100-year,1pct_plu,500-year
River Rch & RM= S26,Reach-1,8396
     577     788     962     583    1160    2320    1700
River Rch & RM= S26,Reach-1,7690
     777    1080    1330     815    1630    3250    2430
River Rch & RM= S26,Reach-1,2753
     824    1150    1420     871    1740    3470    2610
Boundary for River Rch & Prof#=S26,Reach-1,1
Up Type=0
Dn Type=3
Dn Slope=0.005
Boundary for River Rch & Prof#=S26,Reach-1,2
Up Type=0
Dn Type=3
Dn Slope=0.005
Boundary for River Rch & Prof#=S26,Reach-1,3
Up Type=0
Dn Type=3
Dn Slope=0.005
Boundary for River Rch & Prof#=S26,Reach-1,4
Up Type=0
Dn Type=3
Dn Slope=0.005
Boundary for River Rch & Prof#=S26,Reach-1,5
Up Type=0
Dn Type=3
Dn Slope=0.005
Boundary for River Rch & Prof#=S26,Reach-1,6
Up Type=0
Dn Type=3
Dn Slope=0.005
Boundary for River Rch & Prof#=S26,Reach-1,7
Up Type=0
Dn Type=3
Dn Slope=0.005

--- S26.g01 (geometry) ---

Geom Title=Existing Conditions

River Reach=S26,Reach-1
Reach XY= 30
      2319179.00      7053010.00      2319130.04      7052770.43
      2319234.88      7052661.96      2319439.37      7052671.08
      2319630.56      7052906.24      2320068.82      7053010.46
      2320392.73      7052946.77      2320478.70      7052667.17
      2320784.58      7053055.23      2320952.95      7053032.51
      2321025.38      7053202.52      2321149.42      7053109.43
      2321279.19      7053252.99      2321428.96      7053117.52
      2321744.40      7053209.90      2321877.38      7053163.13
      2322122.01      7053710.22      2321936.75      7053853.81
      2321936.76      7053966.17      2322472.84      7054552.12
      2322959.40      7054638.94      2322936.76      7055116.21
      2323109.08      7055189.07      2323242.47      7055473.57
      2323518.88      7055699.65      2323753.02      7055732.66
      2323961.87      7056143.55      2324377.63      7056356.99
      2324482.49      7055918.51      2324779.00      7055760.00

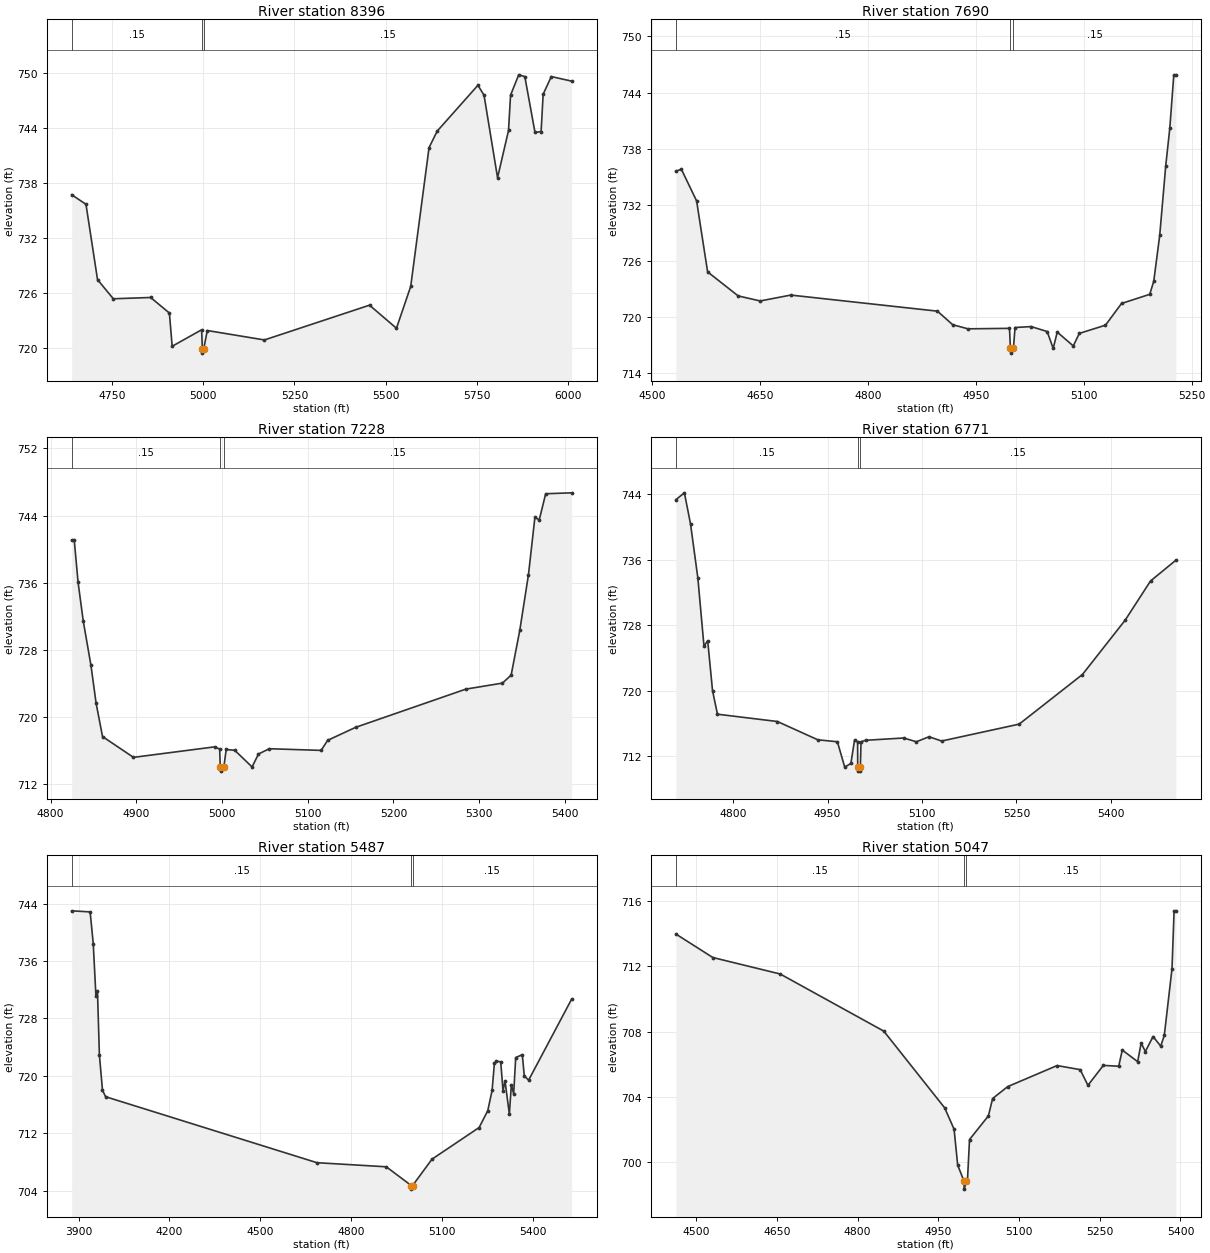
Type RM Length L Ch R = 1,8396,706,706,706
BEGIN DESCRIPTION:
1030
END DESCRIPTION:
XS GIS Cut Line= 4
      2320146.27      7053272.10      2320353.78      7052909.97
      2320325.30      7052511.23      2320077.09      7052018.88
#Sta/Elev= 30
  4640.3  736.75  4679.5  735.70  4711.1  727.47  4754.3  725.38  4856.5  725.52
  4907.8  723.82  4915.4  720.19  4996.0  721.99  4998.0  719.94  4998.3  719.44
  5002.0  719.94  5011.5  721.91  5167.9  720.88  5455.5  724.68  5529.3  722.16
  5568.3  726.73  5618.5  741.90  5640.8  743.70  5752.3  748.71  5769.0  747.62
  5806.0  738.61  5836.0  743.77  5841.6  747.63  5863.9  749.85  5880.6  749.66
  5908.5  743.55  5925.2  743.65  5930.8  747.73  5953.1  749.66  6008.8  749.16
#Mann=3,-1,0
  4640.3    0.15       0  4998.0    0.05       0  5002.0    0.15       0
Bank Sta=4998,5002
Exp/Cntr=0.3,0.1

Type RM Length L Ch R = 1,7690,462,462,462
BEGIN DESCRIPTION:
S26 13.0
END DESCRIPTION:
XS GIS Cut Line= 3
      2320429.00      7053259.99      2320679.00      7052860.00
      2320779.00      7052660.00
#Sta/Elev= 30
  4532.6  735.59  4540.3  735.80  4561.5  732.41  4576.8  724.82  4619.3  722.25
  4649.9  721.71  4692.4  722.34  4896.4  720.62  4917.6  719.17  4938.8  718.73
  4996.6  718.78  4997.9  716.63  4998.3  716.13  5002.1  716.63  5004.3  718.87
  5026.7  718.97  5049.0  718.44  5057.4  716.63  5063.0  718.38  5085.3  716.90
  5093.7  718.24  5130.1  719.12  5152.4  721.44  5191.6  722.42  5197.2  723.81
  5205.5  728.72  5213.9  736.19  5219.5  740.16  5225.1  745.90  5227.9  745.90
#Mann=3,-1,0
  4532.6    0.15       0  4997.9    0.05       0  5002.1    0.15       0
Bank Sta=4997.9,5002.1
Exp/Cntr=0.3,0.1

Type RM Length L Ch R = 1,7228,457,457,457
BEGIN DESCRIPTION:
S26 12.0
END DESCRIPTION:
XS GIS Cut Line= 3
      2320879.01      7053209.98      2320979.00      7053060.00
      2320929.00      7052659.97
#Sta/Elev= 30
  4824.5  741.09  4827.5  741.09  4832.0  736.03  4838.0  731.44  4847.0  726.16
  4853.0  721.65  4860.5  717.67  4896.6  715.19  4991.2  716.44  4997.2  716.18
  4997.9  714.05  4998.3  713.55  5002.1  714.05  5004.8  716.13  5014.8  716.03
  5035.0  714.05  5042.5  715.59  5055.1  716.22  5115.6  716.02  5123.2  717.22
  5155.9  718.77  5284.4  723.32  5327.2  724.04  5337.3  724.99  5347.4  730.34
  5357.5  736.95  5365.0  743.78  5370.1  743.49  5377.6  746.60  5407.9  746.71
#Mann=3,-1,0
  4824.5    0.15       0  4997.9    0.05       0  5002.1    0.15       0
Bank Sta=4997.9,5002.1
Exp/Cntr=0.3,0.1

Type RM Length L Ch R = 1,6771,1284,1284,1284
BEGIN DESCRIPTION:
S26 11.0
END DESCRIPTION:
XS GIS Cut Line= 3
      2320978.98      7053360.01      2321229.00      7053210.00
      2321279.00      7052709.96
#Sta/Elev= 30
  4709.0  743.30  4722.6  744.14  4732.3  740.36  4744.0  733.74  4753.7  725.45
  4759.6  726.11  4767.3  720.01  4775.1  717.15  4870.3  716.26  4934.5  714.03
  4965.6  713.79  4977.2  710.71  4987.0  711.14  4992.8  713.97  4997.7  713.79
  4997.9  710.71  4998.2  710.21  5001.8  710.21  5002.1  710.71  5003.1  713.79
  5010.6  713.97  5070.9  714.25  5091.0  713.79  5111.1  714.40  5131.2  713.88
  5254.3  715.94  5354.8  721.99  5422.7  728.62  5462.9  733.39  5503.1  735.92
#Mann=3,-1,0
  4709.0    0.15       0  4997.9    0.05       0  5002.1    0.15       0
Bank Sta=4997.9,5002.1
Exp/Cntr=0.3,0.1

Type RM Length L Ch R = 1,5487,440,440,440
BEGIN DESCRIPTION:
S26 10.0
END DESCRIPTION:
XS GIS Cut Line= 3
      2320928.98      7053410.00      2322029.00      7053610.00
      2322429.03      7053259.97
#Sta/Elev= 30
  3877.3  742.98  3938.3  742.83  3948.5  738.41  3957.4  731.06  3962.4  731.85
  3968.8  722.91  3979.0  718.01  3989.1  717.10  4686.6  707.91  4915.3  707.34
  4997.8  704.73  4998.2  704.23  5002.2  704.73  5066.1  708.40  5221.7  712.81
  5250.2  715.16  5264.4  717.97  5272.0  721.73  5278.7  722.05  5292.9  721.95
  5300.5  717.94  5307.1  719.29  5321.4  714.67  5328.0  718.77  5335.6  717.49
  5342.3  722.55  5364.1  722.95  5370.7  719.98  5385.0  719.41  5526.9  730.69
#Mann=3,-1,0
  3877.3    0.15       0  4997.8    0.05       0  5002.2    0.15       0
Bank Sta=4997.8,5002.2
Exp/Cntr=0.3,0.1

Type RM Length L Ch R = 1,5047,475,475,475
BEGIN DESCRIPTION:
S26 9.0
END DESCRIPTION:
XS GIS Cut Line= 3
      2321429.00      7054110.00      2321929.00      7053910.00
      2322228.98      7053660.02
#Sta/Elev= 30
  4462.4  713.99  4531.1  712.55  4656.3  711.54  4848.8  708.04  4961.9  703.34
  4979.4  702.03  4986.1  699.83  4997.7  698.86  4998.2  698.36  5002.3  698.86
  5004.2  698.86  5008.1  701.40  5043.2  702.85  5051.0  703.91  5079.0  704.64
  5170.8  705.93  5213.7  705.68  5228.1  704.72  5256.7  705.94  5285.3  705.89
  5291.9  706.88  5320.5  706.17  5327.0  707.31  5334.8  706.79  5349.1  707.71
  5363.4  707.12  5370.0  707.78  5384.3  711.86  5388.2  715.41  5391.4  715.41
#Mann=3,-1,0
  4462.4    0.15       0  4997.7    0.05       0  5002.3    0.15       0
Bank Sta=4997.7,5002.3
Exp/Cntr=0.3,0.1

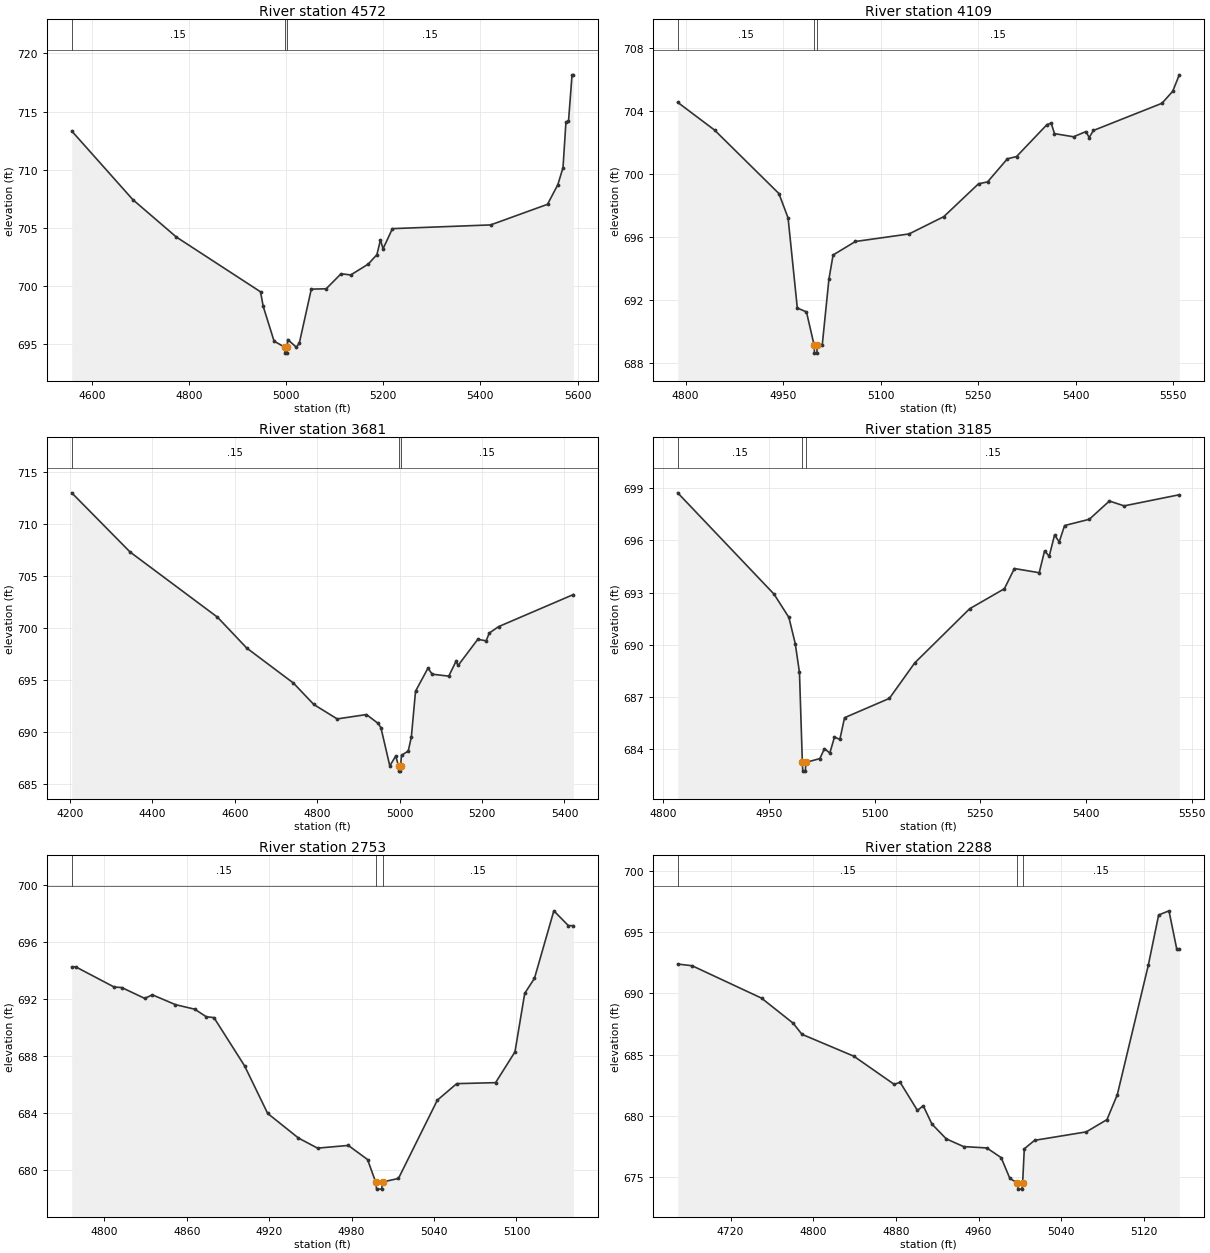
Type RM Length L Ch R = 1,4572,463,463,463
BEGIN DESCRIPTION:
S26 8.0
END DESCRIPTION:
XS GIS Cut Line= 3
      2322028.98      7054660.03      2322229.00      7054260.00
      2322429.01      7053709.98
#Sta/Elev= 30
  4558.8  713.33  4684.6  707.43  4774.1  704.22  4947.4  699.51  4952.9  698.26
  4975.3  695.27  4997.7  694.74  4998.2  694.24  5001.9  694.24  5002.4  694.74
  5003.3  695.41  5021.3  694.74  5027.3  695.11  5051.9  699.74  5082.5  699.77
  5113.1  701.06  5133.1  700.96  5169.0  701.89  5186.9  702.70  5194.3  703.97
  5199.6  703.21  5218.9  704.94  5421.0  705.26  5538.1  707.03  5559.4  708.72
  5570.0  710.18  5576.0  714.07  5581.3  714.15  5588.6  718.16  5591.3  718.16
#Mann=3,-1,0
  4558.8    0.15       0  4997.7    0.05       0  5002.4    0.15       0
Bank Sta=4997.7,5002.4
Exp/Cntr=0.3,0.1

Type RM Length L Ch R = 1,4109,428,428,428
BEGIN DESCRIPTION:
S26 7.0
END DESCRIPTION:
XS GIS Cut Line= 3
      2322378.97      7054710.03      2322529.00      7054560.00
      2322629.00      7054009.99
#Sta/Elev= 30
  4787.9  704.55  4844.5  702.79  4943.5  698.75  4957.6  697.20  4971.8  691.47
  4985.9  691.22  4997.7  689.10  4998.2  688.60  5001.9  688.60  5002.4  689.10
  5010.2  689.14  5020.4  693.30  5026.8  694.84  5061.1  695.70  5143.6  696.18
  5197.0  697.28  5250.4  699.37  5264.3  699.49  5294.8  700.96  5308.8  701.10
  5355.8  703.14  5362.2  703.22  5367.2  702.56  5396.5  702.36  5415.5  702.69
  5420.6  702.31  5427.0  702.76  5532.4  704.49  5548.9  705.25  5559.1  706.30
#Mann=3,-1,0
  4787.9    0.15       0  4997.7    0.05       0  5002.4    0.15       0
Bank Sta=4997.7,5002.4
Exp/Cntr=0.3,0.1

Type RM Length L Ch R = 1,3681,496,496,496
BEGIN DESCRIPTION:
S26 6.0
END DESCRIPTION:
XS GIS Cut Line= 3
      2322379.01      7055209.99      2322929.00      7054610.00
      2322979.00      7054210.04
#Sta/Elev= 30
  4204.6  713.01  4346.1  707.31  4558.2  701.03  4629.1  698.06  4742.6  694.68
  4791.9  692.62  4848.6  691.23  4919.6  691.65  4947.9  690.80  4954.7  690.39
  4976.3  686.70  4990.5  687.65  4997.6  686.70  4998.2  686.20  5001.9  686.20
  5002.4  686.70  5004.7  687.73  5021.0  688.13  5028.6  689.50  5038.7  693.90
  5068.9  696.12  5079.0  695.54  5119.3  695.35  5136.9  696.78  5142.0  696.38
  5189.8  698.90  5210.0  698.75  5217.6  699.50  5240.2  700.12  5421.6  703.21
#Mann=3,-1,0
  4204.6    0.15       0  4997.6    0.05       0  5002.4    0.15       0
Bank Sta=4997.6,5002.4
Exp/Cntr=0.3,0.1

Type RM Length L Ch R = 1,3185,432,432,432
BEGIN DESCRIPTION:
S26 5.0
END DESCRIPTION:
XS GIS Cut Line= 3
      2322778.98      7055160.01      2322929.00      7055060.00
      2323279.00      7054660.00
#Sta/Elev= 30
  4820.7  698.73  4957.4  692.91  4978.5  691.57  4987.5  690.07  4993.5  688.41
  4997.6  683.24  4998.2  682.74  5001.9  682.74  5002.5  683.24  5022.4  683.46
  5029.0  684.03  5036.6  683.78  5043.2  684.70  5050.8  684.56  5057.5  685.81
  5121.1  686.92  5157.1  688.96  5235.0  692.07  5284.3  693.22  5298.5  694.38
  5333.7  694.14  5341.3  695.39  5347.9  695.09  5355.5  696.31  5362.1  695.91
  5369.7  696.85  5404.8  697.21  5433.3  698.26  5454.2  697.98  5532.5  698.62
#Mann=3,-1,0
  4820.7    0.15       0  4997.6    0.05       0  5002.5    0.15       0
Bank Sta=4997.6,5002.5
Exp/Cntr=0.3,0.1

Type RM Length L Ch R = 1,2753,465,465,465
BEGIN DESCRIPTION:
S26 4.0
END DESCRIPTION:
XS GIS Cut Line= 3
      2322978.96      7055410.02      2323179.00      7055310.00
      2323279.02      7055209.98
#Sta/Elev= 30
  4776.3  694.27  4779.1  694.27  4807.1  692.85  4812.7  692.81  4829.4  692.05
  4835.0  692.30  4851.8  691.61  4865.8  691.29  4874.2  690.76  4879.8  690.70
  4902.1  687.31  4918.9  683.97  4941.3  682.24  4955.2  681.53  4977.6  681.72
  4991.6  680.73  4997.5  679.15  4998.2  678.65  5001.9  678.65  5002.5  679.15
  5014.1  679.40  5042.4  684.90  5056.5  686.06  5084.8  686.13  5098.9  688.29
  5106.0  692.40  5113.1  693.46  5127.2  698.20  5137.8  697.16  5141.4  697.16
#Mann=3,-1,0
  4776.3    0.15       0  4997.5    0.05       0  5002.5    0.15       0
Bank Sta=4997.5,5002.5
Exp/Cntr=0.3,0.1

Type RM Length L Ch R = 1,2288,432,432,432
BEGIN DESCRIPTION:
S26 3.0
END DESCRIPTION:
XS GIS Cut Line= 3
      2323179.00      7055760.00      2323479.00      7055610.00
      2323479.00      7055460.01
#Sta/Elev= 30
  4668.8  692.38  4682.8  692.24  4749.9  689.60  4780.6  687.55  4789.0  686.65
  4839.3  684.86  4878.4  682.56  4884.0  682.74  4900.8  680.44  4906.4  680.82
  4914.8  679.33  4928.7  678.12  4945.5  677.49  4967.9  677.38  4981.8  676.59
  4990.2  674.90  4997.5  674.52  4998.1  674.02  5001.9  674.02  5002.6  674.52
  5004.2  677.31  5014.2  678.00  5064.2  678.69  5084.2  679.69  5094.2  681.72
  5124.2  692.28  5134.2  696.38  5144.2  696.72  5151.7  693.62  5154.2  693.62
#Mann=3,-1,0
  4668.8    0.15       0  4997.5    0.05       0  5002.6    0.15       0
Bank Sta=4997.5,5002.6
Exp/Cntr=0.3,0.1

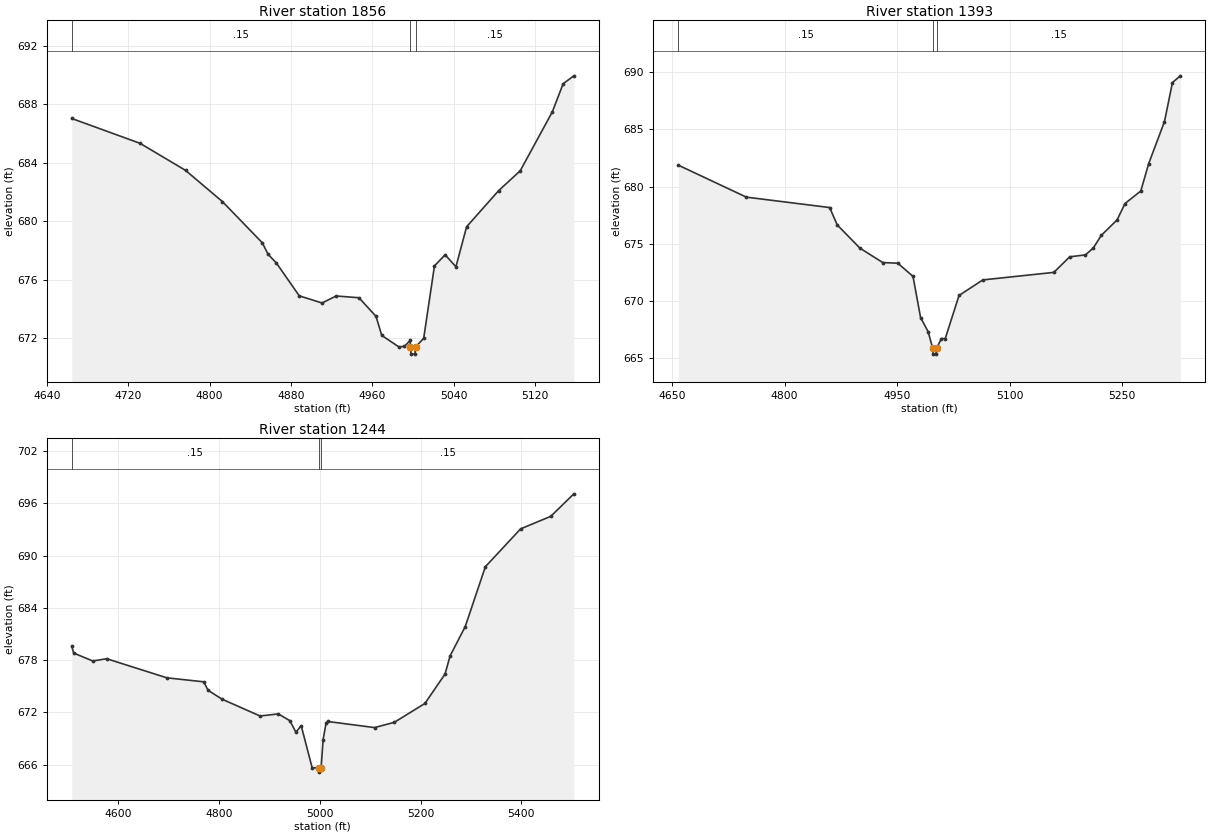
Type RM Length L Ch R = 1,1856,463,463,463
BEGIN DESCRIPTION:
S26 2.0
END DESCRIPTION:
XS GIS Cut Line= 3
      2323479.01      7055960.00      2323779.00      7055810.00
      2323829.00      7055660.01
#Sta/Elev= 30
  4664.6  687.04  4731.7  685.34  4776.4  683.49  4812.7  681.35  4851.9  678.53
  4857.5  677.75  4865.8  677.14  4888.2  674.90  4910.6  674.41  4924.5  674.89
  4946.9  674.77  4963.7  673.49  4969.3  672.19  4986.0  671.41  4991.6  671.44
  4997.2  671.85  4997.5  671.41  4998.1  670.91  5001.9  670.91  5002.6  671.41
  5010.5  671.99  5021.1  676.95  5031.6  677.71  5042.2  676.89  5052.7  679.63
  5084.3  682.11  5105.4  683.46  5137.0  687.50  5147.6  689.42  5158.1  689.96
#Mann=3,-1,0
  4664.6    0.15       0  4997.5    0.05       0  5002.6    0.15       0
Bank Sta=4997.5,5002.6
Exp/Cntr=0.3,0.1

Type RM Length L Ch R = 1,1393,149,149,149
BEGIN DESCRIPTION:
S26 1.0
END DESCRIPTION:
XS GIS Cut Line= 3
      2323678.99      7056210.00      2324029.00      7056160.00
      2324129.00      7055859.99
#Sta/Elev= 30
  4658.0  681.88  4748.9  679.08  4860.0  678.17  4870.1  676.65  4900.4  674.62
  4930.8  673.36  4951.0  673.30  4971.2  672.15  4981.3  668.55  4991.4  667.31
  4997.5  665.85  4998.1  665.35  5001.9  665.35  5002.6  665.85  5009.0  666.71
  5014.2  666.71  5032.6  670.48  5064.3  671.84  5159.1  672.50  5180.2  673.86
  5201.3  674.03  5211.8  674.64  5222.4  675.74  5243.5  677.09  5254.0  678.52
  5275.1  679.62  5285.6  682.01  5306.7  685.69  5317.3  689.10  5327.8  689.69
#Mann=3,-1,0
  4658.0    0.15       0  4997.5    0.05       0  5002.6    0.15       0
Bank Sta=4997.5,5002.6
Exp/Cntr=0.3,0.1

Type RM Length L Ch R = 1,1244,0,0,0
BEGIN DESCRIPTION:
1031
END DESCRIPTION:
XS GIS Cut Line= 3
      2323718.70      7056445.76      2324166.26      7056201.64
      2324158.14      7055714.22
#Sta/Elev= 30
  4507.3  679.59  4511.1  678.81  4549.1  677.90  4576.6  678.16  4696.2  675.97
  4769.6  675.51  4777.9  674.55  4805.4  673.53  4881.3  671.59  4917.7  671.83
  4940.5  671.05  4952.5  669.73  4963.0  670.48  4984.8  665.65  4997.4  665.65
  4998.1  665.15  5002.6  665.65  5006.6  668.89  5012.3  670.74  5015.8  670.96
  5108.8  670.26  5148.2  670.87  5208.8  673.03  5248.8  676.41  5258.8  678.49
  5288.8  681.84  5328.8  688.71  5398.8  693.06  5458.8  694.50  5504.6  697.08
#Mann=3,-1,0
  4507.3    0.15       0  4997.4    0.05       0  5002.6    0.15       0
Bank Sta=4997.4,5002.6
Exp/Cntr=0.3,0.1

Chan Stop Cuts=-1