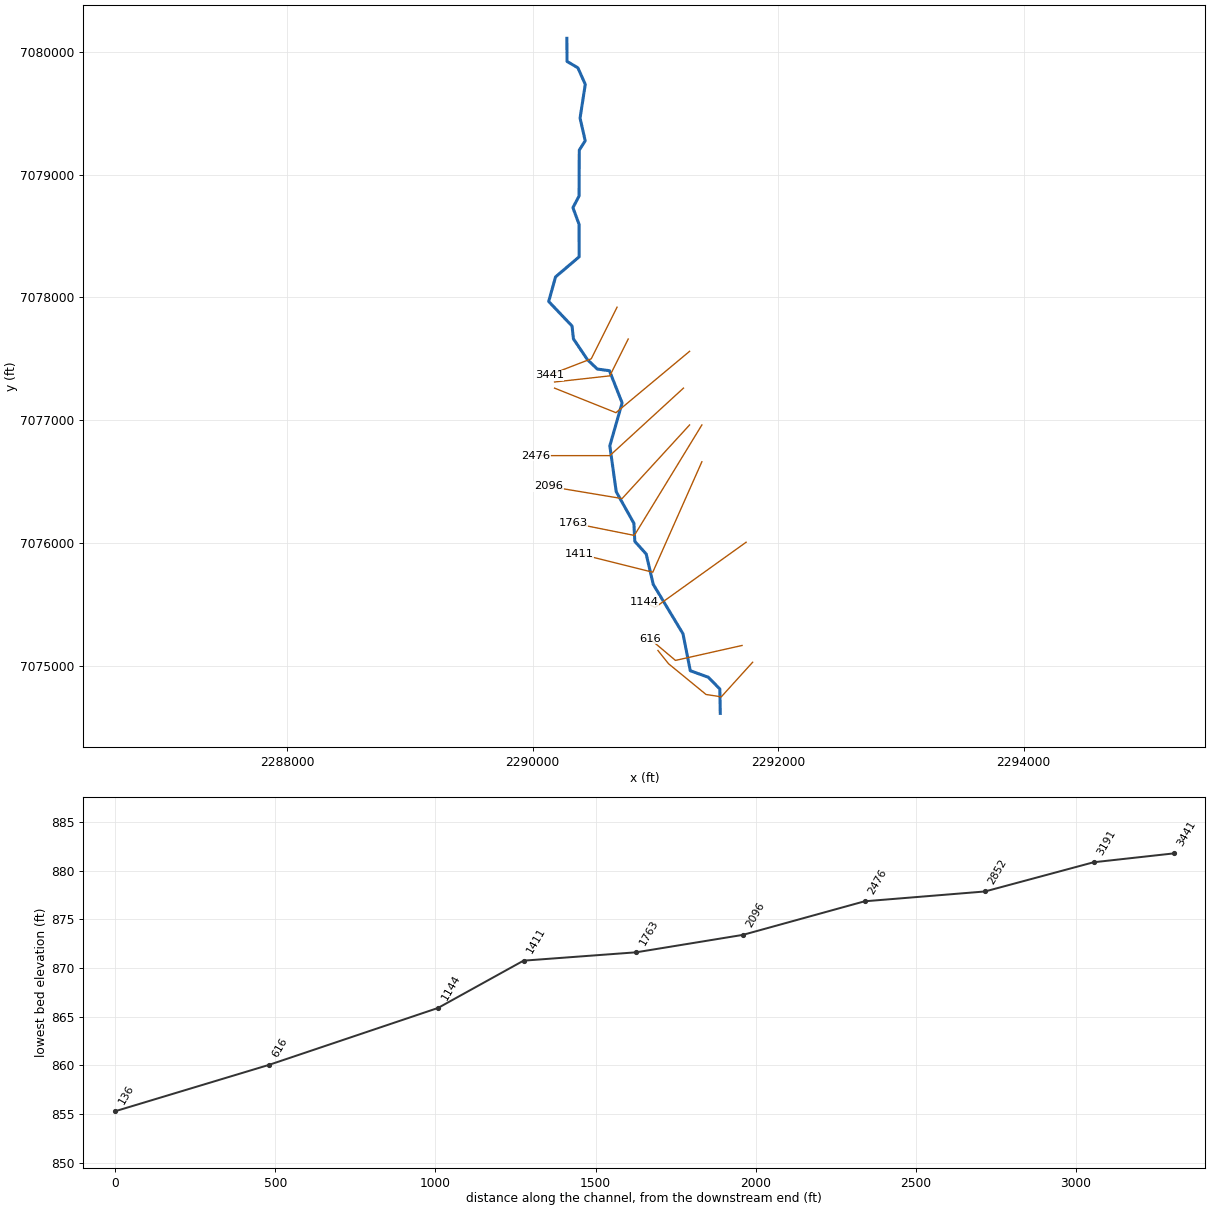
--- S4.prj (project) ---

Proj Title=S4 Base Level Engineering
Current Plan=p01
Default Exp/Contr=0.3,0.1
English Units
Geom File=g01
Flow File=f01
Plan File=p01
BEGIN DESCRIPTION:
S4
END DESCRIPTION:

--- S4.p01 (plan) ---

Plan Title=Multiple Run
Short Identifier=Multiple
Geom File=g01
Flow File=f01
Subcritical Flow
K Sum by GR= 0
Std Step Tol= 0.01
Critical Tol= 0.01
Num of Std Step Trials= 20
Max Error Tol= 0.3
Flow Tol Ratio= 0.001
Split Flow NTrial= 30
Split Flow Tol= 0.02
Split Flow Ratio= 0.02
Log Output Level= 0
Friction Slope Method= 1
Unsteady Friction Slope Method= 2
Unsteady Bridges Friction Slope Method= 1
Parabolic Critical Depth
Global Vel Dist=  1 , 1 , 1
Global Log Level= 0
CheckData=True
Encroach Param= -1, 0, 0, 0
BEGIN DESCRIPTION:
Multiple Run
END DESCRIPTION:

--- S4.f01 (steady flow) ---

Flow Title=Multiple
Number of Profiles=7
Profile Names=10-year,25-year,50-year,1pct_min,100-year,1pct_plu,500-year
River Rch & RM= S4,Reach-1,3441
     522     707     857     516    1030    2050    1490
River Rch & RM= S4,Reach-1,1144
     604     826    1010     611    1220    2430    1790
Boundary for River Rch & Prof#=S4,Reach-1,1
Up Type=0
Dn Type=3
Dn Slope=0.005
Boundary for River Rch & Prof#=S4,Reach-1,2
Up Type=0
Dn Type=3
Dn Slope=0.005
Boundary for River Rch & Prof#=S4,Reach-1,3
Up Type=0
Dn Type=3
Dn Slope=0.005
Boundary for River Rch & Prof#=S4,Reach-1,4
Up Type=0
Dn Type=3
Dn Slope=0.005
Boundary for River Rch & Prof#=S4,Reach-1,5
Up Type=0
Dn Type=3
Dn Slope=0.005
Boundary for River Rch & Prof#=S4,Reach-1,6
Up Type=0
Dn Type=3
Dn Slope=0.005
Boundary for River Rch & Prof#=S4,Reach-1,7
Up Type=0
Dn Type=3
Dn Slope=0.005

--- S4.g01 (geometry) ---

Geom Title=Existing Conditions

River Reach=S4,Reach-1
Reach XY= 30
      2290279.00      7080110.00      2290280.63      7079921.82
      2290368.54      7079870.04      2290429.12      7079735.12
      2290386.56      7079460.00      2290428.49      7079275.22
      2290380.22      7079199.50      2290378.48      7078825.22
      2290328.41      7078730.05      2290378.48      7078594.78
      2290379.09      7078329.88      2290186.87      7078166.14
      2290130.93      7077965.97      2290321.14      7077766.17
      2290332.63      7077661.50      2290445.64      7077493.29
      2290526.62      7077415.55      2290625.97      7077401.99
      2290729.29      7077139.83      2290629.05      7076789.96
      2290681.24      7076415.93      2290825.24      7076158.44
      2290832.56      7076011.47      2290925.38      7075908.50
      2290982.62      7075661.50      2291225.25      7075258.45
      2291284.71      7074957.42      2291431.44      7074904.48
      2291525.48      7074808.55      2291529.00      7074610.00

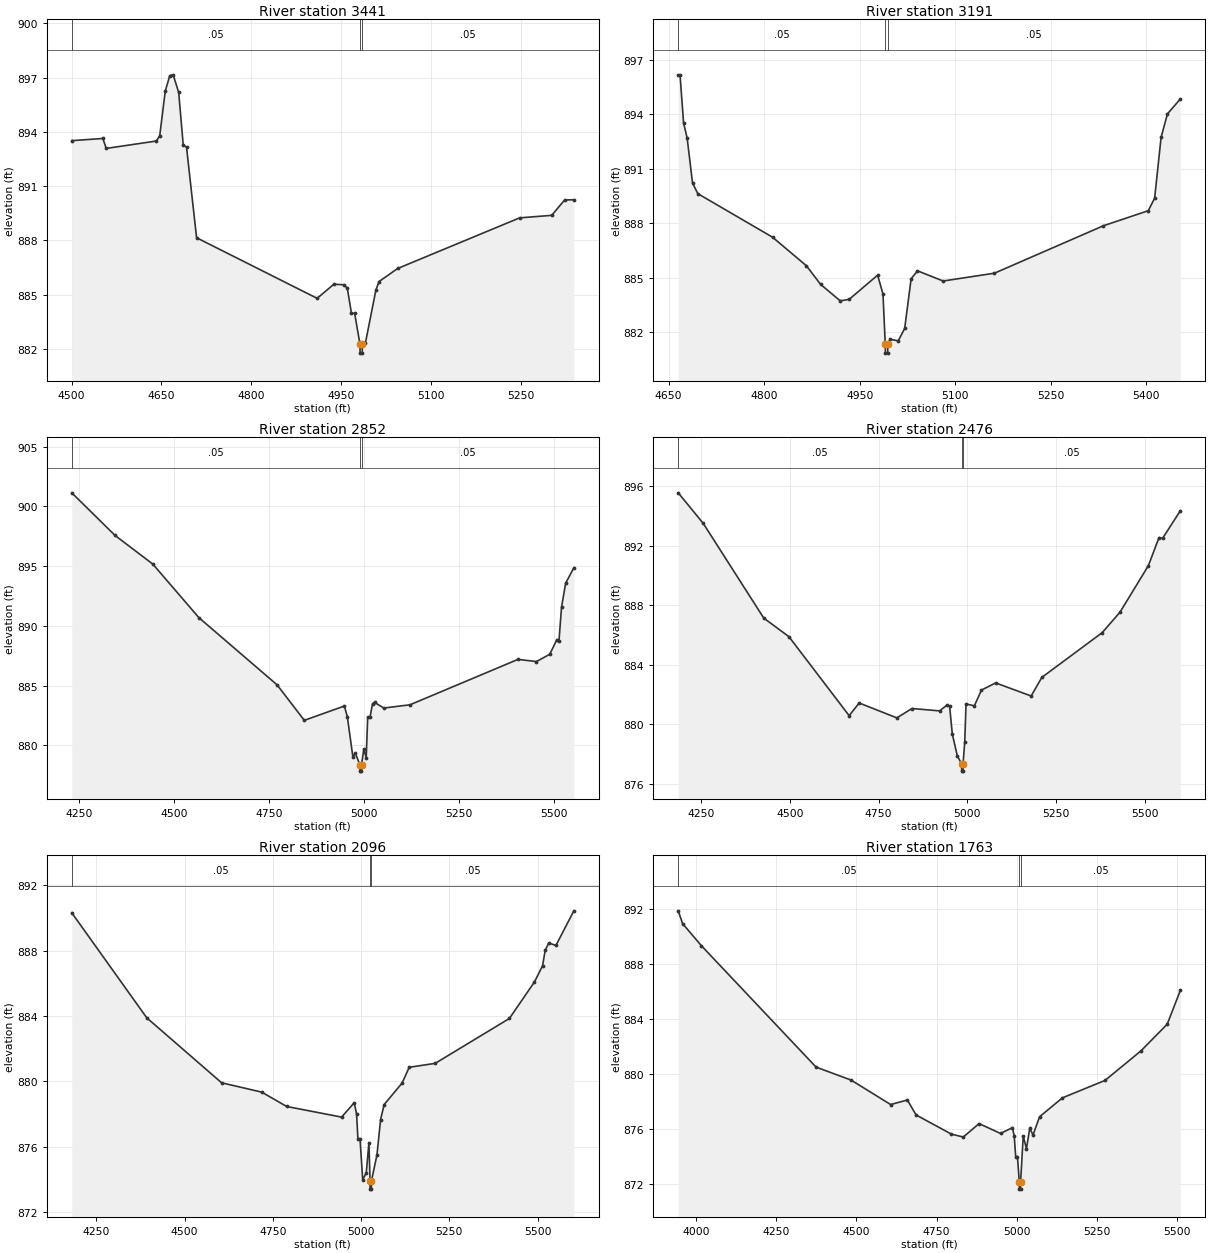
Type RM Length L Ch R = 1,3441,250,250,250
BEGIN DESCRIPTION:
1099
END DESCRIPTION:
XS GIS Cut Line= 3
      2290688.09      7077919.65      2290477.75      7077498.96
      2290134.59      7077366.13
#Sta/Elev= 30
  4500.2  893.51  4552.1  893.63  4557.7  893.08  4641.5  893.49  4647.1  893.79
  4656.3  896.25  4663.9  897.11  4669.5  897.15  4678.7  896.18  4686.3  893.27
  4691.8  893.15  4708.6  888.14  4909.9  884.79  4937.8  885.57  4954.6  885.54
  4960.2  885.36  4967.2  883.96  4972.5  883.96  4981.4  882.26  4981.6  881.76
  4985.1  881.76  4985.4  882.26  4990.6  882.34  5008.0  885.25  5013.3  885.72
  5044.3  886.44  5248.0  889.24  5301.6  889.38  5323.1  890.23  5338.5  890.24
#Mann=3,-1,0
  4500.2    0.05       0  4981.4    0.04       0  4985.4    0.05       0
Bank Sta=4981.4,4985.4
Exp/Cntr=0.3,0.1

Type RM Length L Ch R = 1,3191,339,339,339
BEGIN DESCRIPTION:
S4 6.0
END DESCRIPTION:
XS GIS Cut Line= 3
      2290779.00      7077659.99      2290629.00      7077360.00
      2290178.97      7077310.00
#Sta/Elev= 30
  4665.0  896.17  4667.8  896.17  4673.4  893.52  4679.0  892.69  4687.4  890.22
  4695.7  889.63  4813.1  887.23  4866.2  885.66  4888.6  884.63  4919.3  883.73
  4933.3  883.81  4978.0  885.14  4986.4  884.11  4990.0  881.35  4990.3  880.85
  4993.8  880.85  4994.0  881.35  4997.6  881.61  5010.5  881.53  5020.5  882.21
  5030.6  884.94  5040.6  885.38  5080.9  884.82  5161.4  885.25  5332.4  887.86
  5402.9  888.69  5412.9  889.38  5423.0  892.72  5433.0  894.02  5453.2  894.84
#Mann=3,-1,0
  4665.0    0.05       0  4990.0   0.033       0  4994.0    0.05       0
Bank Sta=4990,4994
Exp/Cntr=0.3,0.1

Type RM Length L Ch R = 1,2852,376,376,376
BEGIN DESCRIPTION:
S4 5.0
END DESCRIPTION:
XS GIS Cut Line= 3
      2291279.03      7077560.02      2290679.00      7077060.00
      2290178.98      7077260.01
#Sta/Elev= 30
  4231.6  901.14  4345.5  897.57  4444.5  895.18  4565.5  890.70  4771.2  885.07
  4842.8  882.10  4948.2  883.30  4956.0  882.37  4970.4  879.05  4976.9  879.36
  4989.2  878.35  4989.4  877.85  4992.9  877.85  4993.2  878.35  4999.0  879.69
  5005.5  878.98  5009.4  882.36  5015.4  882.36  5022.1  883.49  5027.5  883.60
  5051.7  883.13  5120.4  883.40  5404.4  887.20  5452.9  887.02  5487.9  887.63
  5506.7  888.86  5512.1  888.74  5518.9  891.58  5529.6  893.57  5551.2  894.87
#Mann=3,-1,0
  4231.6    0.05       0  4989.2   0.033       0  4993.2    0.05       0
Bank Sta=4989.2,4993.2
Exp/Cntr=0.3,0.1

Type RM Length L Ch R = 1,2476,380,380,380
BEGIN DESCRIPTION:
S4 4.0
END DESCRIPTION:
XS GIS Cut Line= 3
      2291228.99      7077259.99      2290629.00      7076710.00
      2290029.03      7076710.00
#Sta/Elev= 30
  4185.6  895.55  4256.2  893.49  4426.4  887.13  4497.3  885.88  4666.9  880.57
  4695.2  881.42  4801.3  880.42  4843.8  881.05  4921.5  880.89  4943.1  881.29
  4949.9  881.20  4957.3  879.35  4971.5  877.86  4983.7  877.34  4983.9  876.84
  4987.4  876.84  4987.7  877.34  4992.4  878.81  4996.1  881.36  5019.5  881.23
  5039.5  882.29  5079.5  882.77  5179.5  881.89  5209.5  883.14  5379.5  886.15
  5429.5  887.52  5509.5  890.65  5539.5  892.54  5549.5  892.49  5599.5  894.34
#Mann=3,-1,0
  4185.6    0.05       0  4983.7   0.035       0  4987.7    0.05       0
Bank Sta=4983.7,4987.7
Exp/Cntr=0.3,0.1

Type RM Length L Ch R = 1,2096,333,333,333
BEGIN DESCRIPTION:
S4 3.0
END DESCRIPTION:
XS GIS Cut Line= 3
      2291278.99      7076959.99      2290729.00      7076360.00
      2290129.00      7076460.00
#Sta/Elev= 30
  4180.5  890.31  4392.9  883.88  4605.0  879.90  4718.5  879.33  4789.4  878.45
  4944.8  877.80  4980.6  878.68  4987.3  877.98  4991.0  876.48  4997.0  876.48
  5004.6  873.96  5014.7  874.39  5022.3  876.23  5025.4  873.89  5025.6  873.39
  5029.1  873.39  5029.4  873.89  5045.1  875.50  5055.3  877.65  5065.4  878.57
  5116.1  879.88  5136.4  880.85  5209.9  881.09  5420.2  883.84  5491.2  886.08
  5514.0  887.06  5521.6  888.02  5531.7  888.46  5552.0  888.31  5602.7  890.43
#Mann=3,-1,0
  4180.5    0.05       0  5025.4   0.033       0  5029.4    0.05       0
Bank Sta=5025.4,5029.4
Exp/Cntr=0.3,0.1

Type RM Length L Ch R = 1,1763,352,352,352
BEGIN DESCRIPTION:
S4 2.0
END DESCRIPTION:
XS GIS Cut Line= 3
      2291379.00      7076960.00      2290829.00      7076060.00
      2290328.95      7076160.01
#Sta/Elev= 30
  3944.9  891.90  3958.5  890.97  4016.5  889.37  4374.5  880.50  4484.0  879.55
  4606.8  877.77  4659.0  878.10  4686.2  877.01  4796.4  875.61  4833.2  875.40
  4882.5  876.38  4949.3  875.66  4986.1  876.08  4991.9  875.51  4996.7  873.94
  5002.2  873.94  5007.8  872.10  5008.1  871.60  5011.6  871.60  5011.8  872.10
  5020.0  875.48  5030.2  874.55  5040.4  876.05  5050.6  875.55  5071.0  876.88
  5142.4  878.26  5275.0  879.53  5387.2  881.69  5468.8  883.63  5509.6  886.09
#Mann=3,-1,0
  3944.9    0.05       0  5007.8   0.033       0  5011.8    0.05       0
Bank Sta=5007.8,5011.8
Exp/Cntr=0.3,0.1

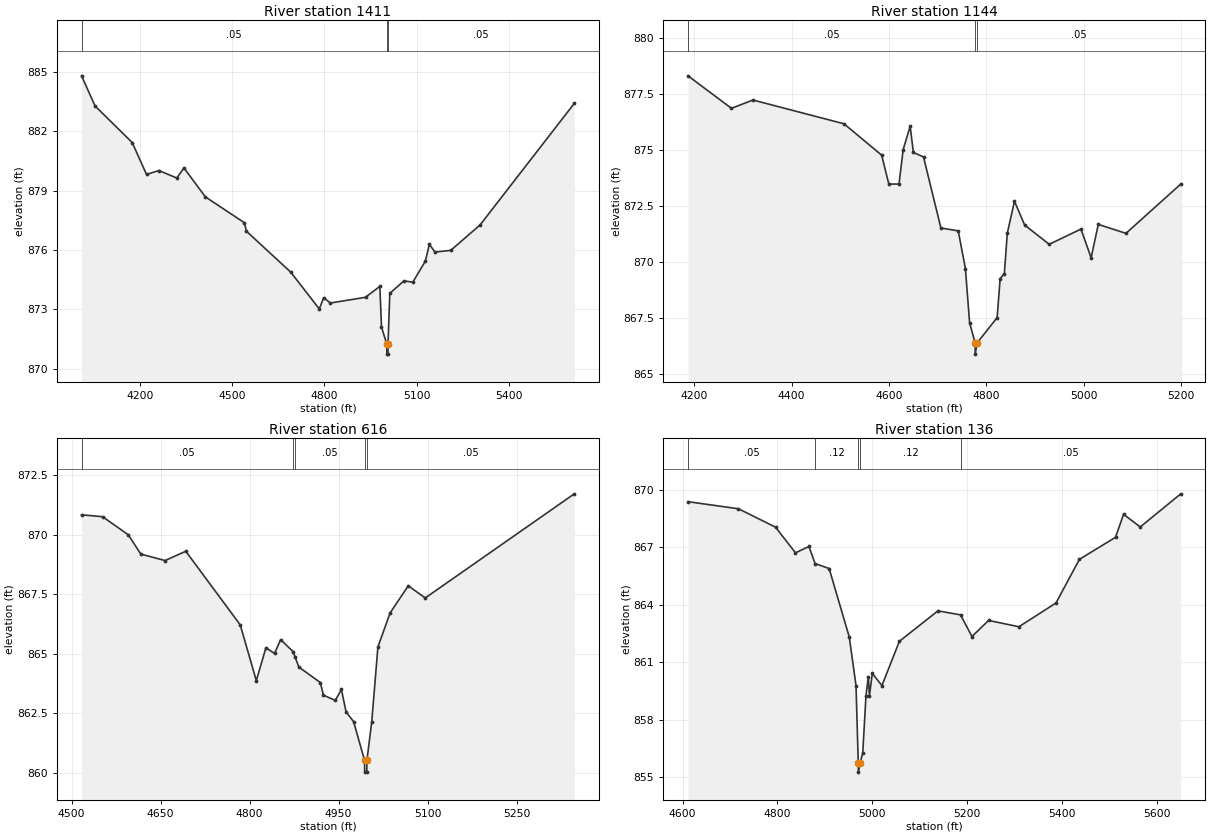
Type RM Length L Ch R = 1,1411,267,267,267
BEGIN DESCRIPTION:
S4 1.0
END DESCRIPTION:
XS GIS Cut Line= 3
      2291379.01      7076660.03      2290979.00      7075760.00
      2290378.98      7075910.00
#Sta/Elev= 30
  4009.6  884.79  4053.4  883.27  4174.5  881.42  4221.0  879.81  4261.3  880.01
  4319.5  879.63  4342.7  880.14  4412.5  878.68  4539.7  877.37  4545.8  876.95
  4690.2  874.88  4783.2  873.02  4797.5  873.59  4819.4  873.32  4933.6  873.61
  4980.2  874.16  4985.6  872.11  5002.8  871.24  5003.1  870.74  5006.6  870.74
  5006.8  871.24  5012.6  873.81  5058.9  874.44  5087.3  874.37  5128.5  875.44
  5141.4  876.29  5159.4  875.89  5211.0  875.98  5306.3  877.26  5613.0  883.40
#Mann=3,-1,0
  4009.6    0.05       0  5002.8   0.033       0  5006.8    0.05       0
Bank Sta=5002.8,5006.8
Exp/Cntr=0.3,0.1

Type RM Length L Ch R = 1,1144,528,528,528
BEGIN DESCRIPTION:
1098
END DESCRIPTION:
XS GIS Cut Line= 3
      2291739.65      7076004.54      2290998.02      7075473.23
      2290909.48      7075517.50
#Sta/Elev= 30
  4187.5  878.30  4276.6  876.85  4320.8  877.22  4507.5  876.16  4584.9  874.76
  4599.6  873.47  4620.5  873.47  4629.1  875.01  4643.4  876.05  4650.0  874.88
  4670.8  874.68  4706.5  871.51  4742.1  871.38  4756.8  869.70  4765.4  867.28
  4776.7  866.38  4777.0  865.88  4780.8  866.38  4821.9  867.51  4828.1  869.25
  4836.7  869.47  4842.8  871.28  4857.5  872.70  4878.4  871.64  4928.8  870.78
  4993.9  871.46  5014.8  870.18  5029.5  871.67  5086.3  871.27  5198.8  873.47
#Mann=3,-1,0
  4187.5    0.05       0  4776.7   0.033       0  4780.8    0.05       0
Bank Sta=4776.7,4780.8
Exp/Cntr=0.3,0.1

Type RM Length L Ch R = 1,616,480,480,480
BEGIN DESCRIPTION:
1097
END DESCRIPTION:
XS GIS Cut Line= 3
      2291706.43      7075163.27      2291164.06      7075041.51
      2290953.83      7075218.55
#Sta/Elev= 30
  4516.7  870.83  4552.2  870.75  4595.5  869.99  4616.6  869.18  4657.5  868.91
  4692.4  869.30  4784.2  866.21  4811.3  863.87  4827.5  865.25  4842.0  865.01
  4852.3  865.59  4873.2  865.09  4876.4  864.88  4883.0  864.44  4919.3  863.79
  4924.4  863.26  4944.5  863.04  4954.8  863.50  4962.6  862.56  4975.3  862.15
  4993.7  860.53  4994.0  860.03  4997.5  860.03  4997.8  860.53  5005.9  862.14
  5016.3  865.28  5036.8  866.71  5067.5  867.85  5096.1  867.34  5347.4  871.71
#Mann=5,-1,0
  4516.7    0.05       0  4873.2    0.12       0  4876.4    0.05       0
  4993.7   0.033       0  4997.8    0.05       0
Bank Sta=4993.7,4997.8
Exp/Cntr=0.3,0.1

Type RM Length L Ch R = 1,136,0,0,0
BEGIN DESCRIPTION:
S4  0.1
END DESCRIPTION:
XS GIS Cut Line= 5
      2291792.82      7075026.74      2291537.19      7074744.84
      2291412.96      7074763.95      2291107.14      7075014.81
      2291021.11      7075122.35
#Sta/Elev= 30
  4611.5  869.39  4717.9  869.02  4796.1  868.06  4838.2  866.72  4866.6  867.05
  4879.5  866.16  4909.2  865.90  4951.7  862.32  4965.9  859.79  4970.6  855.77
  4970.9  855.27  4974.8  855.77  4980.1  856.27  4986.9  859.26  4991.9  860.25
  4994.2  859.26  5000.3  860.42  5020.6  859.79  5057.4  862.10  5138.7  863.69
  5186.4  863.48  5210.5  862.35  5245.6  863.19  5309.5  862.86  5387.7  864.10
  5437.2  866.38  5513.3  867.53  5530.3  868.73  5565.5  868.07  5651.0  869.80
#Mann=5,-1,0
  4611.5    0.05       0  4879.5    0.12       0  4970.6    0.07       0
  4974.8    0.12       0  5186.4    0.05       0
Bank Sta=4970.6,4974.8
Exp/Cntr=0.3,0.1

Chan Stop Cuts=-1