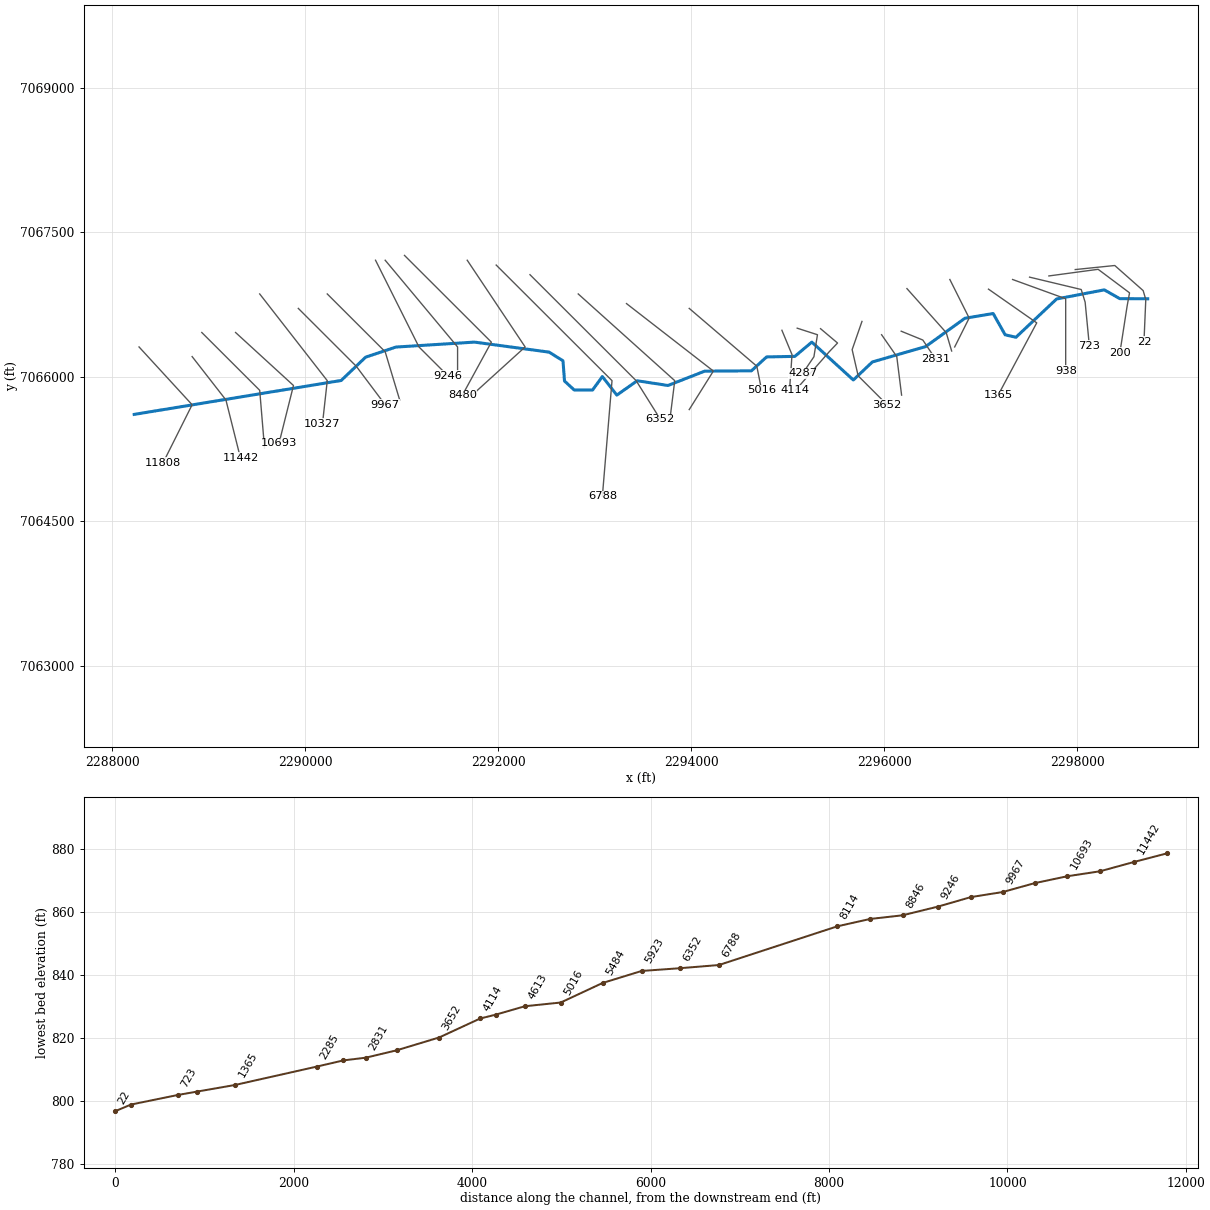
--- S52.prj (project) ---

Proj Title=S52 Base Level Engineering
Current Plan=p01
Default Exp/Contr=0.3,0.1
English Units
Geom File=g01
Flow File=f01
Plan File=p01
BEGIN DESCRIPTION:
S52
END DESCRIPTION:

--- S52.p01 (plan) ---

Plan Title=Multiple Run
Short Identifier=Multiple
Geom File=g01
Flow File=f01
Subcritical Flow
K Sum by GR= 0
Std Step Tol= 0.01
Critical Tol= 0.01
Num of Std Step Trials= 20
Max Error Tol= 0.3
Flow Tol Ratio= 0.001
Split Flow NTrial= 30
Split Flow Tol= 0.02
Split Flow Ratio= 0.02
Log Output Level= 0
Friction Slope Method= 1
Unsteady Friction Slope Method= 2
Unsteady Bridges Friction Slope Method= 1
Parabolic Critical Depth
Global Vel Dist=  1 , 1 , 1
Global Log Level= 0
CheckData=True
Encroach Param= -1, 0, 0, 0
BEGIN DESCRIPTION:
Multiple Run
END DESCRIPTION:

--- S52.f01 (steady flow) ---

Flow Title=Multiple
Number of Profiles=7
Profile Names=10-year,25-year,50-year,1pct_min,100-year,1pct_plu,500-year
River Rch & RM= S52,Reach-1,11808
     571     780     952     577    1150    2300    1690
River Rch & RM= S52,Reach-1,6788
     631     867    1060     646    1290    2570    1900
River Rch & RM= S52,Reach-1,6352
    1080    1520    1900    1180    2350    4690    3600
River Rch & RM= S52,Reach-1,2581
    1740    2520    3200    2010    4020    8010    6340
River Rch & RM= S52,Reach-1,22
    2930    4310    5520    3500    6980   13900   11200
Boundary for River Rch & Prof#=S52,Reach-1,1
Up Type=0
Dn Type=3
Dn Slope=0.005
Boundary for River Rch & Prof#=S52,Reach-1,2
Up Type=0
Dn Type=3
Dn Slope=0.005
Boundary for River Rch & Prof#=S52,Reach-1,3
Up Type=0
Dn Type=3
Dn Slope=0.005
Boundary for River Rch & Prof#=S52,Reach-1,4
Up Type=0
Dn Type=3
Dn Slope=0.005
Boundary for River Rch & Prof#=S52,Reach-1,5
Up Type=0
Dn Type=3
Dn Slope=0.005
Boundary for River Rch & Prof#=S52,Reach-1,6
Up Type=0
Dn Type=3
Dn Slope=0.005
Boundary for River Rch & Prof#=S52,Reach-1,7
Up Type=0
Dn Type=3
Dn Slope=0.005

--- S52.g01 (geometry) ---

Geom Title=Existing Conditions

River Reach=S52,Reach-1
Reach XY= 30
      2288229.00      7065610.00      2290373.15      7065962.06
      2290626.70      7066204.17      2290939.50      7066308.78
      2291753.92      7066360.20      2292527.42      7066256.18
      2292670.98      7066166.34      2292686.75      7065956.35
      2292787.43      7065863.40      2292977.75      7065863.45
      2293078.73      7066002.82      2293229.00      7065810.00
      2293439.33      7065959.13      2293758.97      7065910.07
      2294139.44      7066058.94      2294623.15      7066062.06
      2294780.46      7066206.46      2295073.10      7066212.23
      2295248.96      7066360.25      2295679.00      7065967.07
      2295876.55      7066154.53      2296427.53      7066313.55
      2296834.93      7066607.76      2297127.58      7066656.96
      2297251.81      7066436.02      2297363.72      7066410.36
      2297784.86      7066807.93      2298279.01      7066902.47
      2298439.50      7066811.20      2298729.00      7066810.00

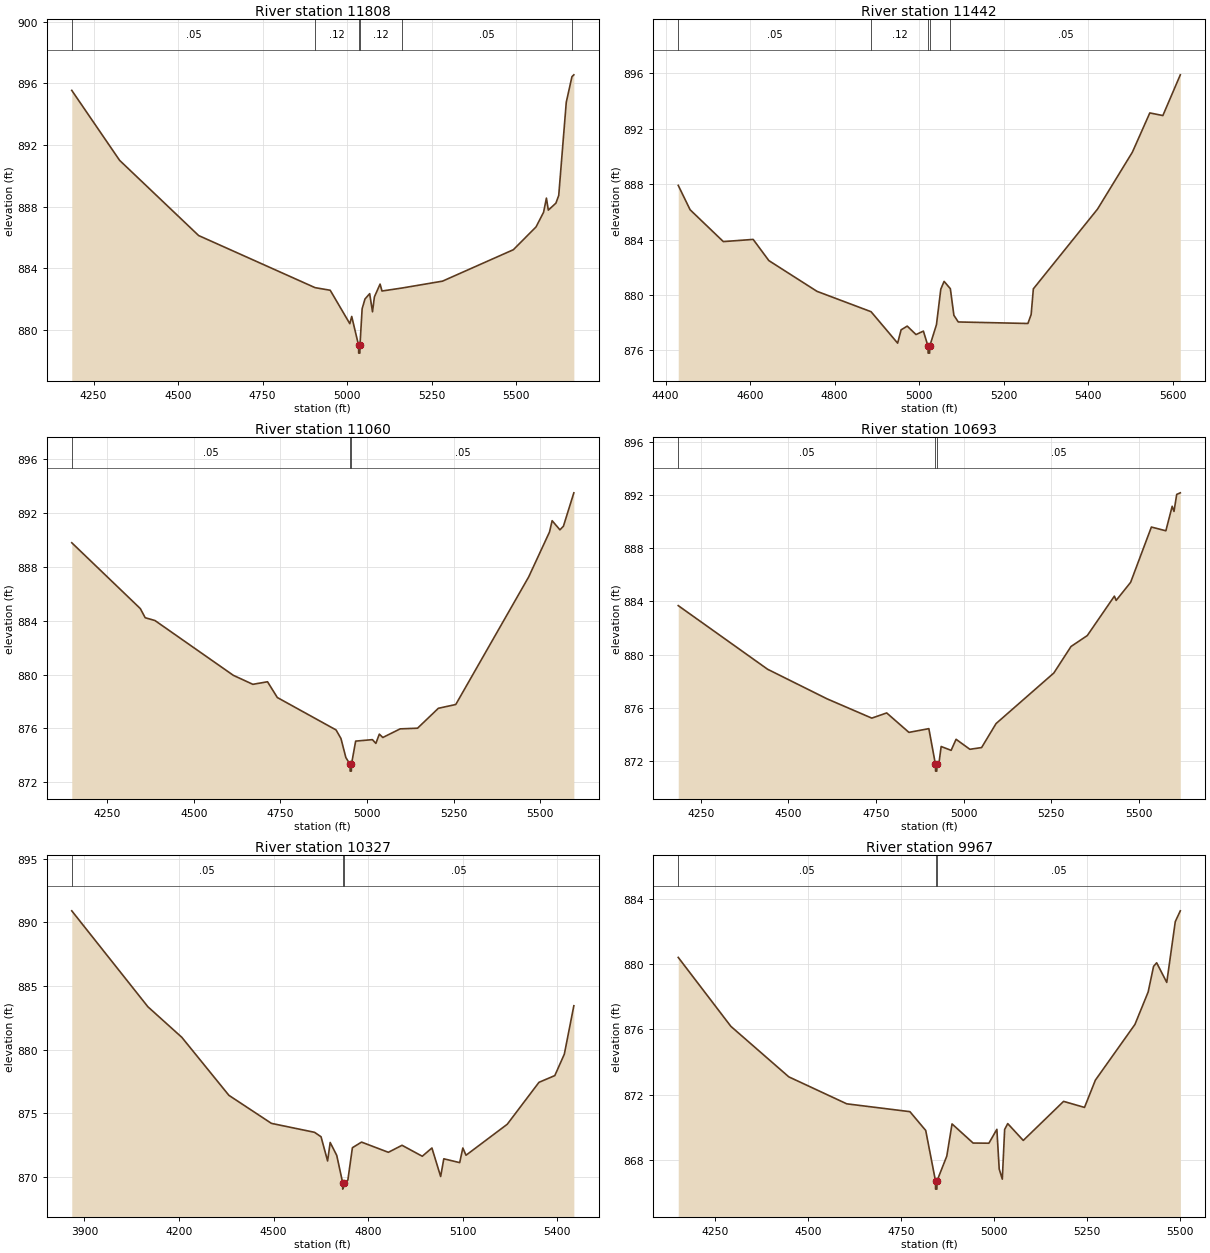
Type RM Length L Ch R = 1,11808,366,366,366
BEGIN DESCRIPTION:
S52 24.0
END DESCRIPTION:
XS GIS Cut Line= 3
      2288278.99      7066310.01      2288829.00      7065710.00
      2288528.99      7065109.98
#Sta/Elev= 30
  4185.6  895.55  4327.1  891.01  4560.8  886.13  4905.0  882.75  4949.9  882.58
  5007.9  880.41  5013.5  880.88  5033.9  879.00  5034.1  878.50  5037.6  878.50
  5037.9  879.00  5044.3  881.38  5052.7  882.01  5066.6  882.36  5075.0  881.18
  5080.6  882.15  5097.4  882.98  5103.0  882.53  5163.6  882.73  5281.9  883.17
  5491.5  885.21  5558.6  886.69  5580.9  887.64  5589.3  888.56  5594.9  887.78
  5617.3  888.23  5625.7  888.73  5648.0  894.78  5664.8  896.44  5670.4  896.56
#Mann=6,-1,0
  4185.6    0.05       0  4905.0    0.12       0  5033.9    0.07       0
  5037.9    0.12       0  5163.6    0.05       0  5664.8   0.075       0
Bank Sta=5033.9,5037.9
Exp/Cntr=0.3,0.1

Type RM Length L Ch R = 1,11442,382,382,382
BEGIN DESCRIPTION:
S52 23.0
END DESCRIPTION:
XS GIS Cut Line= 3
      2288828.99      7066210.02      2289179.00      7065760.00
      2289329.01      7065159.98
#Sta/Elev= 30
  4429.8  887.91  4457.9  886.15  4536.6  883.85  4607.2  884.01  4644.3  882.48
  4758.3  880.26  4886.3  878.79  4949.2  876.52  4957.4  877.48  4971.9  877.75
  4992.7  877.14  5010.2  877.39  5021.1  876.30  5021.4  875.80  5024.9  875.80
  5025.1  876.30  5041.1  877.85  5051.4  880.42  5059.2  880.98  5074.0  880.45
  5082.4  878.53  5092.7  878.05  5257.6  877.94  5265.3  878.59  5270.5  880.44
  5422.5  886.20  5505.0  890.31  5546.2  893.14  5577.1  892.95  5618.4  895.89
#Mann=5,-1,0
  4429.8    0.05       0  4886.3    0.12       0  5021.1    0.07       0
  5025.1    0.12       0  5074.0    0.05       0
Bank Sta=5021.1,5025.1
Exp/Cntr=0.3,0.1

Type RM Length L Ch R = 1,11060,367,367,367
BEGIN DESCRIPTION:
S52 22.0
END DESCRIPTION:
XS GIS Cut Line= 3
      2288929.03      7066459.97      2289529.00      7065860.00
      2289579.00      7065259.97
#Sta/Elev= 30
  4147.1  889.80  4345.1  884.91  4359.2  884.23  4387.5  884.02  4613.8  879.95
  4670.3  879.28  4712.7  879.47  4741.0  878.30  4910.7  875.89  4924.9  875.25
  4939.0  873.84  4951.2  873.33  4951.4  872.83  4954.9  872.83  4955.2  873.33
  4967.3  875.06  5015.7  875.17  5025.7  874.89  5035.7  875.58  5045.8  875.33
  5095.9  875.97  5146.1  876.02  5206.3  877.50  5256.5  877.78  5467.2  887.26
  5527.4  890.60  5535.0  891.44  5557.5  890.76  5567.6  891.03  5597.7  893.51
#Mann=3,-1,0
  4147.1    0.05       0  4951.2   0.033       0  4955.2    0.05       0
Bank Sta=4951.2,4955.2
Exp/Cntr=0.3,0.1

Type RM Length L Ch R = 1,10693,366,366,366
BEGIN DESCRIPTION:
S52 21.0
END DESCRIPTION:
XS GIS Cut Line= 3
      2289279.00      7066460.00      2289879.00      7065910.00
      2289729.00      7065310.01
#Sta/Elev= 30
  4186.1  883.68  4441.1  878.90  4610.6  876.68  4738.3  875.23  4780.8  875.62
  4844.3  874.16  4901.1  874.44  4920.0  871.75  4920.3  871.25  4923.8  871.25
  4924.0  871.75  4929.4  871.75  4936.2  873.10  4964.6  872.81  4978.8  873.64
  5018.1  872.89  5051.6  873.02  5092.8  874.82  5257.7  878.62  5306.7  880.61
  5353.1  881.43  5430.4  884.39  5435.5  884.07  5476.8  885.43  5536.0  889.58
  5577.3  889.30  5595.3  891.14  5600.5  890.75  5608.2  892.03  5618.5  892.15
#Mann=3,-1,0
  4186.1    0.05       0  4920.0   0.033       0  4924.0    0.05       0
Bank Sta=4920,4924
Exp/Cntr=0.3,0.1

Type RM Length L Ch R = 1,10327,360,360,360
BEGIN DESCRIPTION:
S52 20.0
END DESCRIPTION:
XS GIS Cut Line= 3
      2289528.99      7066860.02      2290229.00      7065960.00
      2290179.00      7065509.97
#Sta/Elev= 30
  3859.9  890.90  4101.5  883.37  4209.2  880.97  4358.5  876.42  4493.4  874.22
  4630.0  873.52  4650.8  873.17  4671.6  871.27  4679.8  872.72  4700.6  871.71
  4719.4  869.56  4719.6  869.06  4723.4  869.56  4735.9  869.77  4750.3  872.31
  4779.3  872.75  4864.4  871.95  4907.8  872.50  4972.0  871.64  5002.6  872.29
  5030.3  870.05  5040.3  871.44  5090.7  871.14  5100.7  872.29  5110.8  871.72
  5241.6  874.15  5342.2  877.44  5392.5  877.97  5422.7  879.65  5452.9  883.45
#Mann=3,-1,0
  3859.9    0.05       0  4719.4   0.033       0  4723.4    0.05       0
Bank Sta=4719.4,4723.4
Exp/Cntr=0.3,0.1

Type RM Length L Ch R = 1,9967,355,355,355
BEGIN DESCRIPTION:
S52 19.0
END DESCRIPTION:
XS GIS Cut Line= 3
      2289929.00      7066710.00      2290529.00      7066110.00
      2290828.98      7065710.03
#Sta/Elev= 30
  4151.5  880.41  4292.9  876.19  4448.5  873.10  4604.1  871.45  4773.8  870.97
  4816.2  869.82  4842.5  866.73  4842.7  866.23  4846.2  866.23  4846.5  866.73
  4872.8  868.25  4886.9  870.22  4943.5  869.05  4985.9  869.04  5007.3  869.89
  5013.6  867.46  5021.9  866.84  5028.2  869.88  5036.5  870.24  5078.2  869.21
  5186.5  871.60  5242.7  871.23  5271.9  872.90  5378.2  876.31  5413.6  878.29
  5428.2  879.86  5436.5  880.08  5463.6  878.88  5486.5  882.60  5500.0  883.26
#Mann=3,-1,0
  4151.5    0.05       0  4842.5   0.033       0  4846.5    0.05       0
Bank Sta=4842.5,4846.5
Exp/Cntr=0.3,0.1

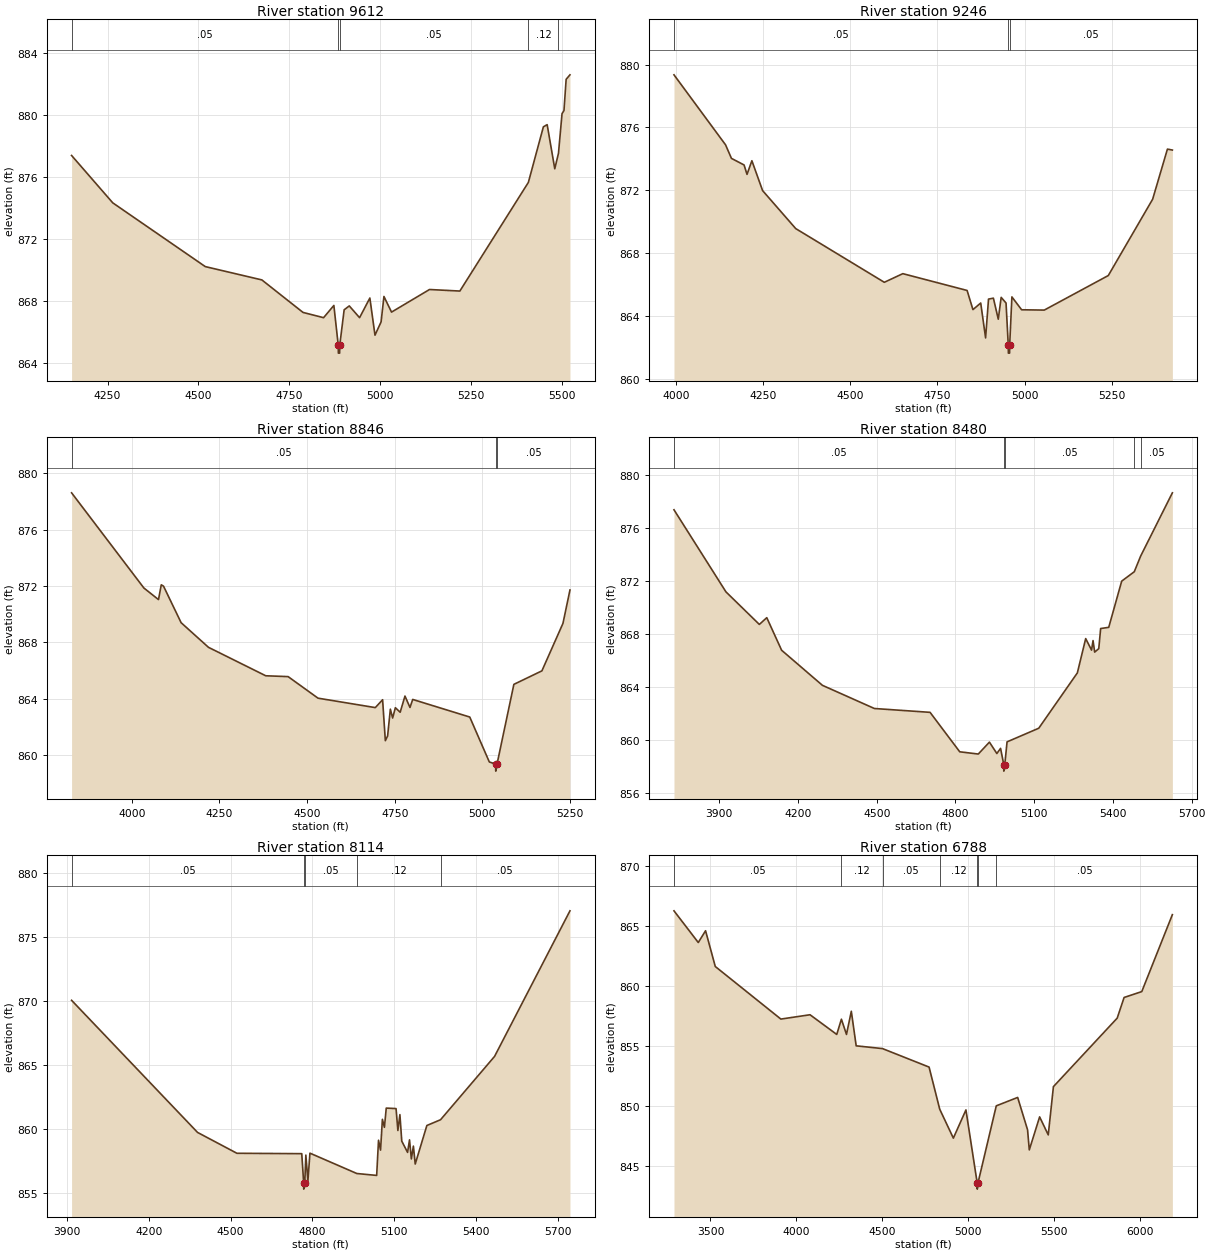
Type RM Length L Ch R = 1,9612,366,366,366
BEGIN DESCRIPTION:
S52 18.0
END DESCRIPTION:
XS GIS Cut Line= 3
      2290228.97      7066860.03      2290829.00      7066260.00
      2290979.00      7065759.99
#Sta/Elev= 30
  4151.1  877.40  4264.3  874.34  4518.8  870.22  4674.4  869.36  4787.5  867.26
  4844.1  866.92  4872.4  867.71  4884.5  865.13  4884.8  864.63  4888.3  864.63
  4888.5  865.13  4900.7  867.43  4914.8  867.68  4943.1  866.92  4971.4  868.19
  4985.5  865.79  5002.3  866.65  5010.1  868.29  5031.0  867.28  5135.4  868.74
  5218.9  868.64  5407.3  875.66  5448.6  879.25  5459.0  879.39  5479.9  876.54
  5490.1  877.54  5499.9  880.10  5505.2  880.30  5511.2  882.32  5521.7  882.61
#Mann=5,-1,0
  4151.1    0.05       0  4884.5   0.033       0  4888.5    0.05       0
  5407.3    0.12       0  5490.1    0.05       0
Bank Sta=4884.5,4888.5
Exp/Cntr=0.3,0.1

Type RM Length L Ch R = 1,9246,400,400,400
BEGIN DESCRIPTION:
S52 17.0
END DESCRIPTION:
XS GIS Cut Line= 3
      2290729.00      7067209.99      2291179.00      7066310.00
      2291479.01      7066009.99
#Sta/Elev= 30
  3993.8  879.35  4141.9  874.89  4158.7  874.03  4195.0  873.61  4203.4  873.01
  4217.4  873.88  4248.1  871.98  4343.2  869.56  4597.5  866.14  4650.6  866.69
  4835.1  865.62  4851.9  864.40  4874.2  864.82  4888.2  862.60  4896.6  865.07
  4910.6  865.13  4924.6  863.79  4932.9  865.18  4946.9  864.82  4953.3  862.13
  4953.6  861.63  4957.1  861.63  4957.3  862.13  4963.7  865.21  4991.6  864.39
  5056.6  864.37  5240.4  866.57  5367.7  871.43  5410.1  874.62  5424.3  874.56
#Mann=3,-1,0
  3993.8    0.05       0  4953.3   0.033       0  4957.3    0.05       0
Bank Sta=4953.3,4957.3
Exp/Cntr=0.3,0.1

Type RM Length L Ch R = 1,8846,366,366,366
BEGIN DESCRIPTION:
S52 16.0
END DESCRIPTION:
XS GIS Cut Line= 3
      2290829.02      7067209.98      2291579.00      7066310.00
      2291579.00      7066060.01
#Sta/Elev= 30
  3828.4  878.61  4034.7  871.85  4076.3  871.03  4084.2  872.08  4090.7  871.98
  4140.8  869.39  4218.9  867.64  4382.2  865.62  4446.0  865.56  4531.3  864.03
  4694.7  863.36  4715.5  863.92  4723.3  861.01  4729.8  861.35  4737.6  863.25
  4744.1  862.62  4751.9  863.35  4765.6  863.03  4779.3  864.18  4793.6  863.37
  4801.4  863.94  4964.1  862.69  5019.9  859.50  5037.9  859.35  5038.2  858.85
  5041.9  859.35  5089.9  865.01  5169.9  865.97  5229.9  869.34  5249.9  871.71
#Mann=3,-1,0
  3828.4    0.05       0  5037.9   0.033       0  5041.9    0.05       0
Bank Sta=5037.9,5041.9
Exp/Cntr=0.3,0.1

Type RM Length L Ch R = 1,8480,366,366,366
BEGIN DESCRIPTION:
S52 15.0
END DESCRIPTION:
XS GIS Cut Line= 3
      2291028.97      7067260.03      2291929.00      7066360.00
      2291629.02      7065810.03
#Sta/Elev= 30
  3727.2  877.41  3925.2  871.21  4052.5  868.75  4080.8  869.26  4137.4  866.80
  4292.9  864.15  4490.9  862.40  4703.1  862.11  4816.2  859.13  4886.9  858.96
  4929.3  859.86  4957.6  859.00  4971.8  859.39  4983.9  858.17  4984.1  857.67
  4987.9  858.17  4996.5  859.88  5117.3  860.91  5264.4  865.09  5296.2  867.68
  5318.5  866.81  5324.2  867.53  5330.4  866.66  5346.0  866.92  5353.2  868.44
  5384.0  868.53  5433.4  872.02  5481.3  872.73  5505.6  873.91  5626.5  878.69
#Mann=5,-1,0
  3727.2    0.05       0  4983.9   0.033       0  4987.9    0.05       0
  5481.3    0.12       0  5505.6    0.05       0
Bank Sta=4983.9,4987.9
Exp/Cntr=0.3,0.1

Type RM Length L Ch R = 1,8114,1326,1326,1326
BEGIN DESCRIPTION:
S52 14.0
END DESCRIPTION:
XS GIS Cut Line= 3
      2291679.02      7067209.97      2292279.00      7066310.00
      2291729.03      7065810.02
#Sta/Elev= 30
  3917.9  870.09  4379.1  859.77  4523.3  858.14  4760.7  858.11  4767.7  855.84
  4767.9  855.34  4771.7  855.84  4775.7  858.00  4783.2  855.97  4790.7  858.15
  4962.3  856.56  5035.0  856.41  5041.8  859.16  5049.2  858.39  5056.0  860.79
  5063.4  860.17  5070.1  861.67  5106.0  861.63  5112.7  859.92  5120.1  861.16
  5126.9  859.09  5148.2  858.21  5155.3  859.19  5162.0  857.70  5169.5  858.70
  5176.2  857.30  5218.8  860.31  5268.9  860.76  5466.8  865.71  5742.8  877.08
#Mann=5,-1,0
  3917.9    0.05       0  4767.7    0.07       0  4771.7    0.05       0
  4962.3    0.12       0  5268.9    0.05       0
Bank Sta=4767.7,4771.7
Exp/Cntr=0.3,0.1

Type RM Length L Ch R = 1,6788,436,436,436
BEGIN DESCRIPTION:
S52 13.0
END DESCRIPTION:
XS GIS Cut Line= 3
      2291979.03      7067159.97      2293179.00      7065960.00
      2293079.00      7064759.98
#Sta/Elev= 30
  3287.8  866.25  3429.2  863.61  3471.6  864.59  3528.2  861.61  3910.0  857.23
  4079.7  857.59  4235.3  855.95  4262.4  857.22  4291.9  855.95  4320.1  857.88
  4348.4  855.00  4501.6  854.77  4772.7  853.23  4834.7  849.72  4914.1  847.31
  4987.3  849.66  5053.0  843.56  5053.3  843.06  5057.2  843.56  5163.9  850.00
  5288.4  850.70  5346.1  848.00  5356.1  846.33  5416.3  849.08  5466.5  847.58
  5496.6  851.60  5867.9  857.31  5908.0  859.03  6010.9  859.52  6189.0  865.93
#Mann=7,-1,0
  3287.8    0.05       0  4262.4    0.12       0  4501.6    0.05       0
  4834.7    0.12       0  5053.0    0.07       0  5057.2    0.12       0
  5163.9    0.05       0
Bank Sta=5053,5057.2
Exp/Cntr=0.3,0.1

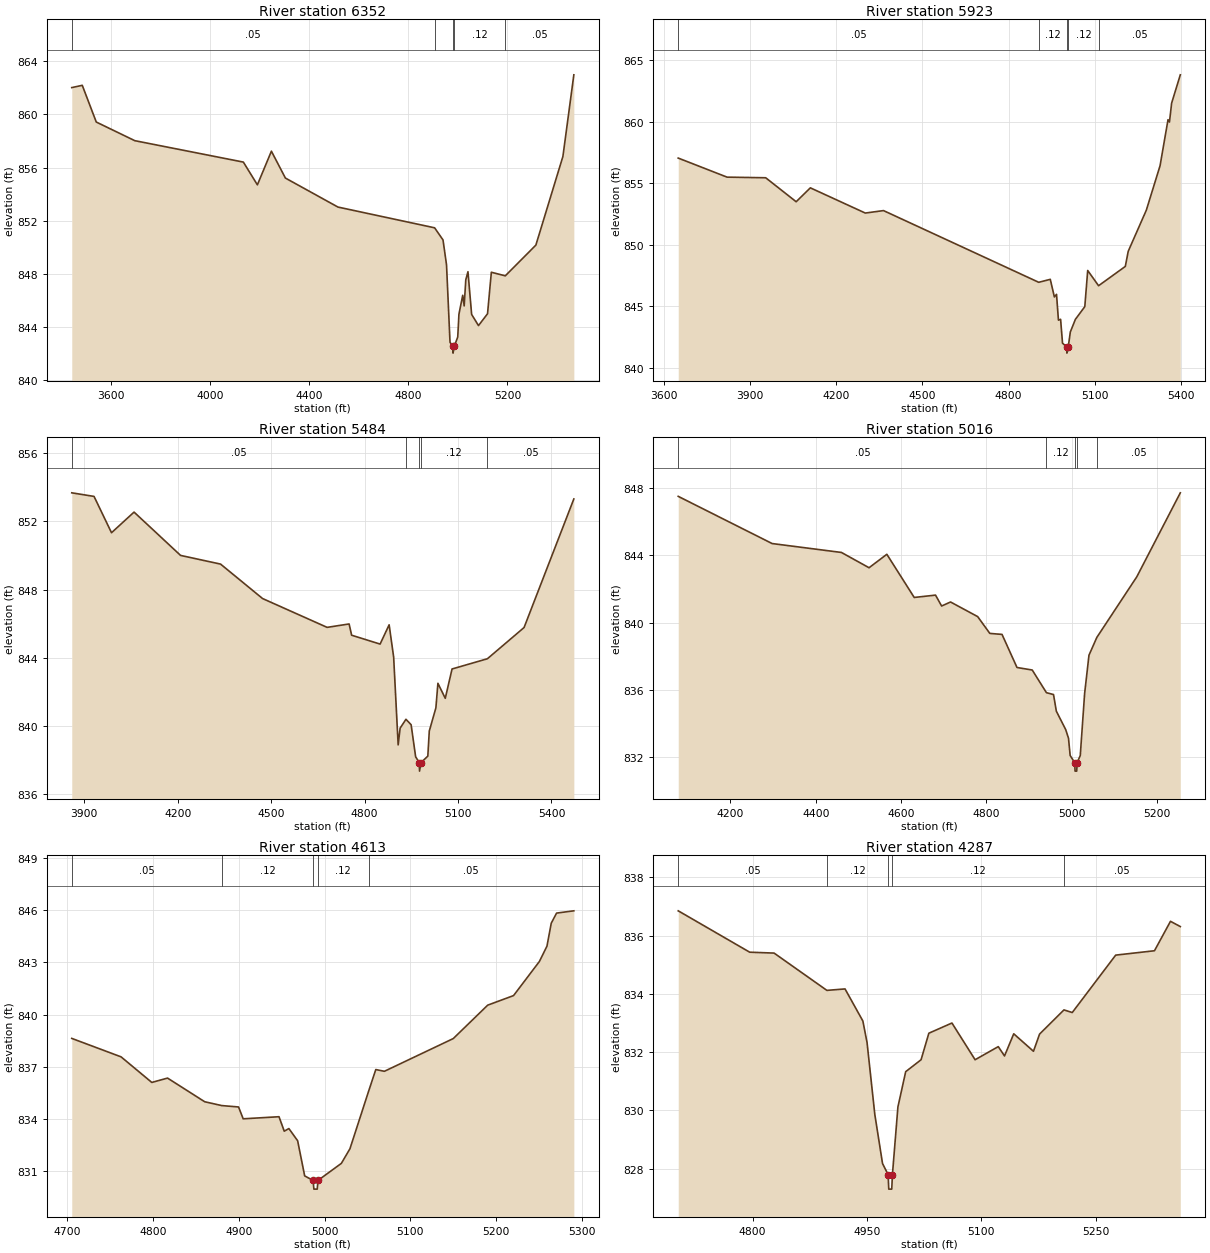
Type RM Length L Ch R = 1,6352,429,429,429
BEGIN DESCRIPTION:
S52 12.0
END DESCRIPTION:
XS GIS Cut Line= 3
      2292329.03      7067059.97      2293429.00      7065960.00
      2293679.00      7065559.99
#Sta/Elev= 30
  3440.7  862.01  3483.1  862.18  3539.7  859.42  3695.2  858.02  4133.6  856.41
  4190.2  854.70  4246.8  857.23  4303.3  855.21  4515.5  853.03  4905.8  851.47
  4939.7  850.56  4953.9  848.69  4968.0  842.87  4979.4  842.55  4980.2  842.05
  4984.9  842.55  4999.2  843.26  5004.0  844.97  5019.3  846.40  5025.2  845.60
  5031.7  847.56  5040.5  848.17  5055.3  844.96  5083.0  844.12  5119.5  845.01
  5134.9  848.13  5191.2  847.86  5314.7  850.17  5423.8  856.83  5468.0  862.97
#Mann=5,-1,0
  3440.7    0.05       0  4905.8    0.12       0  4979.4    0.07       0
  4984.9    0.12       0  5191.2    0.05       0
Bank Sta=4979.4,4984.9
Exp/Cntr=0.3,0.1

Type RM Length L Ch R = 1,5923,439,439,439
BEGIN DESCRIPTION:
S52 11.0
END DESCRIPTION:
XS GIS Cut Line= 3
      2292828.98      7066860.01      2293829.00      7065960.00
      2293779.00      7065560.00
#Sta/Elev= 30
  3649.7  857.04  3819.8  855.49  3954.3  855.44  4060.4  853.49  4109.8  854.62
  4301.1  852.57  4364.6  852.77  4905.1  846.94  4945.4  847.18  4959.6  845.75
  4967.1  845.96  4973.8  843.86  4981.3  843.93  4988.0  841.99  5002.4  841.68
  5003.2  841.18  5007.9  841.68  5015.2  842.90  5032.9  843.93  5065.6  844.96
  5075.7  847.90  5113.5  846.66  5206.7  848.23  5216.8  849.46  5279.8  852.80
  5327.7  856.42  5355.4  860.16  5360.4  859.97  5368.0  861.51  5398.2  863.81
#Mann=5,-1,0
  3649.7    0.05       0  4905.1    0.12       0  5002.4    0.07       0
  5007.9    0.12       0  5113.5    0.05       0
Bank Sta=5002.4,5007.9
Exp/Cntr=0.3,0.1

Type RM Length L Ch R = 1,5484,468,468,468
BEGIN DESCRIPTION:
S52 10.0
END DESCRIPTION:
XS GIS Cut Line= 3
      2293329.02      7066759.99      2294229.00      7066060.00
      2293978.97      7065659.96
#Sta/Elev= 30
  3860.0  853.67  3931.5  853.46  3987.6  851.33  4060.0  852.54  4209.3  850.00
  4337.8  849.49  4472.6  847.47  4679.8  845.78  4750.4  845.98  4758.5  845.32
  4849.9  844.80  4878.9  845.93  4893.4  844.04  4907.9  838.89  4914.2  839.87
  4932.9  840.39  4949.5  840.07  4964.0  838.19  4975.7  837.85  4976.5  837.35
  4981.2  837.85  5003.1  838.23  5007.8  839.70  5029.0  841.06  5035.5  842.50
  5059.1  841.62  5080.9  843.34  5194.4  843.94  5312.1  845.77  5471.9  853.31
#Mann=5,-1,0
  3860.0    0.05       0  4932.9    0.12       0  4975.7    0.07       0
  4981.2    0.12       0  5194.4    0.05       0
Bank Sta=4975.7,4981.2
Exp/Cntr=0.3,0.1

Type RM Length L Ch R = 1,5016,403,403,403
BEGIN DESCRIPTION:
S52 9.0
END DESCRIPTION:
XS GIS Cut Line= 3
      2293978.99      7066710.01      2294679.00      7066110.00
      2294729.00      7065860.02
#Sta/Elev= 30
  4077.7  847.52  4297.8  844.71  4460.2  844.18  4525.0  843.27  4566.7  844.07
  4630.9  841.50  4680.8  841.64  4695.1  840.99  4716.0  841.23  4779.6  840.36
  4808.1  839.36  4836.7  839.30  4871.8  837.33  4907.5  837.18  4940.8  835.83
  4957.4  835.72  4964.0  834.73  4986.0  833.63  4992.5  833.12  4996.4  832.09
  5007.1  831.66  5007.9  831.16  5011.8  831.16  5012.7  831.66  5020.1  832.09
  5030.3  835.78  5040.5  838.06  5058.9  839.12  5152.6  842.73  5254.6  847.73
#Mann=5,-1,0
  4077.7    0.05       0  4940.8    0.12       0  5007.1    0.07       0
  5012.7    0.12       0  5058.9    0.05       0
Bank Sta=5007.1,5012.7
Exp/Cntr=0.3,0.1

Type RM Length L Ch R = 1,4613,326,326,326
BEGIN DESCRIPTION:
S52 7.5
END DESCRIPTION:
XS GIS Cut Line= 3
      2294939.14      7066482.99      2295043.89      7066229.86
      2295022.07      7065919.98
#Sta/Elev= 30
  4705.7  838.63  4763.1  837.57  4798.9  836.10  4817.2  836.35  4860.5  834.99
  4880.4  834.77  4899.9  834.69  4905.3  834.01  4947.0  834.13  4953.1  833.30
  4958.5  833.45  4968.7  832.75  4976.9  830.73  4986.7  830.47  4987.6  829.97
  4991.5  829.97  4992.4  830.47  5019.6  831.45  5029.6  832.29  5051.3  835.59
  5059.7  836.84  5069.7  836.74  5149.9  838.62  5190.0  840.54  5220.1  841.09
  5250.2  843.05  5259.0  843.93  5264.0  845.25  5270.2  845.83  5290.3  845.96
#Mann=5,-1,0
  4705.7    0.05       0  4880.4    0.12       0  4986.7    0.07       0
  4992.4    0.12       0  5051.3    0.05       0
Bank Sta=4986.7,4992.4
Exp/Cntr=0.3,0.1

Type RM Length L Ch R = 1,4287,173,173,173
BEGIN DESCRIPTION:
1679
END DESCRIPTION:
XS GIS Cut Line= 4
      2295097.42      7066504.76      2295307.36      7066436.83
      2295270.68      7066208.13      2295154.96      7066036.96
#Sta/Elev= 30
  4702.3  836.85  4796.1  835.43  4828.1  835.40  4897.4  834.12  4921.2  834.17
  4944.6  833.07  4950.1  832.33  4960.3  829.86  4970.4  828.18  4977.7  827.80
  4978.6  827.30  4982.5  827.30  4983.4  827.80  4990.6  830.12  5000.8  831.33
  5021.0  831.74  5031.2  832.65  5061.5  833.00  5091.9  831.74  5122.3  832.19
  5130.5  831.87  5142.6  832.63  5168.5  832.03  5176.5  832.62  5208.5  833.45
  5219.4  833.36  5276.4  835.33  5327.3  835.48  5348.3  836.49  5361.2  836.31
#Mann=5,-1,0
  4702.3    0.05       0  4897.4    0.12       0  4977.7    0.07       0
  4983.4    0.12       0  5208.5    0.05       0
Bank Sta=4977.7,4983.4
Exp/Cntr=0.3,0.1

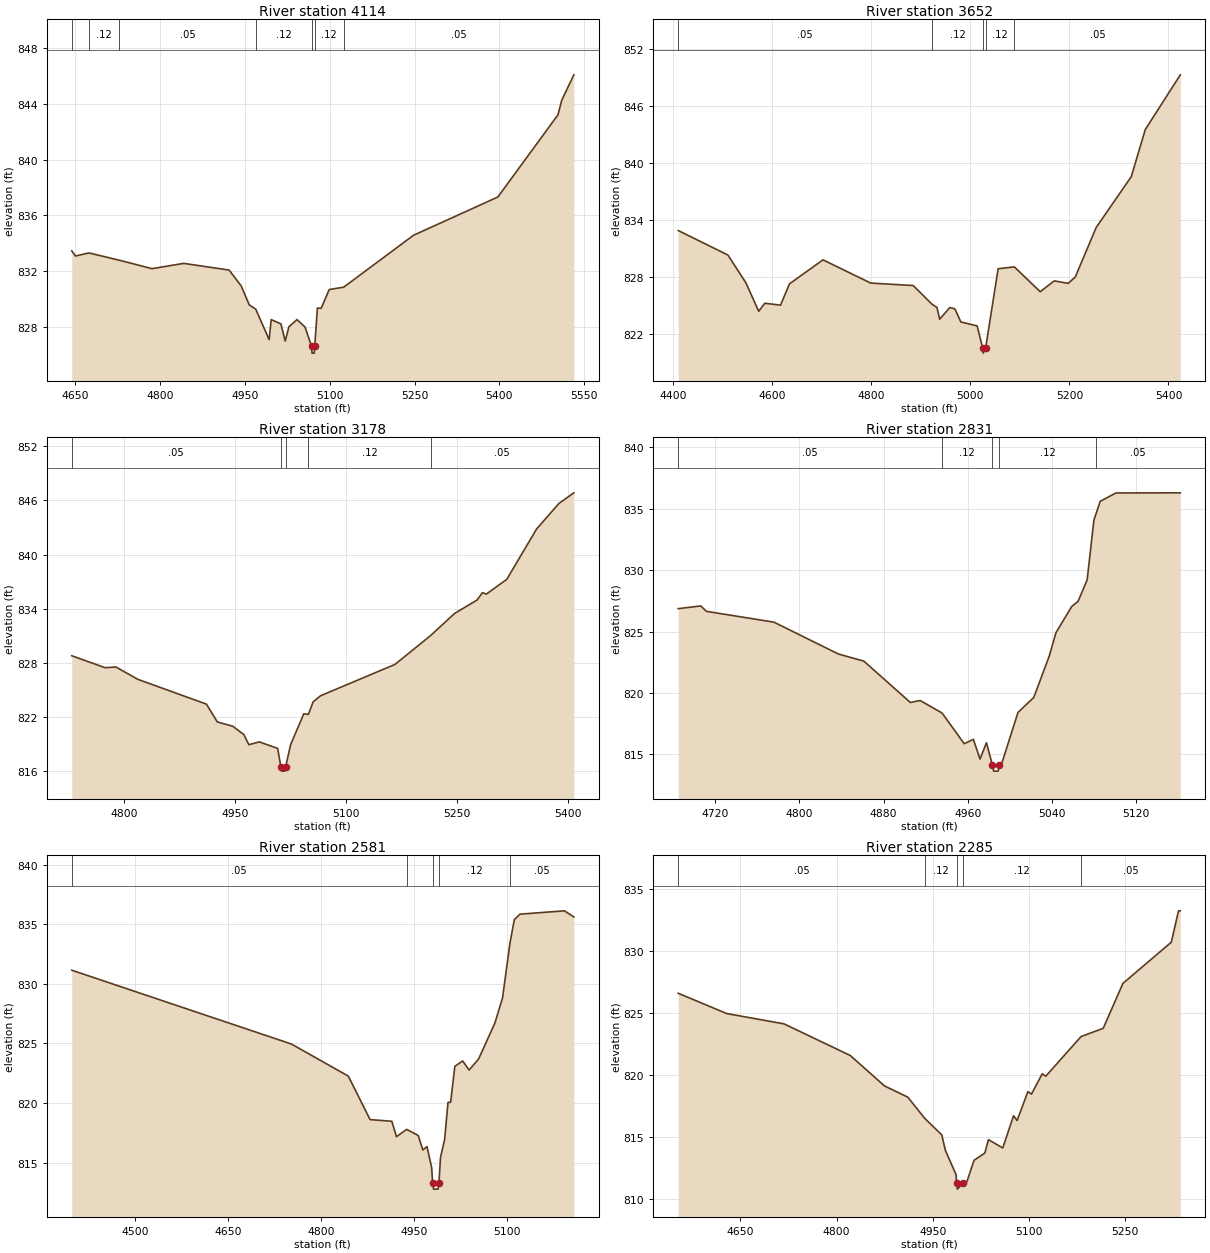
Type RM Length L Ch R = 1,4114,462,462,462
BEGIN DESCRIPTION:
S52 7.0
END DESCRIPTION:
XS GIS Cut Line= 4
      2295339.30      7066499.56      2295515.46      7066350.74
      2295429.00      7066260.00      2295078.97      7065859.96
#Sta/Elev= 30
  4644.1  833.44  4650.7  833.07  4674.4  833.29  4727.9  832.77  4785.9  832.16
  4841.9  832.54  4922.2  832.06  4943.6  830.92  4957.8  829.56  4969.3  829.25
  4993.0  827.06  4996.6  828.50  5013.8  828.19  5021.4  826.96  5028.0  827.99
  5042.3  828.50  5056.5  827.96  5067.9  826.59  5068.8  826.09  5072.7  826.09
  5073.6  826.59  5078.3  829.33  5085.0  829.31  5099.2  830.66  5124.8  830.83
  5248.2  834.56  5397.3  837.31  5503.6  843.22  5510.2  844.26  5531.6  846.09
#Mann=7,-1,0
  4644.1    0.05       0  4674.4    0.12       0  4727.9    0.05       0
  4969.3    0.12       0  5067.9    0.07       0  5073.6    0.12       0
  5124.8    0.05       0
Bank Sta=5067.9,5073.6
Exp/Cntr=0.3,0.1

Type RM Length L Ch R = 1,3652,474,474,474
BEGIN DESCRIPTION:
S52 6.0
END DESCRIPTION:
XS GIS Cut Line= 4
      2295768.49      7066575.02      2295666.67      7066281.99
      2295729.00      7066010.00      2296028.99      7065710.01
#Sta/Elev= 30
  4410.4  832.92  4510.6  830.35  4547.0  827.43  4572.8  824.44  4585.1  825.28
  4616.9  825.08  4635.0  827.32  4702.6  829.84  4798.9  827.40  4884.7  827.14
  4922.7  825.18  4932.7  824.84  4938.1  823.60  4958.6  824.83  4968.9  824.69
  4980.8  823.32  5013.8  822.90  5025.1  820.54  5026.0  820.04  5030.8  820.54
  5056.2  828.91  5088.9  829.10  5141.1  826.49  5169.4  827.63  5197.6  827.37
  5211.8  828.03  5254.2  833.25  5324.9  838.58  5353.2  843.53  5423.9  849.28
#Mann=5,-1,0
  4410.4    0.05       0  4922.7    0.12       0  5025.1    0.07       0
  5030.8    0.12       0  5088.9    0.05       0
Bank Sta=5025.1,5030.8
Exp/Cntr=0.3,0.1

Type RM Length L Ch R = 1,3178,347,347,347
BEGIN DESCRIPTION:
S52 5.0
END DESCRIPTION:
XS GIS Cut Line= 3
      2295971.80      7066436.83      2296129.00      7066210.00
      2296179.00      7065809.99
#Sta/Elev= 30
  4728.7  828.78  4773.6  827.46  4788.5  827.53  4818.2  826.16  4910.8  823.42
  4925.6  821.44  4946.6  820.96  4961.4  820.05  4968.2  818.92  4982.4  819.23
  5007.2  818.51  5011.5  816.49  5012.6  815.99  5017.0  815.99  5018.0  816.49
  5024.8  818.94  5042.5  822.34  5048.8  822.28  5055.1  823.66  5065.1  824.34
  5165.9  827.82  5214.1  831.02  5246.5  833.47  5276.8  834.95  5284.3  835.78
  5289.4  835.61  5317.1  837.25  5357.4  842.83  5387.6  845.66  5407.8  846.84
#Mann=5,-1,0
  4728.7    0.05       0  5011.5   0.033       0  5018.0    0.05       0
  5048.8    0.12       0  5214.1    0.05       0
Bank Sta=5011.5,5018
Exp/Cntr=0.3,0.1

Type RM Length L Ch R = 1,2831,250,250,250
BEGIN DESCRIPTION:
1680
END DESCRIPTION:
XS GIS Cut Line= 3
      2296174.87      7066473.36      2296399.12      7066381.73
      2296529.34      7066186.40
#Sta/Elev= 30
  4684.9  826.87  4706.3  827.09  4711.7  826.65  4775.8  825.77  4837.2  823.17
  4861.2  822.60  4905.4  819.23  4914.7  819.39  4935.6  818.37  4956.6  815.87
  4965.3  816.23  4971.6  814.62  4977.7  815.95  4983.4  814.14  4984.5  813.64
  4988.9  813.64  4989.9  814.14  4992.7  814.38  5007.7  818.42  5022.7  819.64
  5037.4  823.01  5043.8  824.92  5058.8  827.05  5064.8  827.47  5073.4  829.21
  5079.8  834.07  5081.9  834.61  5085.8  835.61  5100.8  836.29  5161.9  836.30
#Mann=5,-1,0
  4684.9    0.05       0  4935.6    0.12       0  4983.4    0.07       0
  4989.9    0.12       0  5081.9    0.05       0
Bank Sta=4983.4,4989.9
Exp/Cntr=0.3,0.1

Type RM Length L Ch R = 1,2581,296,296,296
BEGIN DESCRIPTION:
S52 4.0
END DESCRIPTION:
XS GIS Cut Line= 3
      2296234.43      7066915.53      2296641.20      7066458.70
      2296697.52      7066267.82
#Sta/Elev= 30
  4397.9  831.14  4752.5  824.95  4844.4  822.26  4879.6  818.61  4914.7  818.47
  4922.2  817.18  4938.7  817.79  4957.3  817.28  4964.8  816.06  4971.5  816.35
  4979.0  814.58  4980.6  813.28  4982.0  812.78  4989.4  812.78  4990.8  813.28
  4993.3  815.43  5000.0  816.96  5005.4  820.06  5009.6  820.06  5016.5  823.08
  5029.1  823.53  5039.5  822.77  5054.8  823.69  5081.2  826.72  5093.5  828.83
  5105.6  833.46  5112.5  835.38  5121.6  835.84  5193.4  836.12  5208.6  835.61
#Mann=5,-1,0
  4397.9    0.05       0  4938.7    0.12       0  4980.6    0.07       0
  4990.8    0.12       0  5105.6    0.05       0
Bank Sta=4980.6,4990.8
Exp/Cntr=0.3,0.1

Type RM Length L Ch R = 1,2285,920,920,920
BEGIN DESCRIPTION:
S52 3.0
END DESCRIPTION:
XS GIS Cut Line= 3
      2296678.99      7067010.03      2296879.00      7066610.00
      2296728.98      7066309.96
#Sta/Elev= 30
  4553.2  826.58  4628.7  824.95  4718.1  824.12  4821.6  821.57  4874.7  819.13
  4911.0  818.23  4937.5  816.52  4964.1  815.19  4969.7  813.94  4986.5  811.97
  4987.0  811.33  4988.4  810.83  4997.2  811.33  5003.2  811.43  5014.4  813.15
  5031.2  813.73  5036.8  814.81  5059.1  814.14  5075.9  816.73  5081.5  816.35
  5098.3  818.67  5103.9  818.47  5120.6  820.10  5126.2  819.91  5181.2  823.10
  5215.7  823.76  5246.4  827.37  5321.9  830.69  5333.1  833.21  5335.9  833.21
#Mann=5,-1,0
  4553.2    0.05       0  4937.5    0.12       0  4987.0    0.07       0
  4997.2    0.12       0  5181.2    0.05       0
Bank Sta=4987,4997.2
Exp/Cntr=0.3,0.1

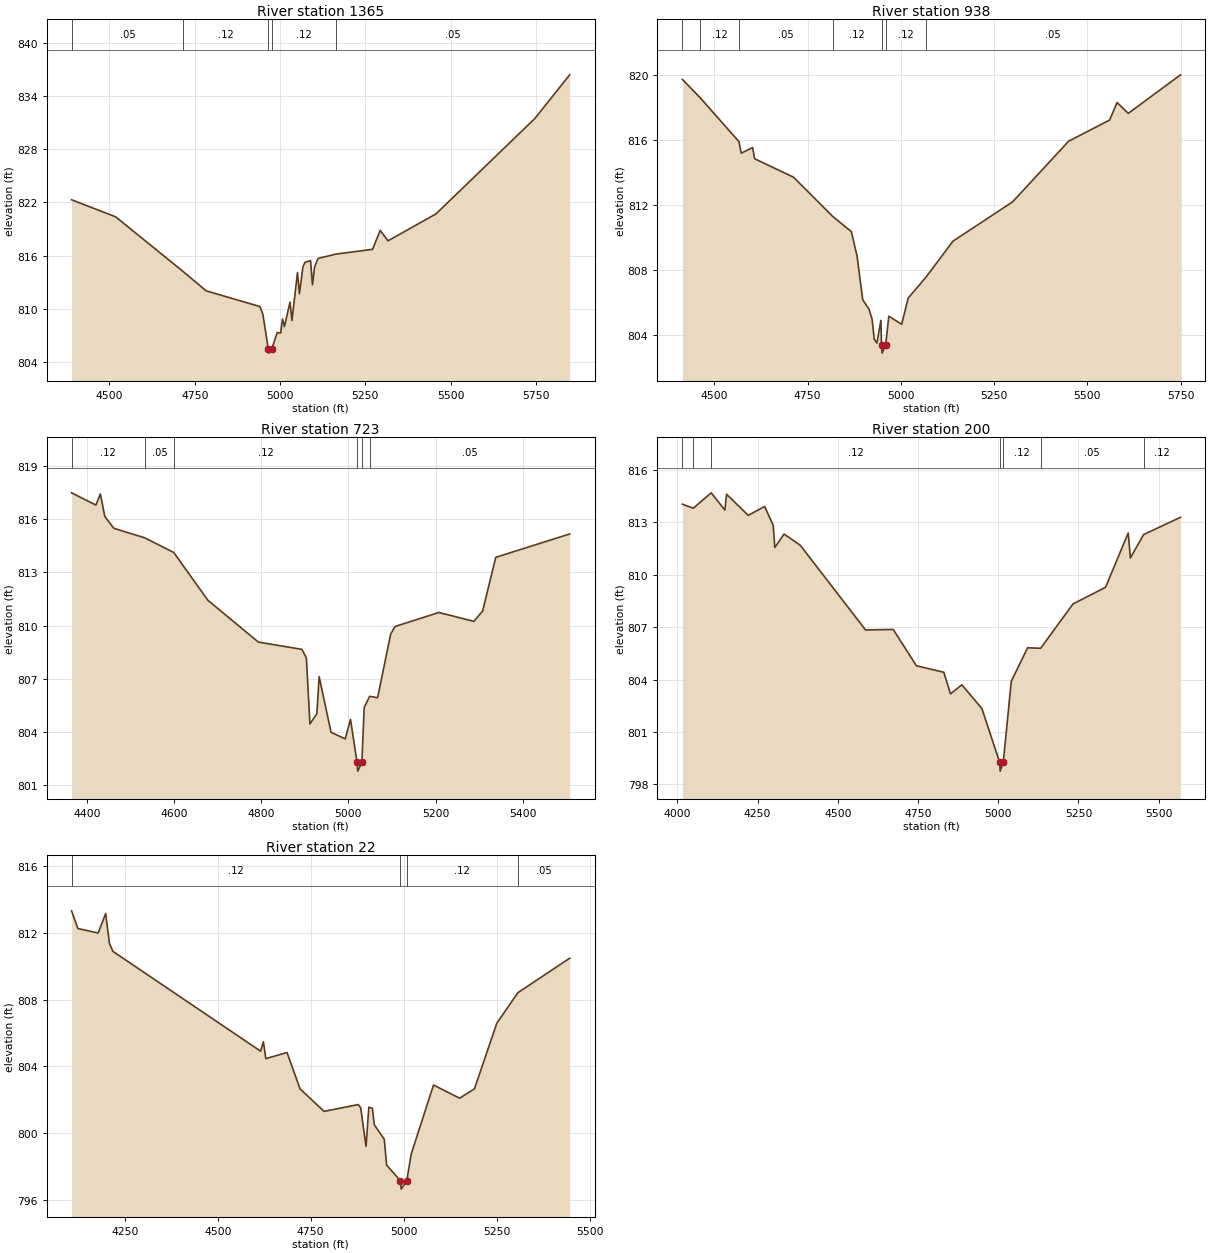
Type RM Length L Ch R = 1,1365,427,427,427
BEGIN DESCRIPTION:
S52 2.0
END DESCRIPTION:
XS GIS Cut Line= 3
      2297079.04      7066909.97      2297579.00      7066560.00
      2297178.99      7065809.98
#Sta/Elev= 30
  4388.9  822.30  4518.3  820.37  4716.0  814.19  4783.4  812.01  4941.2  810.23
  4949.9  809.33  4965.5  805.47  4967.0  804.97  4976.1  805.47  4991.8  807.29
  5002.0  807.26  5007.3  808.83  5013.0  807.98  5029.3  810.73  5035.0  808.66
  5051.2  814.07  5056.9  811.68  5067.2  814.75  5073.2  815.23  5089.5  815.43
  5095.2  812.69  5101.2  814.68  5111.5  815.67  5163.6  816.16  5271.2  816.70
  5293.8  818.84  5316.5  817.66  5457.1  820.70  5747.2  831.49  5849.2  836.42
#Mann=5,-1,0
  4388.9    0.05       0  4716.0    0.12       0  4965.5    0.07       0
  4976.1    0.12       0  5163.6    0.05       0
Bank Sta=4965.5,4976.1
Exp/Cntr=0.3,0.1

Type RM Length L Ch R = 1,938,215,215,215
BEGIN DESCRIPTION:
S52 1.0
END DESCRIPTION:
XS GIS Cut Line= 3
      2297328.96      7067010.01      2297879.00      7066810.00
      2297879.00      7066059.98
#Sta/Elev= 30
  4414.4  819.76  4461.4  818.64  4566.0  815.92  4572.1  815.20  4602.6  815.55
  4608.0  814.86  4712.4  813.72  4817.8  811.29  4867.3  810.36  4882.6  808.86
  4897.9  806.15  4914.6  805.58  4923.2  804.93  4928.5  803.74  4935.8  803.48
  4946.5  804.88  4948.2  803.36  4949.8  802.86  4959.3  803.36  4967.8  805.14
  5002.2  804.64  5019.7  806.26  5066.1  807.51  5139.7  809.77  5299.7  812.20
  5449.7  815.94  5559.7  817.25  5579.7  818.33  5609.7  817.66  5749.7  820.04
#Mann=7,-1,0
  4414.4    0.05       0  4461.4    0.12       0  4566.0    0.05       0
  4817.8    0.12       0  4948.2    0.07       0  4959.3    0.12       0
  5066.1    0.05       0
Bank Sta=4948.2,4959.3
Exp/Cntr=0.3,0.1

Type RM Length L Ch R = 1,723,523,523,523
BEGIN DESCRIPTION:
S52 1.1
END DESCRIPTION:
XS GIS Cut Line= 4
      2297504.76      7067034.44      2298039.84      7066906.14
      2298080.51      7066774.73      2298124.32      7066321.05
#Sta/Elev= 30
  4364.4  817.49  4420.2  816.80  4430.5  817.43  4440.7  816.16  4461.3  815.49
  4532.6  814.95  4599.2  814.12  4677.3  811.43  4793.2  809.07  4893.2  808.66
  4903.5  808.17  4911.6  804.45  4927.5  805.03  4932.8  807.12  4960.1  803.98
  4992.7  803.61  5004.8  804.71  5019.8  802.29  5021.4  801.79  5030.9  802.29
  5036.2  805.38  5048.8  806.01  5067.0  805.93  5097.1  809.53  5107.2  809.95
  5207.7  810.74  5288.0  810.24  5308.1  810.82  5338.3  813.85  5508.0  815.17
#Mann=6,-1,0
  4364.4    0.12       0  4532.6    0.05       0  4599.2    0.12       0
  5019.8    0.07       0  5030.9    0.12       0  5048.8    0.05       0
Bank Sta=5019.8,5030.9
Exp/Cntr=0.3,0.1

Type RM Length L Ch R = 1,200,178,178,178
BEGIN DESCRIPTION:
S52 0.5
END DESCRIPTION:
XS GIS Cut Line= 5
      2297705.07      7067046.95      2298215.06      7067115.78
      2298540.47      7066871.72      2298515.44      7066734.05
      2298440.34      7066249.03
#Sta/Elev= 30
  4015.8  814.04  4049.8  813.81  4105.6  814.69  4148.3  813.70  4153.4  814.61
  4221.0  813.40  4272.0  813.91  4298.8  812.83  4303.8  811.56  4332.6  812.33
  4383.0  811.69  4586.6  806.84  4672.8  806.87  4745.0  804.79  4830.4  804.42
  4851.2  803.18  4886.6  803.70  4949.1  802.34  5004.5  799.26  5006.1  798.76
  5015.6  799.26  5040.6  803.90  5091.4  805.82  5132.0  805.79  5233.0  808.33
  5334.2  809.28  5405.0  812.39  5411.7  810.96  5452.9  812.30  5567.9  813.29
#Mann=7,-1,0
  4015.8    0.12       0  4049.8    0.05       0  4105.6    0.12       0
  5004.5    0.07       0  5015.6    0.12       0  5132.0    0.05       0
  5452.9    0.12       0
Bank Sta=5004.5,5015.6
Exp/Cntr=0.3,0.1

Type RM Length L Ch R = 1,22,0,0,0
BEGIN DESCRIPTION:
S52 0.1
END DESCRIPTION:
XS GIS Cut Line= 5
      2297977.82      7067113.20      2298387.46      7067155.22
      2298681.54      7066894.75      2298708.84      7066802.32
      2298689.97      7066364.13
#Sta/Elev= 30
  4107.0  813.32  4123.9  812.26  4178.5  811.99  4198.7  813.16  4208.7  811.38
  4218.2  810.89  4615.3  804.91  4622.9  805.47  4629.5  804.46  4686.4  804.83
  4721.5  802.65  4786.0  801.30  4878.0  801.71  4884.6  801.51  4898.9  799.20
  4906.4  801.55  4916.0  801.49  4921.1  800.50  4947.9  799.63  4954.3  798.08
  4991.5  797.14  4993.5  796.64  5008.5  797.14  5020.3  798.74  5080.4  802.88
  5150.5  802.09  5190.5  802.65  5250.5  806.58  5307.2  808.41  5446.6  810.48
#Mann=4,-1,0
  4107.0    0.12       0  4991.5    0.07       0  5008.5    0.12       0
  5307.2    0.05       0
Bank Sta=4991.5,5008.5
Exp/Cntr=0.3,0.1

Chan Stop Cuts=-1