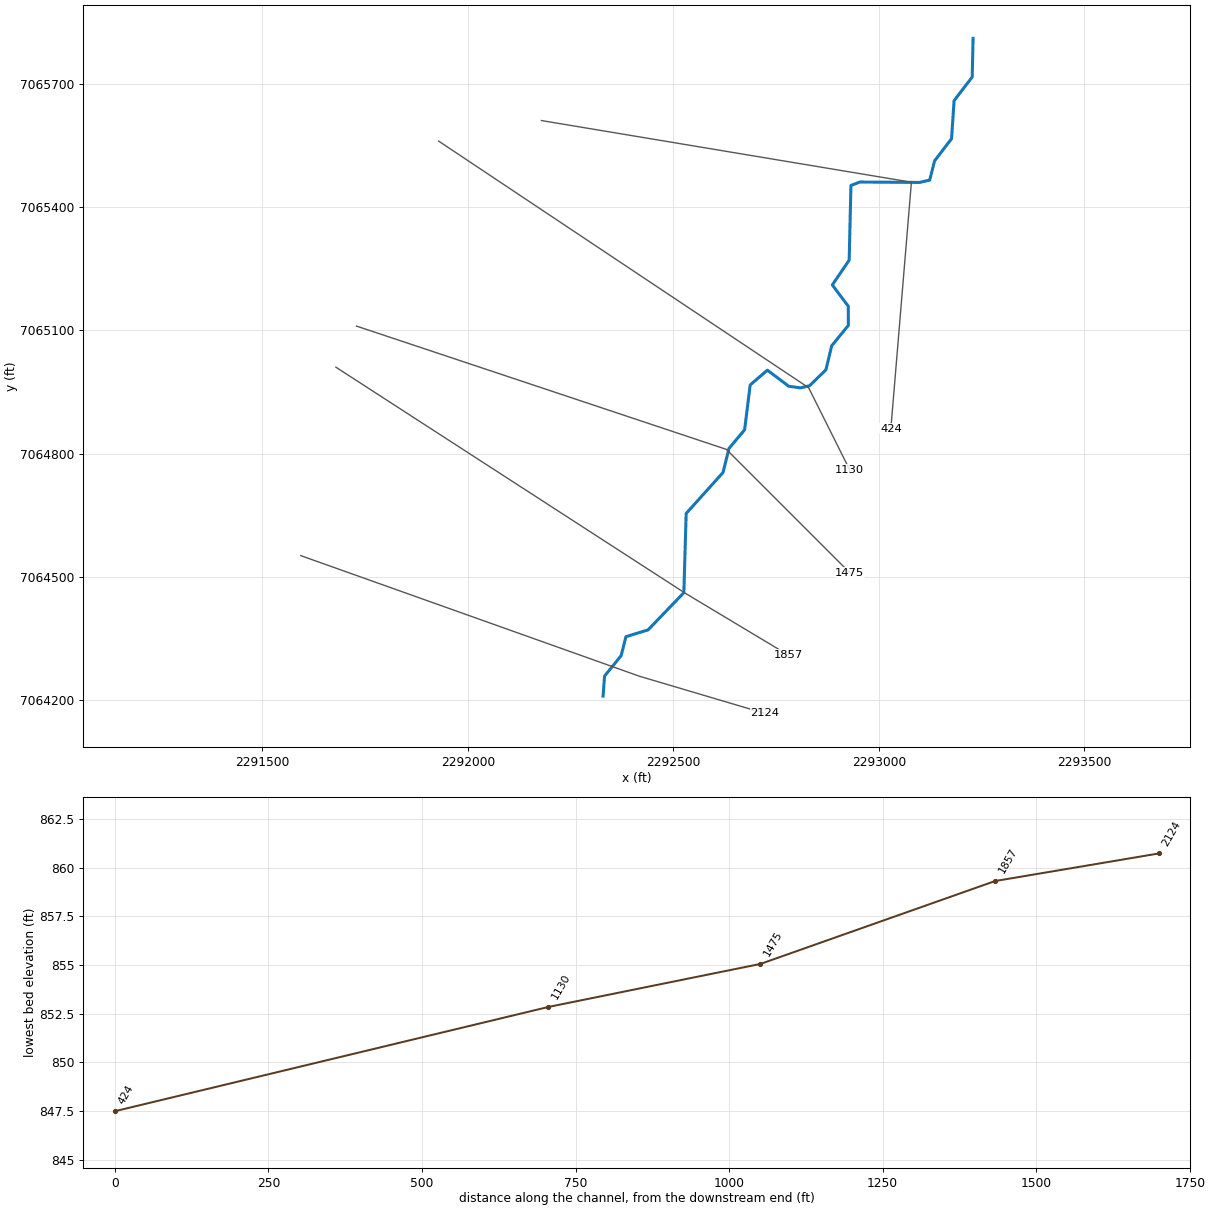
--- S53.prj (project) ---

Proj Title=S53 Base Level Engineering
Current Plan=p01
Default Exp/Contr=0.3,0.1
English Units
Geom File=g01
Flow File=f01
Plan File=p01
BEGIN DESCRIPTION:
S53
END DESCRIPTION:

--- S53.p01 (plan) ---

Plan Title=Multiple Run
Short Identifier=Multiple
Geom File=g01
Flow File=f01
Subcritical Flow
K Sum by GR= 0
Std Step Tol= 0.01
Critical Tol= 0.01
Num of Std Step Trials= 20
Max Error Tol= 0.3
Flow Tol Ratio= 0.001
Split Flow NTrial= 30
Split Flow Tol= 0.02
Split Flow Ratio= 0.02
Log Output Level= 0
Friction Slope Method= 1
Unsteady Friction Slope Method= 2
Unsteady Bridges Friction Slope Method= 1
Parabolic Critical Depth
Global Vel Dist=  1 , 1 , 1
Global Log Level= 0
CheckData=True
Encroach Param= -1, 0, 0, 0
BEGIN DESCRIPTION:
Multiple Run
END DESCRIPTION:

--- S53.f01 (steady flow) ---

Flow Title=Multiple
Number of Profiles=7
Profile Names=10-year,25-year,50-year,1pct_min,100-year,1pct_plu,500-year
River Rch & RM= S53,Reach-1,2124
     418     560     674     404     805    1610    1150
Boundary for River Rch & Prof#=S53,Reach-1,1
Up Type=0
Dn Type=3
Dn Slope=0.005
Boundary for River Rch & Prof#=S53,Reach-1,2
Up Type=0
Dn Type=3
Dn Slope=0.005
Boundary for River Rch & Prof#=S53,Reach-1,3
Up Type=0
Dn Type=3
Dn Slope=0.005
Boundary for River Rch & Prof#=S53,Reach-1,4
Up Type=0
Dn Type=3
Dn Slope=0.005
Boundary for River Rch & Prof#=S53,Reach-1,5
Up Type=0
Dn Type=3
Dn Slope=0.005
Boundary for River Rch & Prof#=S53,Reach-1,6
Up Type=0
Dn Type=3
Dn Slope=0.005
Boundary for River Rch & Prof#=S53,Reach-1,7
Up Type=0
Dn Type=3
Dn Slope=0.005

--- S53.g01 (geometry) ---

Geom Title=Existing Conditions

River Reach=S53,Reach-1
Reach XY= 30
      2292329.00      7064210.00      2292332.58      7064258.55
      2292372.87      7064308.13      2292384.57      7064354.41
      2292438.44      7064370.88      2292525.47      7064461.45
      2292531.07      7064654.14      2292620.84      7064753.95
      2292635.14      7064812.17      2292673.23      7064857.68
      2292686.85      7064966.81      2292728.67      7065002.75
      2292780.66      7064963.58      2292808.94      7064959.64
      2292831.54      7064965.01      2292870.98      7065003.57
      2292885.19      7065062.16      2292925.63      7065111.73
      2292925.40      7065158.36      2292886.59      7065209.99
      2292927.62      7065270.44      2292931.91      7065452.09
      2292953.58      7065460.42      2293099.44      7065459.46
      2293123.59      7065465.17      2293135.30      7065511.78
      2293176.68      7065565.94      2293182.83      7065658.41
      2293226.90      7065715.87      2293229.00      7065810.00

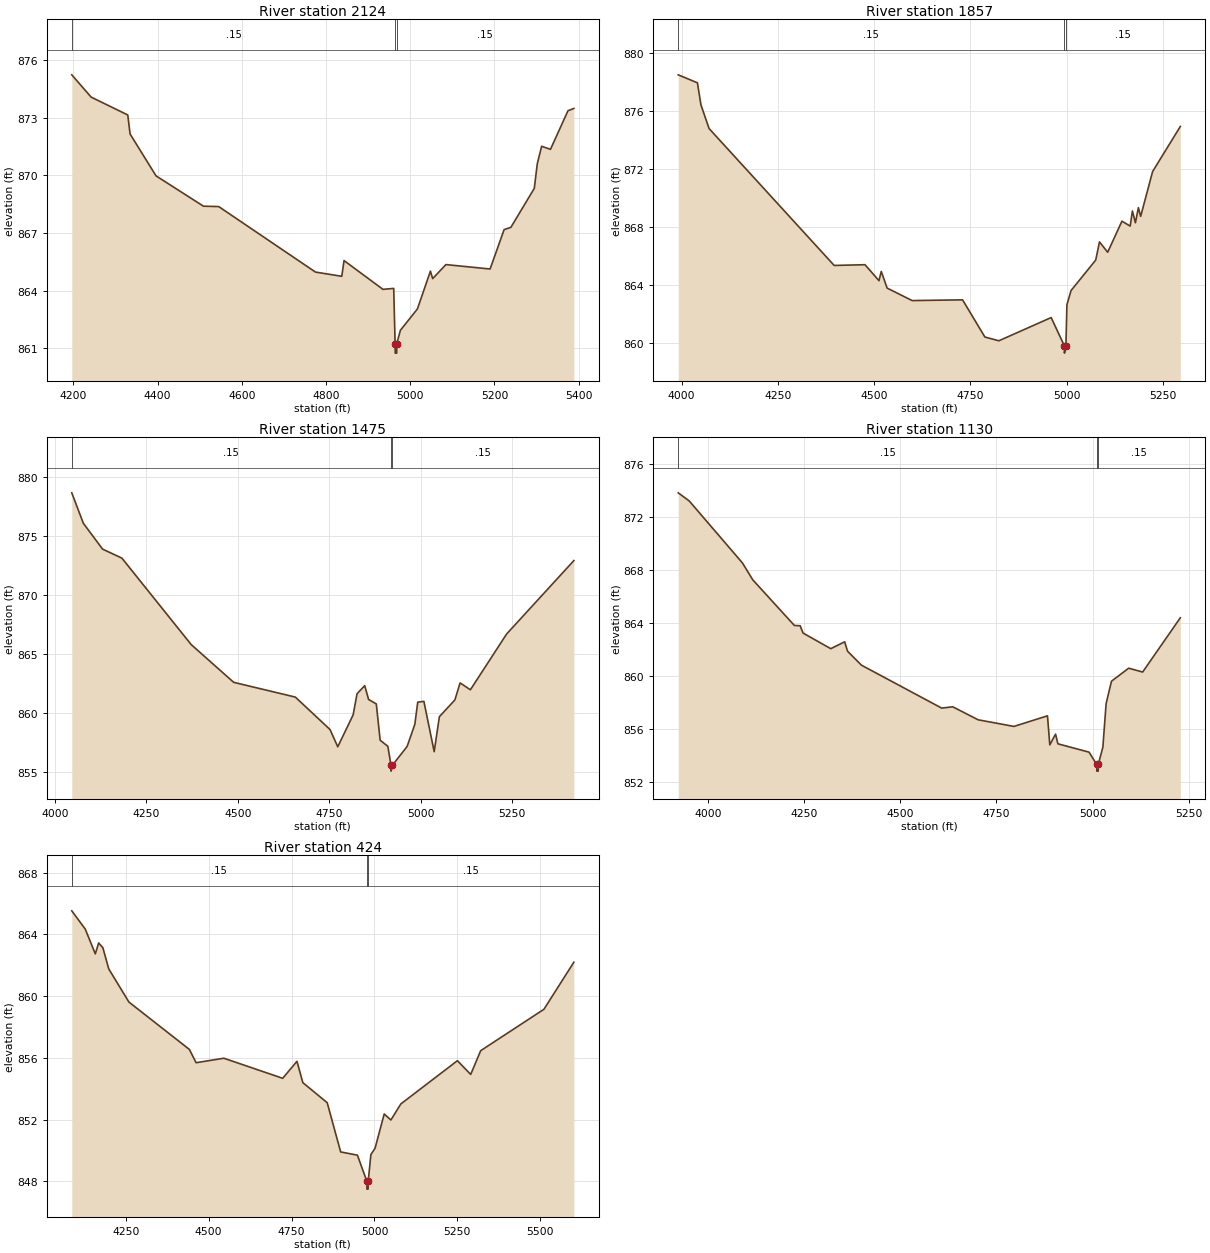
Type RM Length L Ch R = 1,2124,267,267,267
BEGIN DESCRIPTION:
1082
END DESCRIPTION:
XS GIS Cut Line= 3
      2291593.71      7064551.53      2292417.61      7064258.09
      2292722.32      7064167.80
#Sta/Elev= 30
  4196.1  875.23  4242.1  874.07  4329.1  873.14  4334.6  872.15  4396.2  869.97
  4508.9  868.39  4545.1  868.37  4774.9  864.96  4837.4  864.74  4842.7  865.56
  4935.2  864.06  4960.7  864.11  4964.0  861.24  4964.3  860.74  4967.8  860.74
  4968.0  861.24  4976.6  861.93  5017.0  863.04  5047.9  865.01  5053.2  864.62
  5084.7  865.35  5189.6  865.12  5222.9  867.17  5239.0  867.29  5294.6  869.32
  5301.6  870.59  5312.0  871.51  5333.0  871.35  5374.6  873.36  5388.5  873.48
#Mann=3,-1,0
  4196.1    0.15       0  4964.0    0.05       0  4968.0    0.15       0
Bank Sta=4964,4968
Exp/Cntr=0.3,0.1

Type RM Length L Ch R = 1,1857,382,382,382
BEGIN DESCRIPTION:
S53 4.0
END DESCRIPTION:
XS GIS Cut Line= 3
      2291678.99      7065010.01      2292529.00      7064460.00
      2292779.02      7064309.99
#Sta/Elev= 30
  3991.5  878.49  4041.3  877.94  4050.5  876.42  4071.6  874.79  4396.5  865.36
  4476.6  865.41  4512.9  864.31  4518.8  864.95  4534.0  863.80  4599.0  862.94
  4730.0  862.99  4787.9  860.43  4824.2  860.17  4960.1  861.77  4994.4  859.82
  4994.6  859.32  4998.4  859.82  5001.0  862.65  5011.7  863.63  5075.8  865.73
  5085.6  866.98  5106.9  866.27  5143.9  868.41  5165.3  868.07  5171.1  869.11
  5178.9  868.30  5186.6  869.34  5192.5  868.74  5223.6  871.83  5295.5  874.93
#Mann=3,-1,0
  3991.5    0.15       0  4994.4    0.05       0  4998.4    0.15       0
Bank Sta=4994.4,4998.4
Exp/Cntr=0.3,0.1

Type RM Length L Ch R = 1,1475,345,345,345
BEGIN DESCRIPTION:
S53 3.0
END DESCRIPTION:
XS GIS Cut Line= 3
      2291728.97      7065110.01      2292629.00      7064810.00
      2292929.01      7064509.99
#Sta/Elev= 30
  4046.2  878.63  4077.9  876.05  4130.6  873.86  4183.3  873.10  4373.0  865.77
  4489.0  862.58  4657.6  861.33  4752.5  858.58  4773.6  857.12  4815.7  859.83
  4826.3  861.61  4847.3  862.30  4857.9  861.13  4879.0  860.75  4889.5  857.68
  4910.6  857.16  4919.1  855.56  4919.4  855.06  4923.1  855.56  4963.3  857.15
  4984.4  859.03  4992.3  860.90  5009.1  860.97  5037.3  856.71  5051.5  859.67
  5093.9  861.09  5108.1  862.53  5136.3  861.95  5235.3  866.67  5419.2  872.89
#Mann=3,-1,0
  4046.2    0.15       0  4919.1    0.05       0  4923.1    0.15       0
Bank Sta=4919.1,4923.1
Exp/Cntr=0.3,0.1

Type RM Length L Ch R = 1,1130,706,706,706
BEGIN DESCRIPTION:
S53 2.0
END DESCRIPTION:
XS GIS Cut Line= 3
      2291929.01      7065560.00      2292829.00      7064960.00
      2292929.02      7064759.97
#Sta/Elev= 30
  3922.6  873.83  3951.1  873.22  4089.4  868.55  4116.4  867.27  4224.6  863.83
  4239.6  863.81  4247.1  863.26  4319.2  862.08  4355.3  862.60  4362.8  861.89
  4398.8  860.84  4607.6  857.60  4636.2  857.70  4702.3  856.72  4795.4  856.22
  4882.6  857.02  4888.6  854.83  4903.6  855.64  4909.6  854.91  4990.7  854.28
  5010.6  853.35  5010.9  852.85  5014.4  852.85  5014.6  853.35  5026.6  854.66
  5035.0  857.94  5049.0  859.63  5093.7  860.61  5130.0  860.32  5227.9  864.41
#Mann=3,-1,0
  3922.6    0.15       0  5010.6    0.05       0  5014.6    0.15       0
Bank Sta=5010.6,5014.6
Exp/Cntr=0.3,0.1

Type RM Length L Ch R = 1,424,0,0,0
BEGIN DESCRIPTION:
S53 1.0
END DESCRIPTION:
XS GIS Cut Line= 3
      2292178.98      7065610.00      2293079.00      7065460.00
      2293029.00      7064860.01
#Sta/Elev= 30
  4087.0  865.52  4127.6  864.34  4158.0  862.73  4168.1  863.44  4180.8  863.13
  4198.5  861.76  4259.4  859.61  4441.8  856.54  4462.1  855.68  4545.8  855.97
  4723.2  854.67  4766.3  855.77  4784.0  854.39  4857.5  853.09  4898.1  849.90
  4948.7  849.69  4977.2  847.99  4977.4  847.49  4980.9  847.49  4981.2  847.99
  4989.3  849.73  5001.9  850.14  5029.5  852.36  5049.6  851.97  5079.7  853.01
  5250.3  855.81  5290.4  854.92  5320.5  856.46  5511.2  859.14  5601.5  862.19
#Mann=3,-1,0
  4087.0    0.15       0  4977.2    0.05       0  4981.2    0.15       0
Bank Sta=4977.2,4981.2
Exp/Cntr=0.3,0.1

Chan Stop Cuts=-1