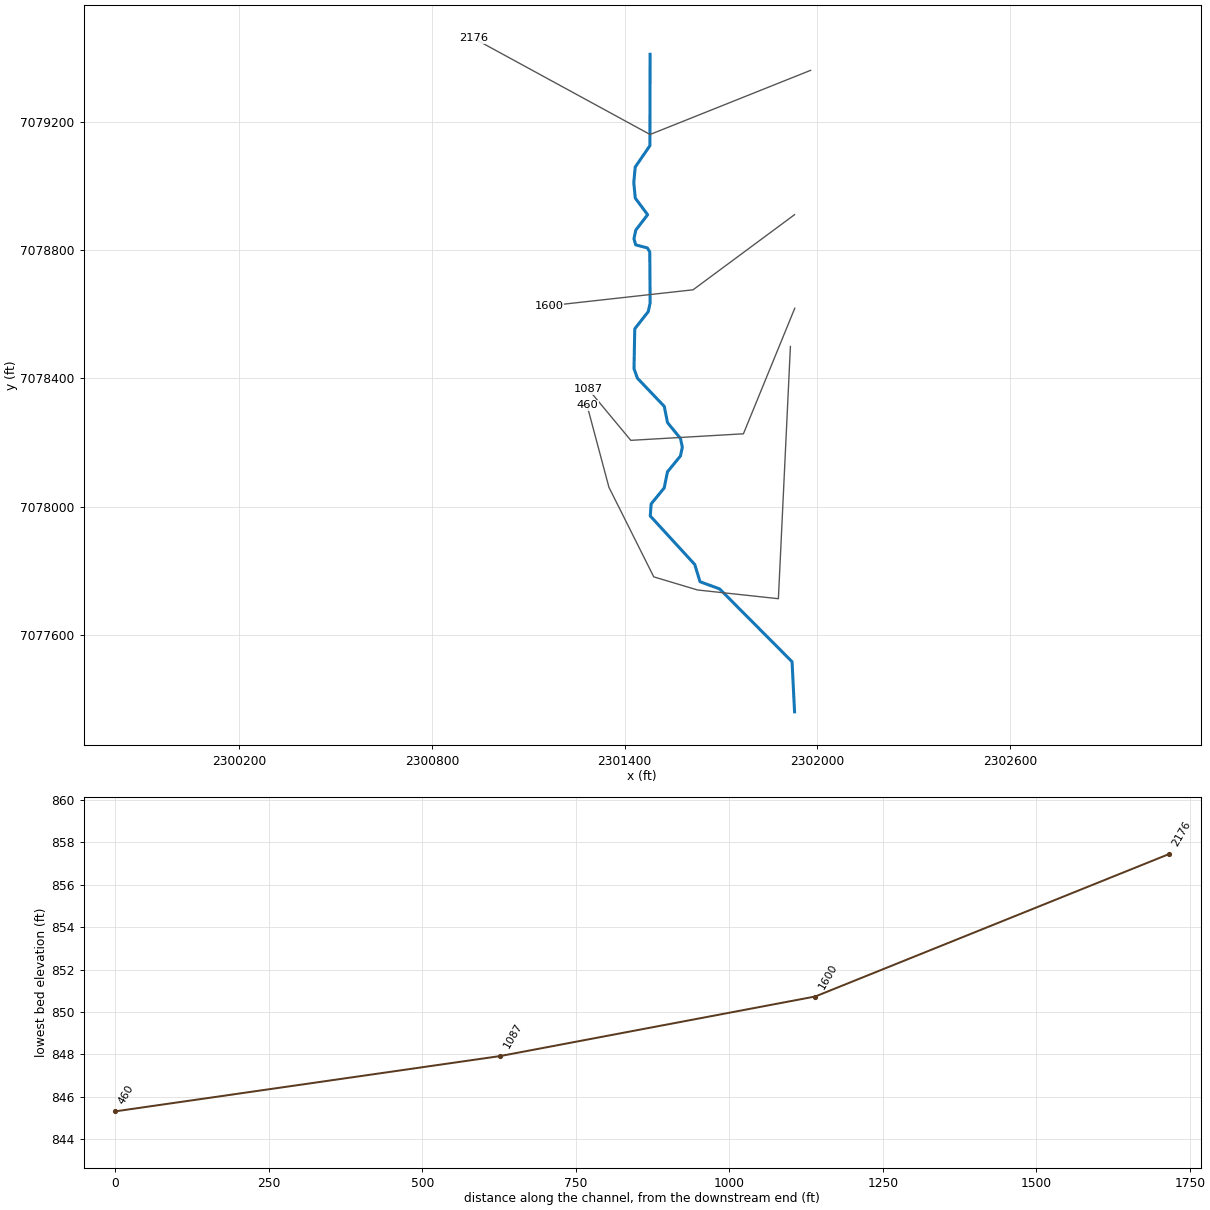
--- S59.prj (project) ---

Proj Title=S59 Base Level Engineering
Current Plan=p01
Default Exp/Contr=0.3,0.1
English Units
Geom File=g01
Flow File=f01
Plan File=p01
BEGIN DESCRIPTION:
S59
END DESCRIPTION:

--- S59.p01 (plan) ---

Plan Title=Multiple Run
Short Identifier=Multiple
Geom File=g01
Flow File=f01
Subcritical Flow
K Sum by GR= 0
Std Step Tol= 0.01
Critical Tol= 0.01
Num of Std Step Trials= 20
Max Error Tol= 0.3
Flow Tol Ratio= 0.001
Split Flow NTrial= 30
Split Flow Tol= 0.02
Split Flow Ratio= 0.02
Log Output Level= 0
Friction Slope Method= 1
Unsteady Friction Slope Method= 2
Unsteady Bridges Friction Slope Method= 1
Parabolic Critical Depth
Global Vel Dist=  1 , 1 , 1
Global Log Level= 0
CheckData=True
Encroach Param= -1, 0, 0, 0
BEGIN DESCRIPTION:
Multiple Run
END DESCRIPTION:

--- S59.f01 (steady flow) ---

Flow Title=Multiple
Number of Profiles=7
Profile Names=10-year,25-year,50-year,1pct_min,100-year,1pct_plu,500-year
River Rch & RM= S59,Reach-1,2176
     402     535     641     382     762    1520    1080
Boundary for River Rch & Prof#=S59,Reach-1,1
Up Type=0
Dn Type=3
Dn Slope=0.005
Boundary for River Rch & Prof#=S59,Reach-1,2
Up Type=0
Dn Type=3
Dn Slope=0.005
Boundary for River Rch & Prof#=S59,Reach-1,3
Up Type=0
Dn Type=3
Dn Slope=0.005
Boundary for River Rch & Prof#=S59,Reach-1,4
Up Type=0
Dn Type=3
Dn Slope=0.005
Boundary for River Rch & Prof#=S59,Reach-1,5
Up Type=0
Dn Type=3
Dn Slope=0.005
Boundary for River Rch & Prof#=S59,Reach-1,6
Up Type=0
Dn Type=3
Dn Slope=0.005
Boundary for River Rch & Prof#=S59,Reach-1,7
Up Type=0
Dn Type=3
Dn Slope=0.005

--- S59.g01 (geometry) ---

Geom Title=Existing Conditions

River Reach=S59,Reach-1
Reach XY= 30
      2301479.00      7079410.00      2301478.48      7079125.22
      2301432.71      7079058.40      2301428.21      7079009.99
      2301432.94      7078961.50      2301471.39      7078909.96
      2301434.55      7078861.98      2301428.77      7078835.00
      2301434.24      7078815.80      2301470.33      7078806.46
      2301478.01      7078794.06      2301479.20      7078634.92
      2301473.25      7078607.67      2301431.25      7078554.06
      2301428.94      7078429.99      2301439.49      7078400.21
      2301523.16      7078312.29      2301533.25      7078261.74
      2301573.67      7078212.20      2301579.42      7078185.00
      2301573.66      7078157.80      2301533.22      7078108.28
      2301522.85      7078057.80      2301482.31      7078008.26
      2301479.59      7077970.62      2301618.11      7077819.42
      2301634.62      7077765.62      2301695.48      7077743.27
      2301921.21      7077516.20      2301929.00      7077360.00

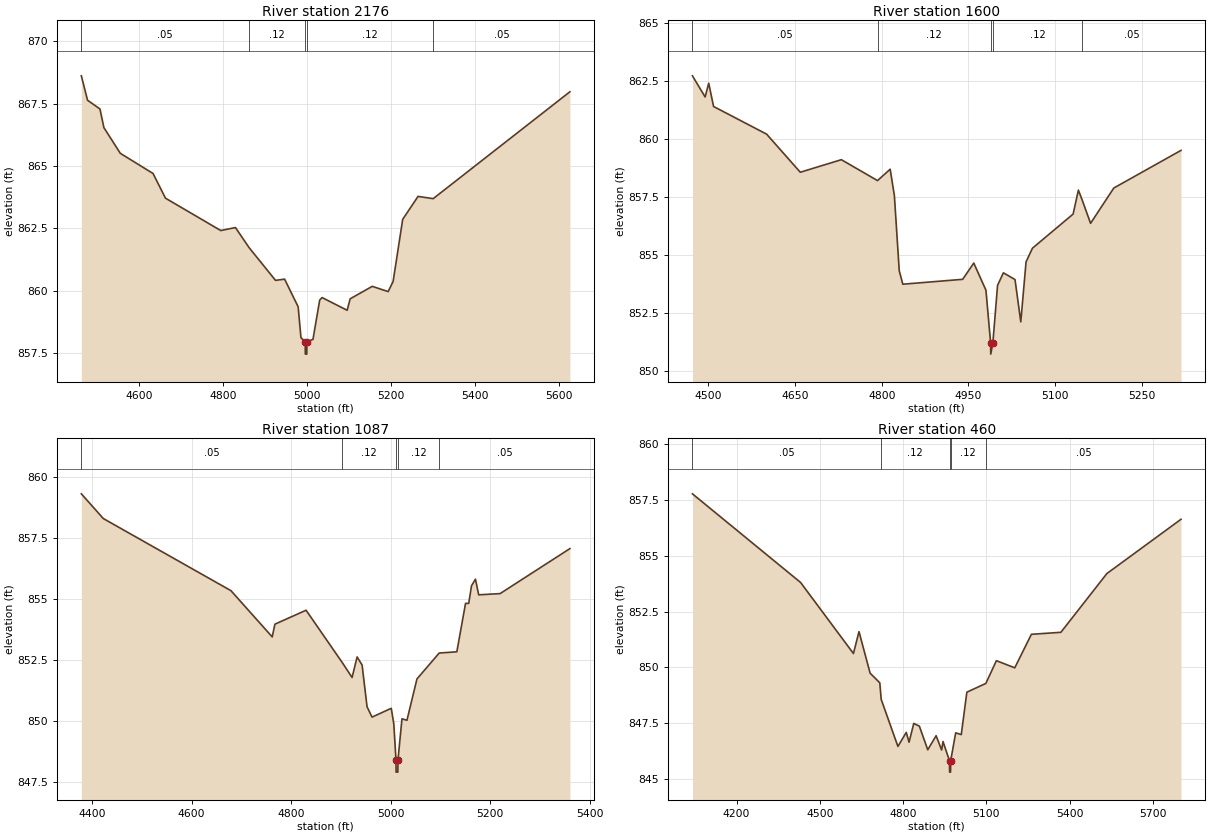
Type RM Length L Ch R = 1,2176,576,576,576
BEGIN DESCRIPTION:
S59 2.0
END DESCRIPTION:
XS GIS Cut Line= 3
      2301978.99      7079360.00      2301479.00      7079160.00
      2300929.01      7079460.00
#Sta/Elev= 30
  4461.9  868.62  4476.7  867.64  4506.3  867.29  4515.7  866.54  4554.8  865.51
  4632.9  864.70  4662.5  863.71  4794.4  862.41  4829.4  862.53  4862.1  861.72
  4925.0  860.41  4946.6  860.46  4978.9  859.35  4985.6  858.11  4995.7  857.95
  4996.0  857.45  4999.5  857.45  4999.7  857.95  5014.2  858.04  5030.3  859.62
  5036.0  859.72  5095.8  859.21  5102.9  859.67  5155.6  860.17  5193.6  859.96
  5205.4  860.37  5228.2  862.86  5264.8  863.78  5300.9  863.69  5626.9  867.98
#Mann=5,-1,0
  4461.9    0.05       0  4862.1    0.12       0  4995.7    0.07       0
  4999.7    0.12       0  5300.9    0.05       0
Bank Sta=4995.7,4999.7
Exp/Cntr=0.3,0.1

Type RM Length L Ch R = 1,1600,513,513,513
BEGIN DESCRIPTION:
S59 1.0
END DESCRIPTION:
XS GIS Cut Line= 3
      2301929.04      7078910.03      2301612.87      7078675.77
      2301163.43      7078625.83
#Sta/Elev= 30
  4472.2  862.71  4494.2  861.80  4500.4  862.39  4508.8  861.39  4600.6  860.20
  4658.9  858.56  4730.0  859.10  4792.6  858.20  4814.5  858.69  4821.8  857.55
  4830.2  854.32  4836.4  853.74  4940.0  853.95  4959.2  854.65  4980.3  853.48
  4988.3  851.23  4988.6  850.73  4992.3  851.23  5000.4  853.69  5010.5  854.23
  5030.6  853.94  5040.6  852.12  5049.7  854.70  5060.8  855.29  5131.2  856.76
  5140.3  857.79  5146.5  857.39  5161.4  856.36  5201.6  857.88  5317.9  859.50
#Mann=5,-1,0
  4472.2    0.05       0  4792.6    0.12       0  4988.3    0.07       0
  4992.3    0.12       0  5146.5    0.05       0
Bank Sta=4988.3,4992.3
Exp/Cntr=0.3,0.1

Type RM Length L Ch R = 1,1087,627,627,627
BEGIN DESCRIPTION:
S59 0.3
END DESCRIPTION:
XS GIS Cut Line= 4
      2301929.68      7078618.34      2301769.67      7078226.81
      2301418.95      7078206.39      2301286.75      7078365.71
#Sta/Elev= 30
  4378.7  859.30  4422.8  858.29  4679.2  855.34  4762.1  853.45  4767.5  853.97
  4830.1  854.54  4902.8  852.40  4922.5  851.79  4932.6  852.63  4942.6  852.30
  4952.6  850.59  4962.6  850.17  5001.2  850.53  5006.3  849.89  5010.7  848.42
  5010.9  847.92  5014.4  847.92  5014.7  848.42  5022.7  850.10  5032.7  850.04
  5052.8  851.73  5097.5  852.79  5132.9  852.84  5150.4  854.82  5156.8  854.82
  5162.4  855.54  5170.3  855.81  5176.8  855.17  5219.8  855.22  5360.0  857.06
#Mann=5,-1,0
  4378.7    0.05       0  4902.8    0.12       0  5010.7    0.07       0
  5014.7    0.12       0  5097.5    0.05       0
Bank Sta=5010.7,5014.7
Exp/Cntr=0.3,0.1

Type RM Length L Ch R = 1,460,0,0,0
BEGIN DESCRIPTION:
S59 0.2
END DESCRIPTION:
XS GIS Cut Line= 6
      2301916.08      7078499.17      2301878.62      7077712.67
      2301626.66      7077739.91      2301490.46      7077780.76
      2301350.85      7078059.97      2301282.80      7078315.16
#Sta/Elev= 30
  4041.3  857.77  4430.9  853.80  4621.1  850.62  4641.1  851.60  4681.2  849.74
  4716.0  849.31  4721.0  848.57  4781.3  846.46  4811.3  847.09  4821.4  846.65
  4838.4  847.49  4858.5  847.37  4888.7  846.31  4918.8  846.94  4938.7  846.30
  4943.7  846.68  4967.1  845.81  4967.4  845.31  4970.9  845.31  4971.1  845.81
  4989.3  847.07  5009.4  846.99  5029.5  848.89  5097.9  849.28  5135.9  850.30
  5202.0  849.98  5261.9  851.48  5368.1  851.57  5533.7  854.20  5800.6  856.63
#Mann=5,-1,0
  4041.3    0.05       0  4721.0    0.12       0  4967.1    0.07       0
  4971.1    0.12       0  5097.9    0.05       0
Bank Sta=4967.1,4971.1
Exp/Cntr=0.3,0.1

Chan Stop Cuts=-1