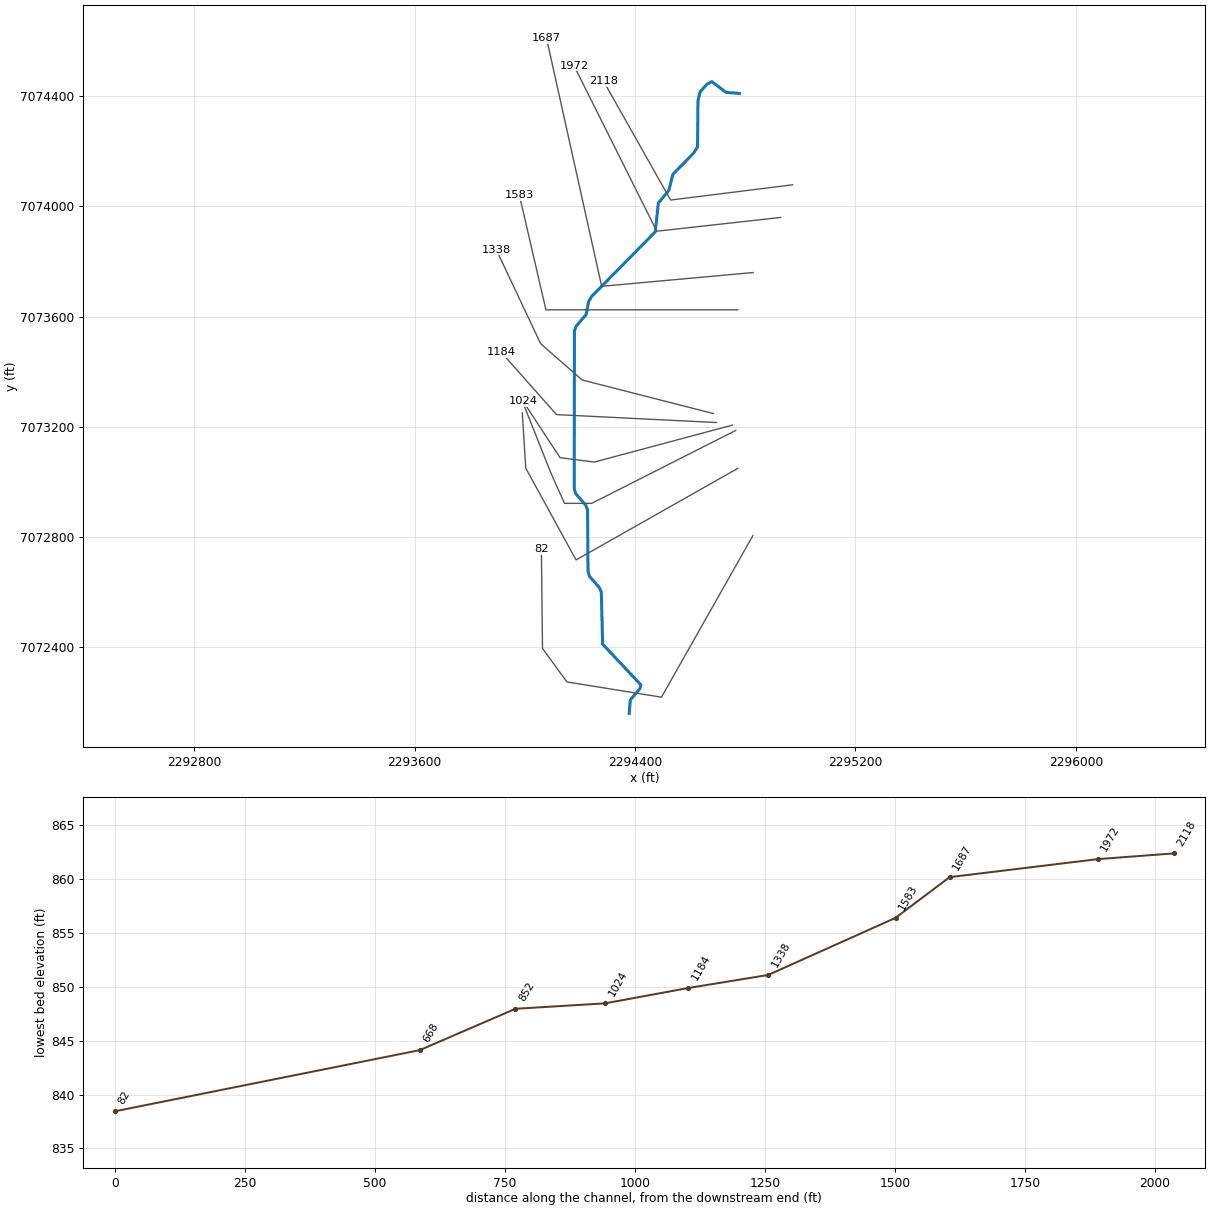
--- S80.prj (project) ---

Proj Title=S80 Base Level Engineering
Current Plan=p01
Default Exp/Contr=0.3,0.1
English Units
Geom File=g01
Flow File=f01
Plan File=p01
BEGIN DESCRIPTION:
S80
END DESCRIPTION:

--- S80.p01 (plan) ---

Plan Title=Multiple Run
Short Identifier=Multiple
Geom File=g01
Flow File=f01
Subcritical Flow
K Sum by GR= 0
Std Step Tol= 0.01
Critical Tol= 0.01
Num of Std Step Trials= 20
Max Error Tol= 0.3
Flow Tol Ratio= 0.001
Split Flow NTrial= 30
Split Flow Tol= 0.02
Split Flow Ratio= 0.02
Log Output Level= 0
Friction Slope Method= 1
Unsteady Friction Slope Method= 2
Unsteady Bridges Friction Slope Method= 1
Parabolic Critical Depth
Global Vel Dist=  1 , 1 , 1
Global Log Level= 0
CheckData=True
Encroach Param= -1, 0, 0, 0
BEGIN DESCRIPTION:
Multiple Run
END DESCRIPTION:

--- S80.f01 (steady flow) ---

Flow Title=Multiple
Number of Profiles=7
Profile Names=10-year,25-year,50-year,1pct_min,100-year,1pct_plu,500-year
River Rch & RM= S80,Reach-1,2118
     270     352     417     246     491     979     681
Boundary for River Rch & Prof#=S80,Reach-1,1
Up Type=0
Dn Type=3
Dn Slope=0.005
Boundary for River Rch & Prof#=S80,Reach-1,2
Up Type=0
Dn Type=3
Dn Slope=0.005
Boundary for River Rch & Prof#=S80,Reach-1,3
Up Type=0
Dn Type=3
Dn Slope=0.005
Boundary for River Rch & Prof#=S80,Reach-1,4
Up Type=0
Dn Type=3
Dn Slope=0.005
Boundary for River Rch & Prof#=S80,Reach-1,5
Up Type=0
Dn Type=3
Dn Slope=0.005
Boundary for River Rch & Prof#=S80,Reach-1,6
Up Type=0
Dn Type=3
Dn Slope=0.005
Boundary for River Rch & Prof#=S80,Reach-1,7
Up Type=0
Dn Type=3
Dn Slope=0.005

--- S80.g01 (geometry) ---

Geom Title=Existing Conditions

River Reach=S80,Reach-1
Reach XY= 30
      2294779.00      7074410.00      2294730.34      7074414.03
      2294678.67      7074453.06      2294661.82      7074443.95
      2294636.79      7074416.83      2294628.70      7074385.30
      2294626.93      7074215.86      2294612.54      7074193.25
      2294537.16      7074116.05      2294522.86      7074057.83
      2294484.77      7074012.32      2294473.48      7073907.57
      2294242.62      7073673.22      2294231.50      7073653.97
      2294222.86      7073607.83      2294187.09      7073566.08
      2294180.20      7073549.50      2294179.52      7072975.22
      2294184.75      7072957.67      2294220.86      7072916.06
      2294227.78      7072899.50      2294229.52      7072675.22
      2294234.75      7072657.67      2294270.86      7072616.06
      2294277.78      7072599.49      2294282.54      7072411.46
      2294421.41      7072263.39      2294418.11      7072250.10
      2294383.02      7072208.64      2294379.00      7072160.00

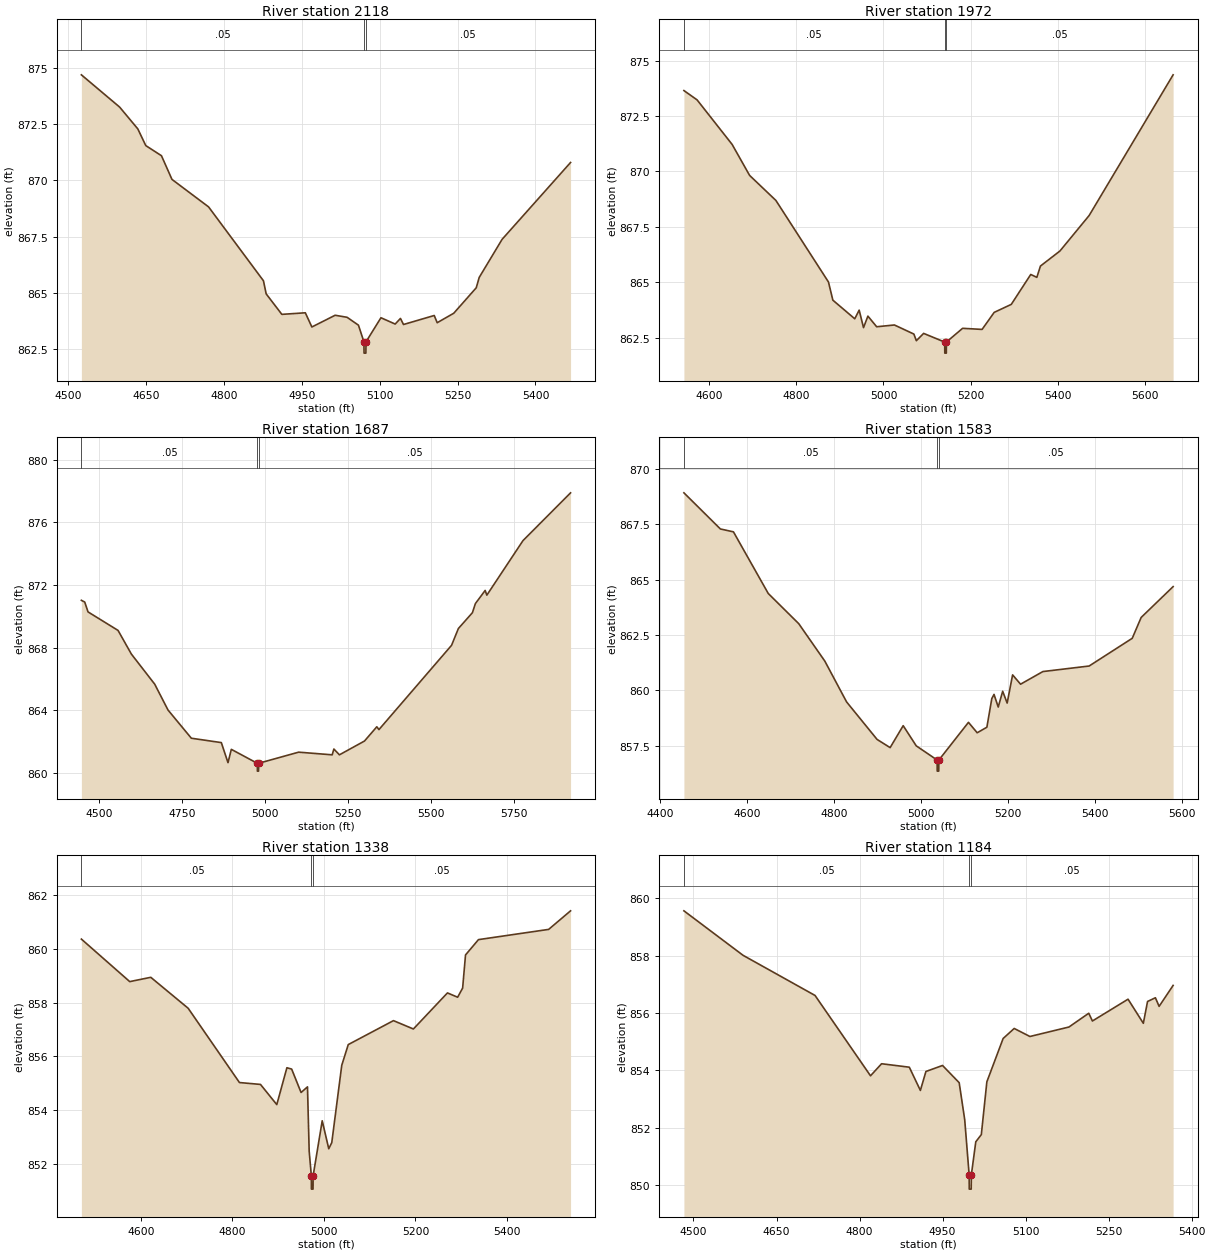
Type RM Length L Ch R = 1,2118,146,146,146
BEGIN DESCRIPTION:
1083
END DESCRIPTION:
XS GIS Cut Line= 3
      2294972.02      7074078.46      2294529.22      7074023.11
      2294285.69      7074454.81
#Sta/Elev= 30
  4525.7  874.68  4599.3  873.25  4634.4  872.28  4649.7  871.54  4679.9  871.09
  4700.1  870.04  4770.6  868.82  4876.3  865.54  4881.5  864.96  4911.7  864.05
  4956.9  864.12  4969.5  863.49  5014.3  864.01  5037.3  863.92  5059.2  863.57
  5069.7  862.83  5070.0  862.33  5073.5  862.33  5073.7  862.83  5102.5  863.90
  5129.9  863.62  5140.1  863.87  5145.9  863.60  5205.1  864.00  5210.8  863.68
  5242.7  864.10  5286.0  865.23  5291.7  865.69  5335.8  867.38  5467.6  870.79
#Mann=3,-1,0
  4525.7    0.05       0  5069.7   0.033       0  5073.7    0.05       0
Bank Sta=5069.7,5073.7
Exp/Cntr=0.3,0.1

Type RM Length L Ch R = 1,1972,285,285,285
BEGIN DESCRIPTION:
S80 2.0
END DESCRIPTION:
XS GIS Cut Line= 3
      2294929.01      7073960.00      2294479.00      7073910.00
      2294179.00      7074510.00
#Sta/Elev= 30
  4541.7  873.65  4571.9  873.23  4652.4  871.22  4692.6  869.82  4753.0  868.69
  4873.7  865.01  4883.8  864.19  4934.1  863.35  4944.2  863.74  4954.2  862.95
  4964.3  863.47  4984.4  862.99  5025.2  863.07  5069.9  862.66  5075.5  862.36
  5092.3  862.69  5140.6  862.30  5140.9  861.80  5144.4  861.80  5144.6  862.30
  5181.8  862.92  5226.5  862.87  5254.4  863.64  5293.6  864.00  5338.3  865.35
  5352.3  865.22  5360.6  865.73  5405.4  866.41  5472.4  868.01  5665.3  874.36
#Mann=3,-1,0
  4541.7    0.05       0  5140.6   0.033       0  5144.6    0.05       0
Bank Sta=5140.6,5144.6
Exp/Cntr=0.3,0.1

Type RM Length L Ch R = 1,1687,104,104,104
BEGIN DESCRIPTION:
S80 1.0
END DESCRIPTION:
XS GIS Cut Line= 3
      2294829.04      7073760.00      2294279.00      7073710.00
      2294078.99      7074610.03
#Sta/Elev= 30
  4447.4  871.03  4457.5  870.92  4467.5  870.29  4557.9  869.11  4598.1  867.60
  4668.4  865.68  4708.5  864.03  4778.8  862.23  4869.2  861.95  4889.3  860.67
  4899.3  861.52  4977.6  860.63  4977.9  860.13  4981.4  860.13  4981.6  860.63
  5102.2  861.34  5203.3  861.17  5208.4  861.54  5225.1  861.17  5300.6  862.05
  5337.8  862.96  5344.2  862.78  5563.1  868.16  5583.6  869.23  5625.9  870.24
  5634.8  870.82  5664.3  871.66  5669.4  871.36  5778.3  874.84  5921.7  877.89
#Mann=3,-1,0
  4447.4    0.05       0  4977.6   0.033       0  4981.6    0.05       0
Bank Sta=4977.6,4981.6
Exp/Cntr=0.3,0.1

Type RM Length L Ch R = 1,1583,245,245,245
BEGIN DESCRIPTION:
1087
END DESCRIPTION:
XS GIS Cut Line= 3
      2294772.76      7073624.61      2294076.68      7073624.61
      2293980.16      7074041.49
#Sta/Elev= 30
  4455.1  868.91  4538.9  867.28  4568.9  867.15  4648.9  864.37  4718.9  863.01
  4778.9  861.32  4828.9  859.48  4898.9  857.79  4928.9  857.42  4958.9  858.41
  4988.9  857.50  5036.9  856.86  5037.1  856.36  5040.6  856.36  5040.9  856.86
  5108.9  858.56  5128.9  858.09  5151.2  858.34  5162.5  859.63  5167.6  859.82
  5177.3  859.25  5187.5  859.96  5197.8  859.43  5210.3  860.70  5228.6  860.28
  5279.9  860.85  5386.2  861.10  5485.2  862.35  5505.7  863.29  5579.1  864.68
#Mann=3,-1,0
  4455.1    0.05       0  5036.9    0.05       0  5040.9    0.05       0
Bank Sta=5036.9,5040.9
Exp/Cntr=0.3,0.1

Type RM Length L Ch R = 1,1338,154,154,154
BEGIN DESCRIPTION:
1086
END DESCRIPTION:
XS GIS Cut Line= 4
      2294684.23      7073248.23      2294208.20      7073370.00
      2294057.54      7073501.84      2293896.36      7073843.36
#Sta/Elev= 30
  4469.8  860.36  4575.5  858.78  4621.5  858.94  4703.2  857.79  4815.3  855.03
  4861.3  854.96  4896.9  854.21  4919.0  855.58  4929.4  855.53  4950.0  854.66
  4964.0  854.87  4967.7  852.48  4972.4  851.57  4972.6  851.07  4976.1  851.07
  4976.4  851.57  4996.2  853.61  5010.5  852.57  5017.1  852.80  5038.9  855.67
  5053.1  856.44  5151.9  857.33  5195.5  857.02  5269.9  858.36  5292.2  858.20
  5303.1  858.54  5309.4  859.77  5337.7  860.34  5491.1  860.72  5539.0  861.41
#Mann=3,-1,0
  4469.8    0.05       0  4972.4   0.033       0  4976.4    0.05       0
Bank Sta=4972.4,4976.4
Exp/Cntr=0.3,0.1

Type RM Length L Ch R = 1,1184,160,160,160
BEGIN DESCRIPTION:
1684
END DESCRIPTION:
XS GIS Cut Line= 3
      2294695.66      7073215.65      2294115.24      7073244.35
      2293914.35      7073470.75
#Sta/Elev= 30
  4482.7  859.56  4589.5  858.01  4719.6  856.61  4819.8  853.81  4839.8  854.23
  4889.9  854.11  4909.9  853.30  4919.9  853.96  4949.9  854.17  4980.0  853.57
  4990.0  852.28  4998.0  850.36  4998.2  849.86  5001.7  849.86  5002.0  850.36
  5010.0  851.51  5020.0  851.76  5030.0  853.60  5059.4  855.11  5079.4  855.46
  5107.8  855.18  5178.3  855.51  5214.1  855.99  5220.7  855.72  5285.1  856.48
  5312.7  855.64  5320.3  856.40  5334.5  856.53  5341.2  856.23  5366.5  856.96
#Mann=3,-1,0
  4482.7    0.05       0  4998.0   0.033       0  5002.0    0.05       0
Bank Sta=4998,5002
Exp/Cntr=0.3,0.1

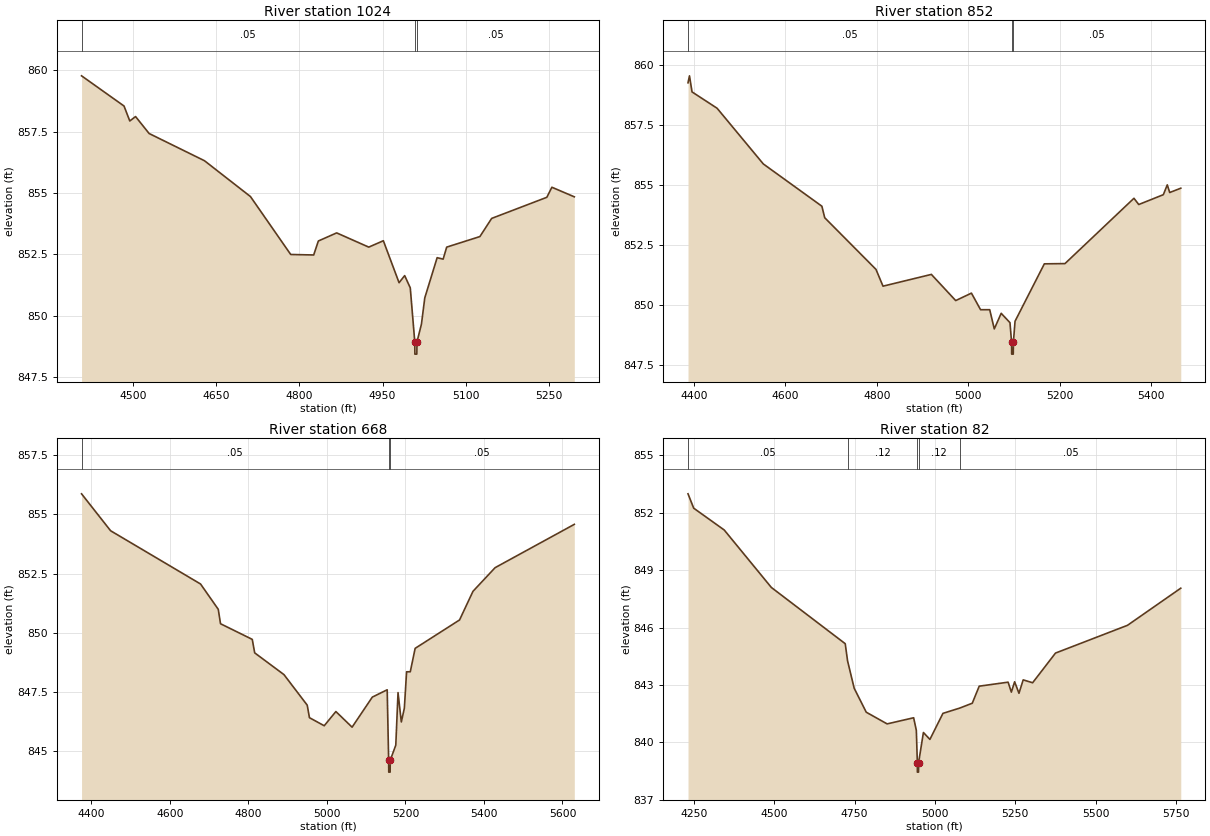
Type RM Length L Ch R = 1,1024,172,172,172
BEGIN DESCRIPTION:
1682
END DESCRIPTION:
XS GIS Cut Line= 4
      2294752.96      7073206.07      2294252.36      7073072.15
      2294128.00      7073088.10      2293994.07      7073292.19
#Sta/Elev= 30
  4407.8  859.78  4484.3  858.55  4494.7  857.94  4505.1  858.12  4529.5  857.43
  4629.3  856.32  4712.1  854.86  4784.6  852.50  4826.0  852.48  4834.4  853.05
  4867.4  853.38  4925.2  852.80  4951.5  853.06  4979.8  851.35  4989.9  851.64
  5000.0  851.14  5008.1  848.94  5008.3  848.44  5011.8  848.44  5012.1  848.94
  5020.1  849.66  5026.1  850.73  5048.4  852.37  5059.2  852.31  5065.6  852.80
  5125.4  853.23  5146.6  853.97  5246.0  854.83  5255.1  855.24  5295.5  854.85
#Mann=3,-1,0
  4407.8    0.05       0  5008.1   0.033       0  5012.1    0.05       0
Bank Sta=5008.1,5012.1
Exp/Cntr=0.3,0.1

Type RM Length L Ch R = 1,852,184,184,184
BEGIN DESCRIPTION:
s80 11.11
END DESCRIPTION:
XS GIS Cut Line= 5
      2294765.77      7073186.95      2294242.80      7072922.28
      2294143.94      7072922.28      2294092.92      7073037.08
      2293994.24      7073285.37
#Sta/Elev= 30
  4387.0  859.24  4390.2  859.53  4395.8  858.86  4450.6  858.18  4551.7  855.86
  4679.8  854.10  4686.0  853.62  4798.1  851.47  4813.5  850.77  4919.3  851.26
  4972.5  850.17  5006.9  850.48  5026.9  849.79  5046.9  849.79  5056.9  848.99
  5072.0  849.64  5091.2  849.25  5094.7  848.44  5094.9  847.94  5098.4  847.94
  5098.7  848.44  5102.3  849.31  5166.4  851.70  5211.5  851.71  5362.4  854.43
  5372.9  854.17  5426.7  854.58  5435.3  854.99  5440.6  854.67  5464.8  854.85
#Mann=3,-1,0
  4387.0    0.05       0  5094.7   0.033       0  5098.7    0.05       0
Bank Sta=5094.7,5098.7
Exp/Cntr=0.3,0.1

Type RM Length L Ch R = 1,668,586,586,586
BEGIN DESCRIPTION:
1085
END DESCRIPTION:
XS GIS Cut Line= 4
      2294772.74      7073048.98      2294186.06      7072716.90
      2294003.64      7073049.83      2293990.88      7073250.74
#Sta/Elev= 30
  4375.0  855.87  4449.0  854.31  4678.1  852.06  4723.2  850.99  4729.0  850.38
  4809.8  849.72  4816.0  849.15  4890.6  848.23  4949.8  846.94  4955.5  846.41
  4993.1  846.07  5022.8  846.67  5064.1  846.01  5115.6  847.28  5153.5  847.59
  5157.2  844.61  5157.5  844.11  5161.0  844.11  5161.2  844.61  5175.4  845.25
  5181.1  847.47  5189.5  846.23  5197.2  846.81  5202.9  848.35  5212.3  848.35
  5224.7  849.34  5337.8  850.54  5372.0  851.75  5428.4  852.75  5630.1  854.58
#Mann=3,-1,0
  4375.0    0.05       0  5157.2   0.033       0  5161.2    0.05       0
Bank Sta=5157.2,5161.2
Exp/Cntr=0.3,0.1

Type RM Length L Ch R = 1,82,0,0,0
BEGIN DESCRIPTION:
1084
END DESCRIPTION:
XS GIS Cut Line= 5
      2294828.07      7072805.41      2294496.01      7072218.77
      2294152.85      7072274.12      2294064.29      7072395.88
      2294060.20      7072755.70
#Sta/Elev= 30
  4232.3  852.99  4250.0  852.24  4344.9  851.10  4491.3  848.10  4721.1  845.16
  4728.4  844.26  4749.0  842.83  4786.5  841.58  4851.4  840.97  4933.8  841.29
  4942.2  840.63  4945.3  838.95  4945.5  838.45  4949.0  838.45  4949.3  838.95
  4964.2  840.52  4984.4  840.16  5024.9  841.52  5077.8  841.80  5116.1  842.05
  5137.7  842.94  5227.5  843.15  5237.6  842.63  5247.8  843.17  5261.3  842.57
  5274.4  843.27  5303.8  843.12  5374.9  844.67  5598.7  846.12  5764.4  848.06
#Mann=5,-1,0
  4232.3    0.05       0  4728.4    0.12       0  4945.3    0.07       0
  4949.3    0.12       0  5077.8    0.05       0
Bank Sta=4945.3,4949.3
Exp/Cntr=0.3,0.1

Chan Stop Cuts=-1