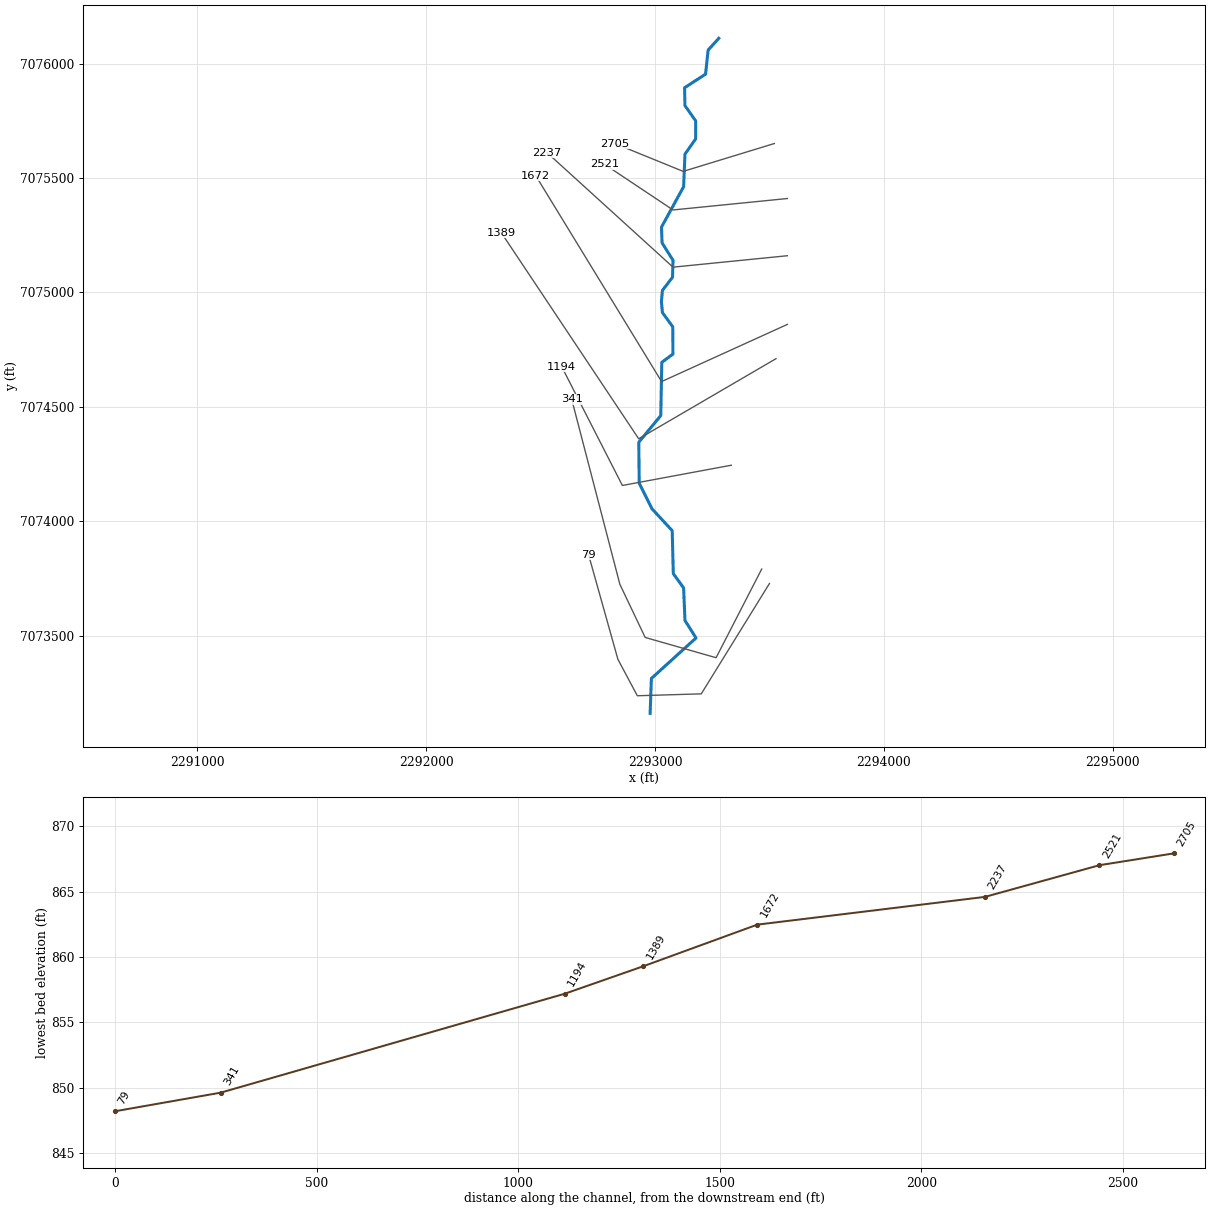
--- S82.prj (project) ---

Proj Title=S82 Base Level Engineering
Current Plan=p01
Default Exp/Contr=0.3,0.1
English Units
Geom File=g01
Flow File=f01
Plan File=p01
BEGIN DESCRIPTION:
S82
END DESCRIPTION:

--- S82.p01 (plan) ---

Plan Title=Multiple Run
Short Identifier=Multiple
Geom File=g01
Flow File=f01
Subcritical Flow
K Sum by GR= 0
Std Step Tol= 0.01
Critical Tol= 0.01
Num of Std Step Trials= 20
Max Error Tol= 0.3
Flow Tol Ratio= 0.001
Split Flow NTrial= 30
Split Flow Tol= 0.02
Split Flow Ratio= 0.02
Log Output Level= 0
Friction Slope Method= 1
Unsteady Friction Slope Method= 2
Unsteady Bridges Friction Slope Method= 1
Parabolic Critical Depth
Global Vel Dist=  1 , 1 , 1
Global Log Level= 0
CheckData=True
Encroach Param= -1, 0, 0, 0
BEGIN DESCRIPTION:
Multiple Run
END DESCRIPTION:

--- S82.f01 (steady flow) ---

Flow Title=Multiple
Number of Profiles=7
Profile Names=10-year,25-year,50-year,1pct_min,100-year,1pct_plu,500-year
River Rch & RM= S82,Reach-1,2705
     342     452     540     321     640    1280     902
Boundary for River Rch & Prof#=S82,Reach-1,1
Up Type=0
Dn Type=3
Dn Slope=0.005
Boundary for River Rch & Prof#=S82,Reach-1,2
Up Type=0
Dn Type=3
Dn Slope=0.005
Boundary for River Rch & Prof#=S82,Reach-1,3
Up Type=0
Dn Type=3
Dn Slope=0.005
Boundary for River Rch & Prof#=S82,Reach-1,4
Up Type=0
Dn Type=3
Dn Slope=0.005
Boundary for River Rch & Prof#=S82,Reach-1,5
Up Type=0
Dn Type=3
Dn Slope=0.005
Boundary for River Rch & Prof#=S82,Reach-1,6
Up Type=0
Dn Type=3
Dn Slope=0.005
Boundary for River Rch & Prof#=S82,Reach-1,7
Up Type=0
Dn Type=3
Dn Slope=0.005

--- S82.g01 (geometry) ---

Geom Title=Existing Conditions

River Reach=S82,Reach-1
Reach XY= 30
      2293279.00      7076110.00      2293232.39      7076058.59
      2293221.22      7075953.56      2293129.54      7075894.10
      2293131.13      7075816.06      2293177.89      7075749.45
      2293177.90      7075670.55      2293131.27      7075604.06
      2293125.24      7075461.56      2293028.59      7075285.00
      2293031.17      7075215.97      2293079.09      7075139.90
      2293076.83      7075065.97      2293032.71      7075008.40
      2293028.18      7074960.00      2293032.71      7074911.60
      2293077.80      7074849.48      2293078.72      7074730.30
      2293029.96      7074694.04      2293025.45      7074461.47
      2292929.39      7074344.84      2292931.24      7074165.93
      2292987.16      7074053.95      2293075.45      7073958.53
      2293080.22      7073770.51      2293125.21      7073708.43
      2293131.31      7073565.91      2293179.47      7073489.53
      2292984.43      7073312.47      2292979.00      7073160.00

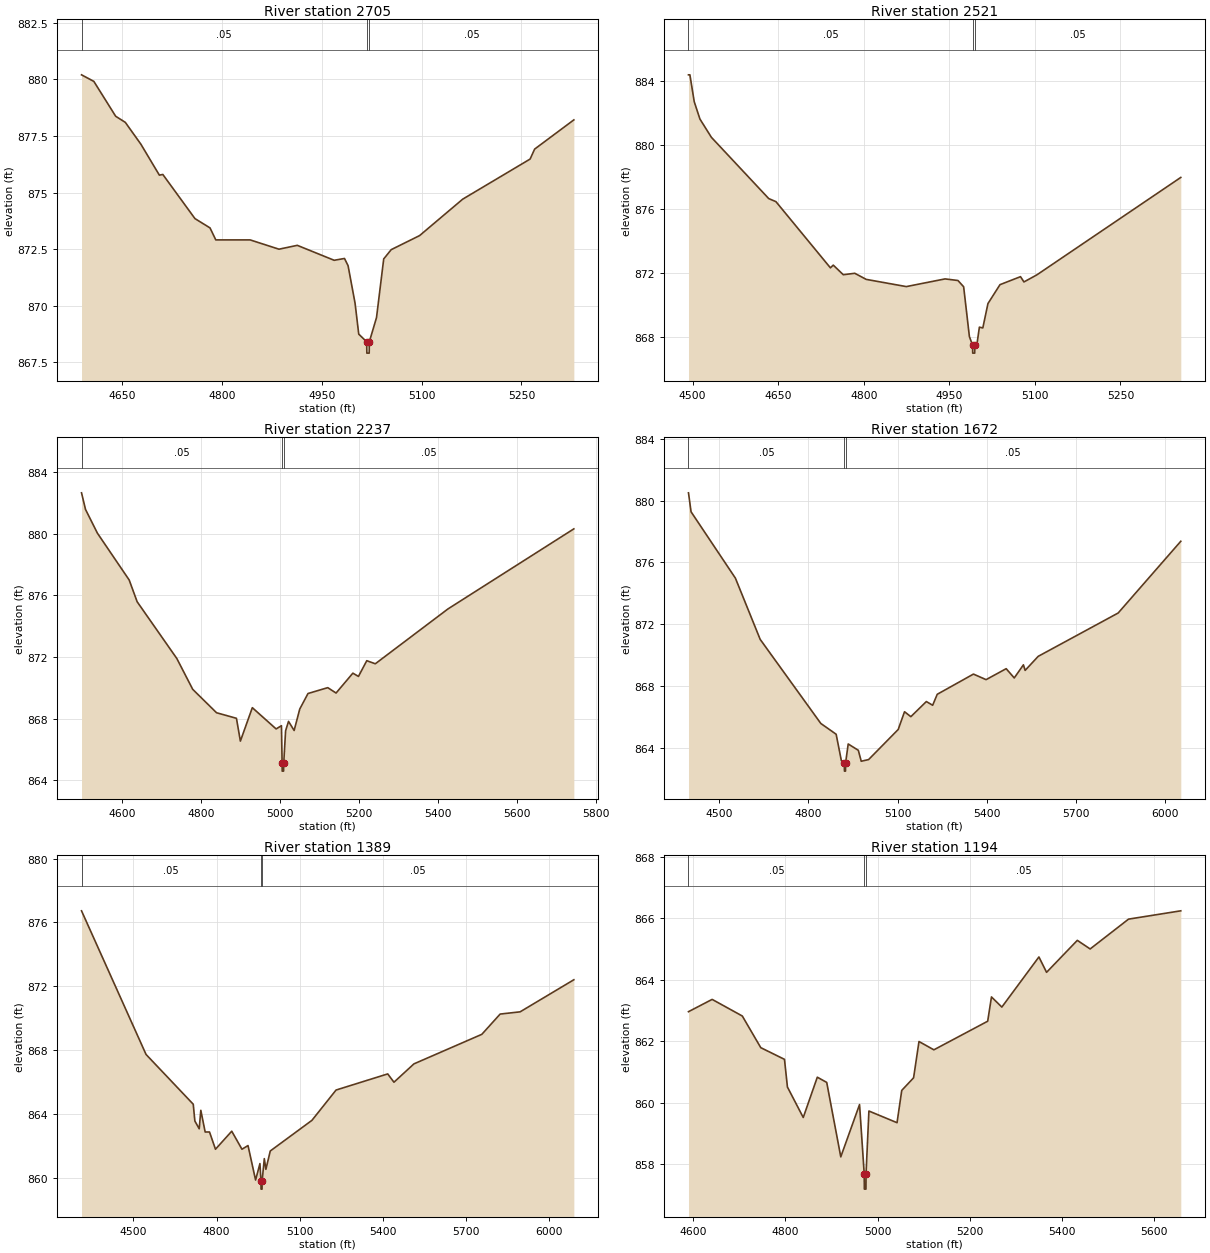
Type RM Length L Ch R = 1,2705,184,184,184
BEGIN DESCRIPTION:
1090
END DESCRIPTION:
XS GIS Cut Line= 3
      2293521.92      7075650.35      2293123.38      7075528.58
      2292824.47      7075650.35
#Sta/Elev= 30
  4589.2  880.20  4607.7  879.91  4640.5  878.37  4655.0  878.10  4678.5  877.13
  4706.1  875.77  4711.3  875.80  4759.6  873.85  4782.2  873.44  4790.9  872.91
  4842.5  872.91  4885.8  872.50  4913.3  872.67  4968.7  872.01  4984.2  872.09
  4989.6  871.77  5000.1  870.11  5005.6  868.75  5017.5  868.41  5017.8  867.91
  5021.3  867.91  5021.5  868.41  5032.3  869.48  5043.1  872.07  5054.4  872.48
  5097.0  873.10  5161.8  874.71  5263.0  876.48  5269.8  876.92  5328.7  878.21
#Mann=3,-1,0
  4589.2    0.05       0  5017.5   0.033       0  5021.5    0.05       0
Bank Sta=5017.5,5021.5
Exp/Cntr=0.3,0.1

Type RM Length L Ch R = 1,2521,284,284,284
BEGIN DESCRIPTION:
S82 4.0
END DESCRIPTION:
XS GIS Cut Line= 3
      2293579.02      7075410.00      2293079.00      7075360.00
      2292778.98      7075560.02
#Sta/Elev= 30
  4492.8  884.37  4495.3  884.37  4502.9  882.69  4512.9  881.61  4533.0  880.47
  4633.5  876.65  4646.1  876.46  4741.6  872.33  4746.6  872.50  4764.2  871.90
  4784.3  871.99  4804.4  871.61  4874.7  871.16  4942.6  871.64  4965.2  871.54
  4975.2  871.15  4985.3  868.04  4990.8  867.51  4991.1  867.01  4994.6  867.01
  4994.8  867.51  4998.3  867.51  5002.8  868.63  5008.8  868.58  5017.8  870.10
  5038.9  871.28  5074.9  871.78  5080.9  871.45  5103.5  871.89  5355.9  877.97
#Mann=3,-1,0
  4492.8    0.05       0  4990.8   0.033       0  4994.8    0.05       0
Bank Sta=4990.8,4994.8
Exp/Cntr=0.3,0.1

Type RM Length L Ch R = 1,2237,565,565,565
BEGIN DESCRIPTION:
S82 3.0
END DESCRIPTION:
XS GIS Cut Line= 3
      2293579.01      7075160.00      2293079.00      7075110.00
      2292529.00      7075610.00
#Sta/Elev= 30
  4498.3  882.66  4508.4  881.58  4538.5  880.04  4618.9  877.00  4639.0  875.59
  4739.5  871.90  4779.7  869.90  4840.0  868.38  4890.3  868.02  4900.3  866.54
  4930.5  868.71  4990.7  867.33  5004.2  867.54  5005.9  865.09  5006.1  864.59
  5009.6  864.59  5009.9  865.09  5014.7  867.21  5022.1  867.82  5036.3  867.23
  5050.5  868.62  5071.4  869.63  5121.4  870.01  5142.4  869.66  5184.9  870.95
  5199.1  870.74  5220.1  871.76  5241.7  871.56  5425.5  875.12  5744.1  880.32
#Mann=3,-1,0
  4498.3    0.05       0  5005.9   0.033       0  5009.9    0.05       0
Bank Sta=5005.9,5009.9
Exp/Cntr=0.3,0.1

Type RM Length L Ch R = 1,1672,283,283,283
BEGIN DESCRIPTION:
S82 2.0
END DESCRIPTION:
XS GIS Cut Line= 3
      2293578.96      7074859.98      2293029.00      7074610.00
      2292478.98      7075510.03
#Sta/Elev= 30
  4395.7  880.51  4404.4  879.28  4553.8  874.98  4637.3  871.01  4841.6  865.56
  4893.3  864.86  4910.8  863.15  4920.9  862.97  4921.2  862.47  4924.7  862.47
  4924.9  862.97  4933.9  864.23  4968.0  863.82  4977.8  863.11  5002.7  863.22
  5102.4  865.17  5123.7  866.32  5145.0  866.00  5197.2  866.98  5218.5  866.74
  5233.9  867.45  5355.9  868.76  5398.5  868.40  5466.2  869.11  5493.4  868.51
  5524.3  869.36  5530.1  869.00  5574.1  869.91  5843.6  872.72  6054.6  877.37
#Mann=3,-1,0
  4395.7    0.05       0  4920.9   0.033       0  4924.9    0.05       0
Bank Sta=4920.9,4924.9
Exp/Cntr=0.3,0.1

Type RM Length L Ch R = 1,1389,195,195,195
BEGIN DESCRIPTION:
S82 1.0
END DESCRIPTION:
XS GIS Cut Line= 3
      2293528.98      7074709.99      2292929.00      7074360.00
      2292328.98      7075260.03
#Sta/Elev= 30
  4312.6  876.73  4545.4  867.73  4715.7  864.61  4721.5  863.56  4737.2  863.07
  4743.0  864.23  4758.7  862.87  4774.4  862.87  4795.9  861.79  4854.6  862.92
  4891.4  861.79  4913.3  862.02  4940.6  859.86  4956.3  860.89  4960.1  859.79
  4960.4  859.29  4963.9  859.29  4964.1  859.79  4972.1  861.20  4977.8  860.53
  4993.6  861.68  5143.9  863.60  5231.0  865.50  5417.3  866.51  5439.9  865.99
  5512.0  867.14  5756.9  868.99  5823.0  870.26  5895.1  870.40  6088.9  872.41
#Mann=3,-1,0
  4312.6    0.05       0  4960.1   0.033       0  4964.1    0.05       0
Bank Sta=4960.1,4964.1
Exp/Cntr=0.3,0.1

Type RM Length L Ch R = 1,1194,853,853,853
BEGIN DESCRIPTION:
1089
END DESCRIPTION:
XS GIS Cut Line= 3
      2293333.71      7074244.50      2292857.71      7074155.95
      2292592.33      7074675.64
#Sta/Elev= 30
  4589.8  862.96  4641.1  863.36  4706.5  862.82  4746.6  861.79  4798.0  861.41
  4804.4  860.51  4838.7  859.52  4869.2  860.83  4889.6  860.66  4920.1  858.24
  4960.8  859.94  4970.9  857.69  4971.2  857.19  4974.7  857.19  4974.9  857.69
  4981.1  859.73  5042.1  859.35  5052.3  860.40  5078.0  860.81  5089.7  861.99
  5122.0  861.72  5238.7  862.65  5246.9  863.44  5269.4  863.11  5349.8  864.74
  5366.4  864.24  5433.1  865.28  5460.9  865.00  5544.2  865.97  5657.5  866.24
#Mann=3,-1,0
  4589.8    0.05       0  4970.9   0.033       0  4974.9    0.05       0
Bank Sta=4970.9,4974.9
Exp/Cntr=0.3,0.1

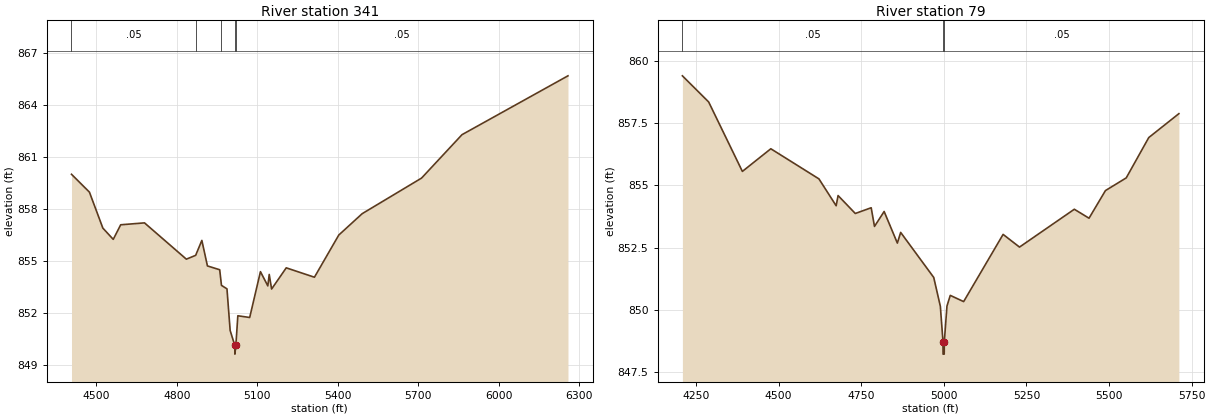
Type RM Length L Ch R = 1,341,262,262,262
BEGIN DESCRIPTION:
1088
END DESCRIPTION:
XS GIS Cut Line= 5
      2293466.54      7073790.66      2293267.28      7073403.21
      2292957.33      7073491.77      2292846.64      7073724.23
      2292636.32      7074532.30
#Sta/Elev= 30
  4407.2  860.00  4474.1  858.97  4524.1  856.90  4562.8  856.25  4590.6  857.09
  4679.3  857.20  4835.3  855.11  4870.0  855.33  4893.1  856.19  4913.9  854.72
  4959.6  854.50  4966.2  853.60  4986.7  853.40  4998.6  851.00  5015.9  850.14
  5016.2  849.64  5019.9  850.14  5027.2  851.85  5071.4  851.75  5111.5  854.39
  5139.0  853.57  5144.2  854.23  5153.1  853.39  5207.6  854.61  5312.7  854.07
  5403.5  856.50  5490.7  857.73  5712.0  859.78  5862.7  862.28  6257.7  865.67
#Mann=5,-1,0
  4407.2    0.05       0  4870.0    0.12       0  4966.2    0.05       0
  5015.9   0.033       0  5019.9    0.05       0
Bank Sta=5015.9,5019.9
Exp/Cntr=0.3,0.1

Type RM Length L Ch R = 1,79,0,0,0
BEGIN DESCRIPTION:
S82 0.1
END DESCRIPTION:
XS GIS Cut Line= 5
      2293500.54      7073727.66      2293202.43      7073245.30
      2292922.97      7073237.02      2292838.10      7073396.41
      2292709.74      7073853.95
#Sta/Elev= 30
  4209.1  859.40  4288.6  858.35  4390.6  855.56  4476.7  856.47  4622.3  855.26
  4674.4  854.18  4680.2  854.59  4732.3  853.87  4780.4  854.10  4790.4  853.35
  4819.6  853.95  4859.6  852.68  4869.6  853.11  4969.7  851.30  4989.7  850.14
  4997.7  848.72  4997.9  848.22  5001.4  848.22  5001.7  848.72  5009.7  850.15
  5019.7  850.58  5060.2  850.33  5179.6  853.03  5229.2  852.52  5395.1  854.04
  5439.6  853.68  5489.3  854.79  5552.2  855.30  5620.4  856.92  5711.5  857.88
#Mann=3,-1,0
  4209.1    0.05       0  4997.7   0.033       0  5001.7    0.05       0
Bank Sta=4997.7,5001.7
Exp/Cntr=0.3,0.1

Chan Stop Cuts=-1