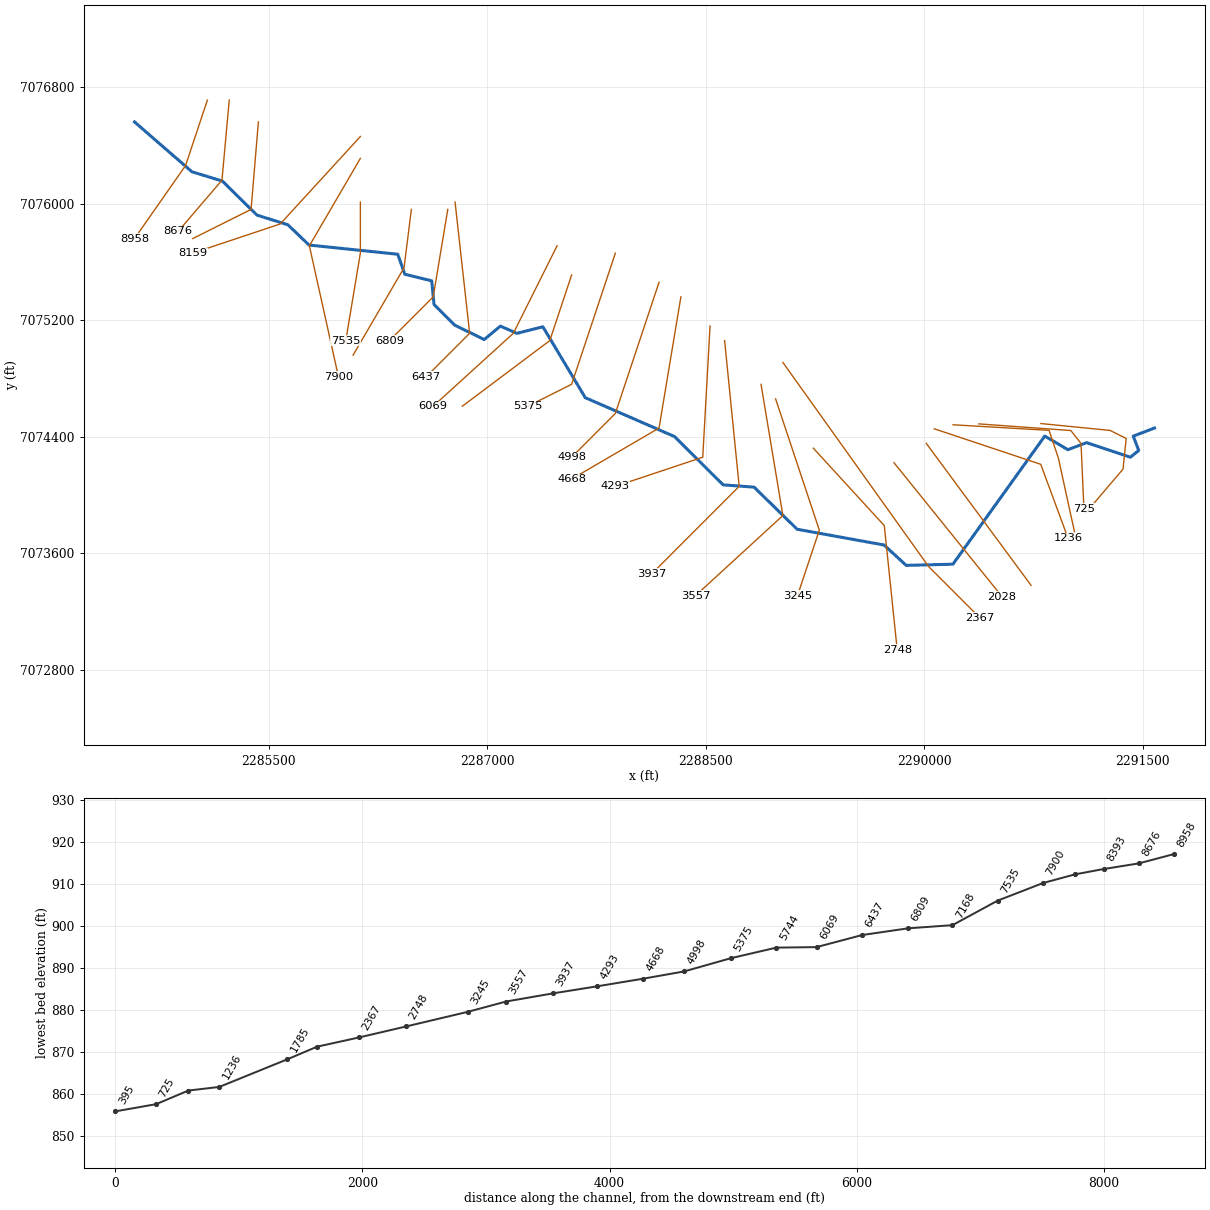
--- S83.prj (project) ---

Proj Title=S83 Base Level Engineering
Current Plan=p01
Default Exp/Contr=0.3,0.1
English Units
Geom File=g01
Flow File=f01
Plan File=p01
BEGIN DESCRIPTION:
S83
END DESCRIPTION:

--- S83.p01 (plan) ---

Plan Title=Multiple Run
Short Identifier=Multiple
Geom File=g01
Flow File=f01
Subcritical Flow
K Sum by GR= 0
Std Step Tol= 0.01
Critical Tol= 0.01
Num of Std Step Trials= 20
Max Error Tol= 0.3
Flow Tol Ratio= 0.001
Split Flow NTrial= 30
Split Flow Tol= 0.02
Split Flow Ratio= 0.02
Log Output Level= 0
Friction Slope Method= 1
Unsteady Friction Slope Method= 2
Unsteady Bridges Friction Slope Method= 1
Parabolic Critical Depth
Global Vel Dist=  1 , 1 , 1
Global Log Level= 0
CheckData=True
Encroach Param= -1, 0, 0, 0
BEGIN DESCRIPTION:
Multiple Run
END DESCRIPTION:

--- S83.f01 (steady flow) ---

Flow Title=Multiple
Number of Profiles=7
Profile Names=10-year,25-year,50-year,1pct_min,100-year,1pct_plu,500-year
River Rch & RM= S83,Reach-1,8958
     388     519     625     375     748    1490    1070
River Rch & RM= S83,Reach-1,7535
     566     772     943     571    1140    2270    1670
River Rch & RM= S83,Reach-1,2748
     656     904    1110     675    1350    2690    1990
Boundary for River Rch & Prof#=S83,Reach-1,1
Up Type=0
Dn Type=3
Dn Slope=0.005
Boundary for River Rch & Prof#=S83,Reach-1,2
Up Type=0
Dn Type=3
Dn Slope=0.005
Boundary for River Rch & Prof#=S83,Reach-1,3
Up Type=0
Dn Type=3
Dn Slope=0.005
Boundary for River Rch & Prof#=S83,Reach-1,4
Up Type=0
Dn Type=3
Dn Slope=0.005
Boundary for River Rch & Prof#=S83,Reach-1,5
Up Type=0
Dn Type=3
Dn Slope=0.005
Boundary for River Rch & Prof#=S83,Reach-1,6
Up Type=0
Dn Type=3
Dn Slope=0.005
Boundary for River Rch & Prof#=S83,Reach-1,7
Up Type=0
Dn Type=3
Dn Slope=0.005

--- S83.g01 (geometry) ---

Geom Title=Existing Conditions

River Reach=S83,Reach-1
Reach XY= 30
      2284579.00      7076560.00      2284972.94      7076218.14
      2285181.43      7076154.48      2285419.32      7075920.76
      2285631.43      7075854.48      2285776.55      7075715.46
      2286385.52      7075652.32      2286434.08      7075515.04
      2286618.68      7075470.18      2286634.47      7075307.55
      2286776.70      7075165.83      2286979.08      7075067.30
      2287089.62      7075159.38      2287204.00      7075109.61
      2287381.67      7075154.70      2287672.93      7074668.13
      2288285.05      7074401.84      2288618.88      7074070.34
      2288831.45      7074054.54      2289126.71      7073765.81
      2289723.09      7073657.76      2289875.43      7073517.93
      2290196.05      7073526.07      2290826.46      7074405.04
      2290985.04      7074311.63      2291113.60      7074359.90
      2291413.94      7074259.95      2291471.27      7074306.29
      2291433.76      7074404.43      2291579.00      7074460.00

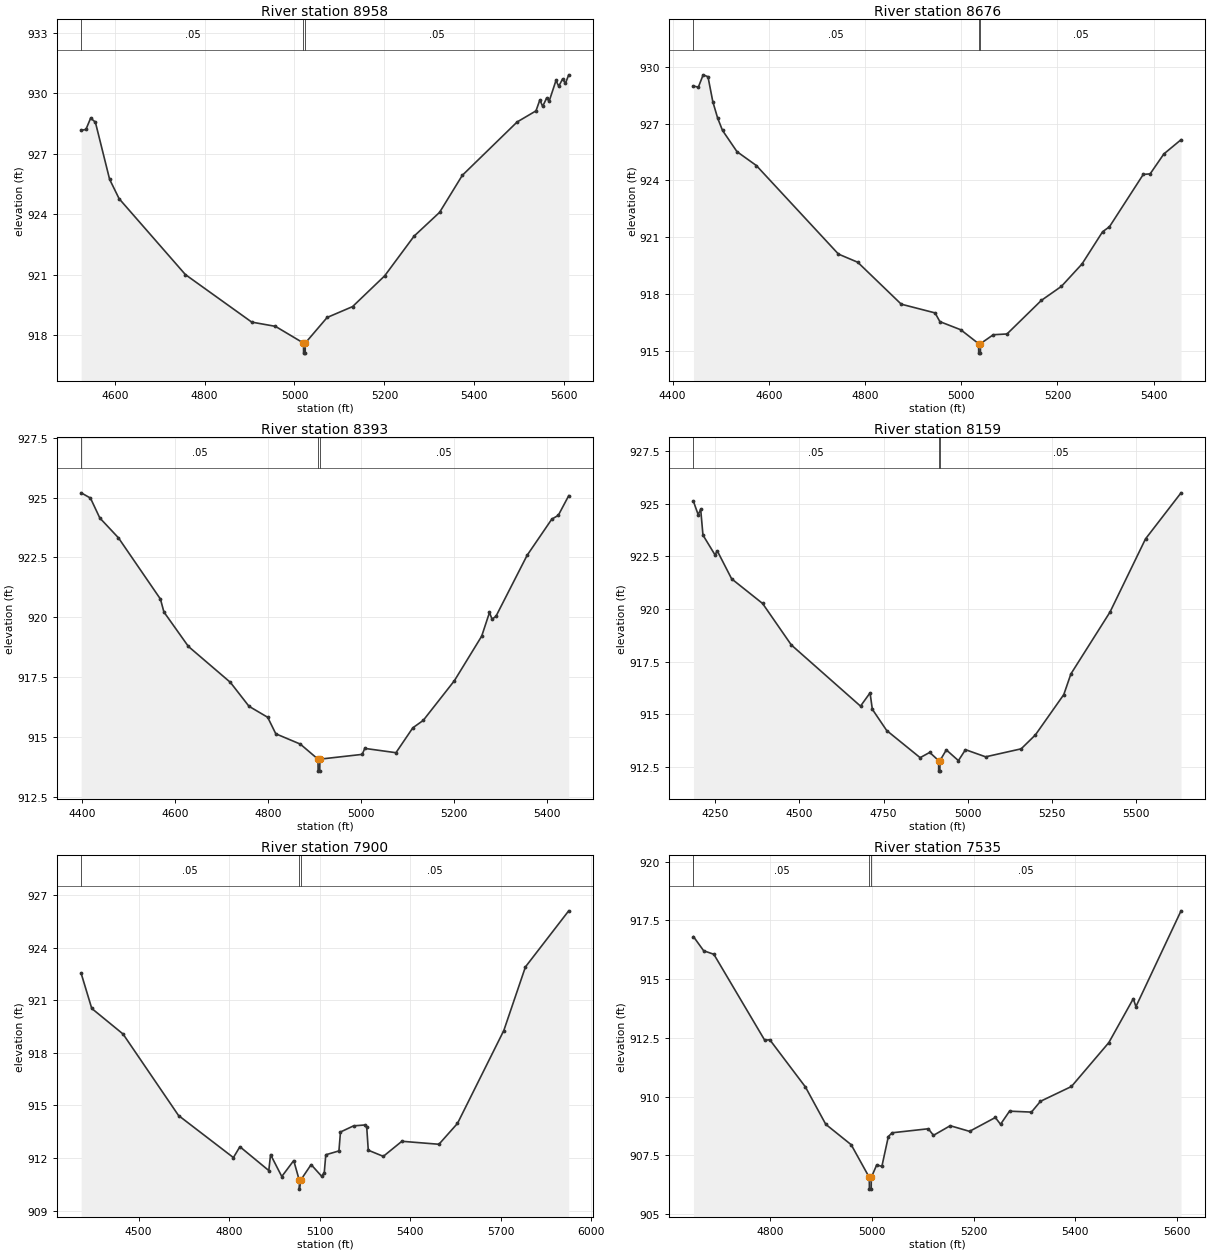
Type RM Length L Ch R = 1,8958,282,282,282
BEGIN DESCRIPTION:
S83 19.0
END DESCRIPTION:
XS GIS Cut Line= 3
      2285079.01      7076710.02      2284929.00      7076260.00
      2284579.00      7075760.00
#Sta/Elev= 30
  4525.4  928.16  4536.0  928.21  4546.5  928.77  4557.0  928.57  4588.7  925.73
  4609.8  924.77  4757.3  921.00  4904.9  918.64  4957.6  918.43  5020.0  917.60
  5020.3  917.10  5023.8  917.10  5024.0  917.60  5072.6  918.87  5129.2  919.41
  5200.7  920.94  5266.1  922.91  5322.8  924.09  5373.4  925.93  5495.4  928.58
  5537.3  929.13  5546.0  929.68  5552.1  929.35  5560.8  929.76  5566.9  929.63
  5581.8  930.64  5587.9  930.35  5596.6  930.72  5602.7  930.49  5610.1  930.92
#Mann=3,-1,0
  4525.4    0.05       0  5020.0    0.04       0  5024.0    0.05       0
Bank Sta=5020,5024
Exp/Cntr=0.3,0.1

Type RM Length L Ch R = 1,8676,283,283,283
BEGIN DESCRIPTION:
S83 18.0
END DESCRIPTION:
XS GIS Cut Line= 3
      2285229.00      7076710.02      2285179.00      7076160.00
      2284878.98      7075809.97
#Sta/Elev= 30
  4443.5  928.98  4453.6  928.92  4463.6  929.57  4473.6  929.47  4483.7  928.15
  4493.7  927.29  4503.8  926.64  4533.9  925.52  4574.1  924.79  4744.8  920.12
  4784.9  919.69  4875.3  917.48  4945.6  917.02  4955.6  916.56  4999.1  916.13
  5036.0  915.40  5036.3  914.90  5039.8  914.90  5040.0  915.40  5066.6  915.87
  5095.1  915.91  5166.5  917.68  5208.2  918.42  5251.0  919.60  5293.8  921.30
  5308.0  921.56  5378.3  924.32  5392.6  924.35  5421.1  925.40  5456.8  926.15
#Mann=3,-1,0
  4443.5    0.05       0  5036.0    0.04       0  5040.0    0.05       0
Bank Sta=5036,5040
Exp/Cntr=0.3,0.1

Type RM Length L Ch R = 1,8393,234,234,234
BEGIN DESCRIPTION:
S83 17.0
END DESCRIPTION:
XS GIS Cut Line= 3
      2285429.00      7076559.96      2285379.00      7075960.00
      2284978.96      7075759.98
#Sta/Elev= 30
  4397.7  925.20  4417.7  924.98  4437.8  924.15  4477.9  923.32  4568.3  920.76
  4575.8  920.22  4628.5  918.78  4718.8  917.28  4758.9  916.28  4799.1  915.82
  4816.6  915.13  4869.3  914.70  4907.4  914.07  4907.7  913.57  4911.2  913.57
  4911.4  914.07  5002.5  914.27  5008.1  914.52  5075.2  914.34  5111.5  915.38
  5133.9  915.69  5201.0  917.35  5259.7  919.21  5276.5  920.20  5282.0  919.92
  5290.4  920.04  5357.5  922.59  5410.6  924.10  5424.6  924.26  5447.0  925.08
#Mann=3,-1,0
  4397.7    0.05       0  4907.4    0.04       0  4911.4    0.05       0
Bank Sta=4907.4,4911.4
Exp/Cntr=0.3,0.1

Type RM Length L Ch R = 1,8159,259,259,259
BEGIN DESCRIPTION:
S83 16.0
END DESCRIPTION:
XS GIS Cut Line= 3
      2286129.00      7076460.01      2285579.00      7075860.00
      2284979.00      7075660.00
#Sta/Elev= 30
  4186.1  925.11  4200.0  924.48  4207.4  924.74  4214.2  923.51  4249.9  922.57
  4256.7  922.76  4299.3  921.43  4391.1  920.26  4476.2  918.29  4681.6  915.38
  4709.9  916.01  4716.7  915.23  4759.3  914.22  4858.5  912.93  4886.9  913.18
  4913.3  912.79  4913.5  912.29  4917.0  912.29  4917.3  912.79  4936.2  913.30
  4972.0  912.79  4993.0  913.31  5052.8  912.97  5158.2  913.35  5200.3  914.01
  5284.7  915.93  5305.7  916.91  5421.7  919.85  5527.1  923.33  5632.5  925.52
#Mann=3,-1,0
  4186.1    0.05       0  4913.3    0.04       0  4917.3    0.05       0
Bank Sta=4913.3,4917.3
Exp/Cntr=0.3,0.1

Type RM Length L Ch R = 1,7900,365,365,365
BEGIN DESCRIPTION:
S83 15.0
END DESCRIPTION:
XS GIS Cut Line= 3
      2286128.99      7076309.98      2285779.00      7075710.00
      2285979.01      7074809.95
#Sta/Elev= 30
  4309.3  922.53  4344.4  920.53  4448.2  919.07  4632.2  914.42  4814.1  912.02
  4835.6  912.64  4931.5  911.28  4937.3  912.19  4974.5  910.94  5014.1  911.85
  5032.6  910.72  5032.9  910.22  5036.6  910.72  5071.8  911.62  5106.3  910.96
  5115.3  911.15  5120.4  912.18  5164.0  912.40  5169.1  913.48  5212.6  913.83
  5249.8  913.88  5256.2  913.74  5261.3  912.44  5311.2  912.09  5372.7  912.95
  5495.6  912.78  5557.1  913.97  5710.7  919.27  5782.4  922.90  5925.9  926.10
#Mann=3,-1,0
  4309.3    0.05       0  5032.6   0.033       0  5036.6    0.05       0
Bank Sta=5032.6,5036.6
Exp/Cntr=0.3,0.1

Type RM Length L Ch R = 1,7535,367,367,367
BEGIN DESCRIPTION:
S83 14.0
END DESCRIPTION:
XS GIS Cut Line= 3
      2286129.00      7076010.01      2286129.00      7075660.00
      2286029.00      7075059.98
#Sta/Elev= 30
  4649.6  916.81  4669.6  916.21  4689.6  916.06  4789.6  912.40  4799.6  912.42
  4869.6  910.41  4909.6  908.82  4959.6  907.95  4995.1  906.56  4995.4  906.06
  4998.9  906.06  4999.1  906.56  5009.7  907.09  5019.9  907.03  5032.6  908.30
  5040.2  908.46  5111.1  908.63  5121.3  908.35  5154.2  908.76  5192.2  908.52
  5242.9  909.11  5253.1  908.82  5270.8  909.38  5313.9  909.34  5331.6  909.80
  5392.5  910.43  5466.0  912.30  5514.1  914.17  5519.2  913.83  5607.9  917.91
#Mann=3,-1,0
  4649.6    0.05       0  4995.1    0.04       0  4999.1    0.05       0
Bank Sta=4995.1,4999.1
Exp/Cntr=0.3,0.1

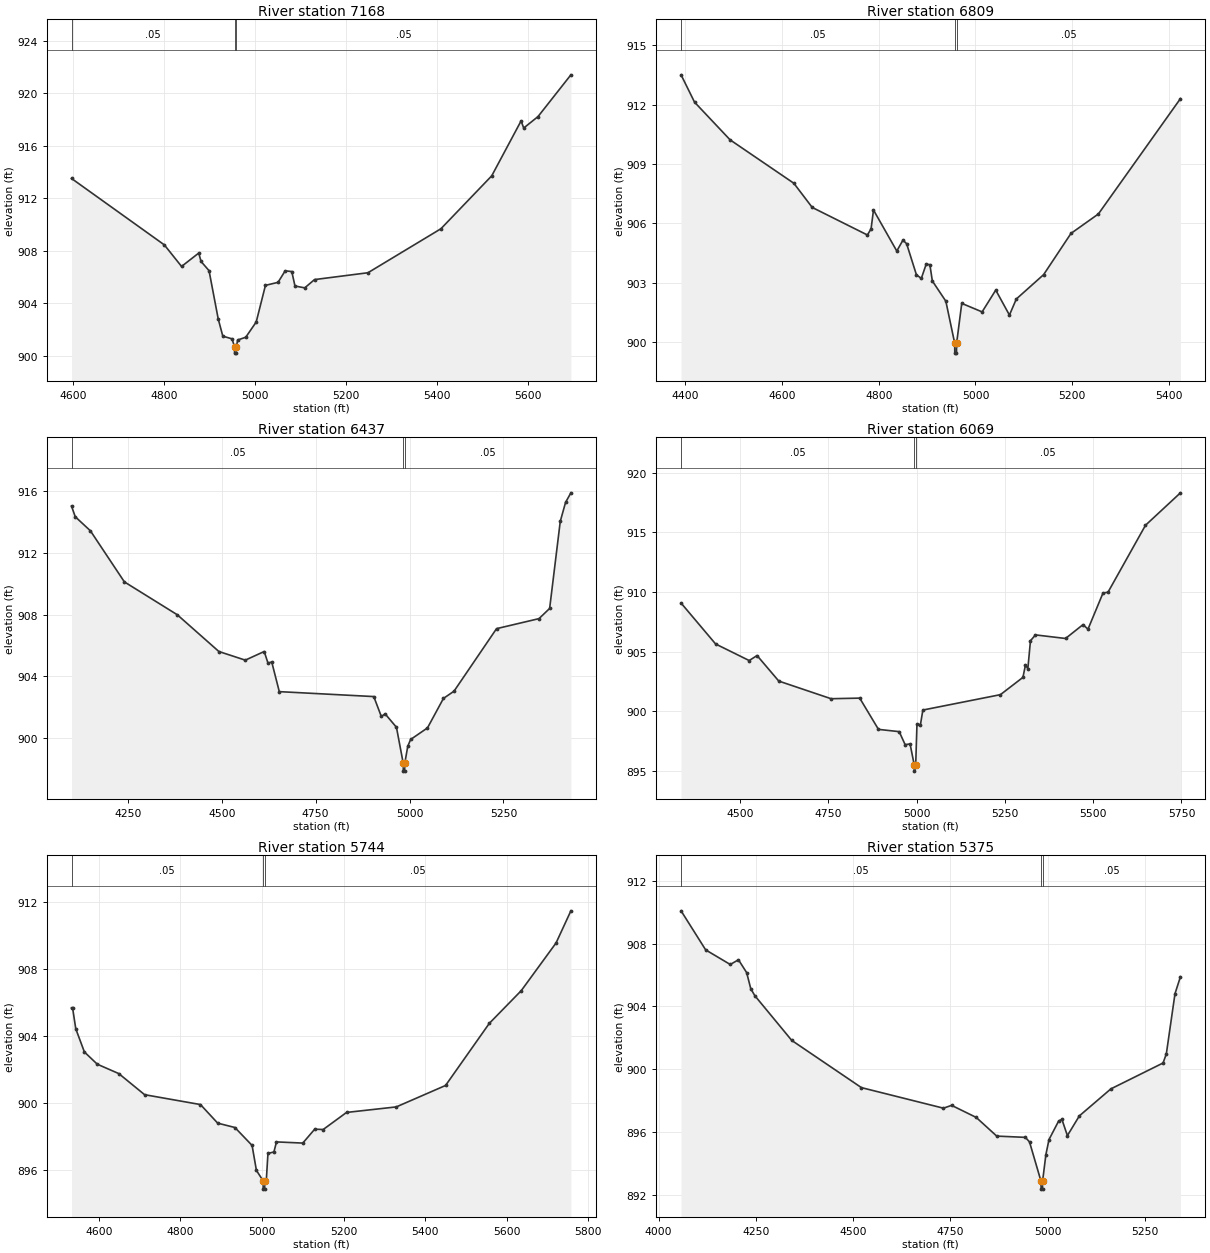
Type RM Length L Ch R = 1,7168,359,359,359
BEGIN DESCRIPTION:
S83 13.0
END DESCRIPTION:
XS GIS Cut Line= 3
      2286479.00      7075960.00      2286429.00      7075560.00
      2286079.02      7074960.03
#Sta/Elev= 30
  4596.6  913.51  4800.7  908.45  4838.5  906.81  4876.3  907.83  4881.3  907.19
  4898.9  906.49  4919.1  902.81  4929.2  901.50  4949.3  901.30  4954.9  900.71
  4955.1  900.21  4958.6  900.21  4958.9  900.71  4961.9  901.21  4979.6  901.42
  5002.6  902.58  5022.9  905.37  5050.6  905.60  5066.3  906.48  5080.8  906.42
  5087.8  905.32  5109.3  905.18  5130.8  905.81  5248.2  906.33  5408.6  909.68
  5520.3  913.71  5584.8  917.89  5590.6  917.35  5622.0  918.22  5694.3  921.40
#Mann=3,-1,0
  4596.6    0.05       0  4954.9    0.04       0  4958.9    0.05       0
Bank Sta=4954.9,4958.9
Exp/Cntr=0.3,0.1

Type RM Length L Ch R = 1,6809,372,372,372
BEGIN DESCRIPTION:
S83 12.0
END DESCRIPTION:
XS GIS Cut Line= 3
      2286729.01      7075960.03      2286629.00      7075360.00
      2286328.98      7075059.98
#Sta/Elev= 30
  4391.2  913.50  4419.1  912.12  4492.6  910.22  4624.4  908.03  4662.4  906.81
  4776.5  905.42  4784.1  905.73  4789.1  906.68  4837.3  904.61  4850.0  905.16
  4857.6  904.98  4877.9  903.41  4888.0  903.23  4898.1  903.95  4905.7  903.92
  4910.8  903.10  4938.7  902.08  4957.0  899.96  4957.2  899.46  4960.7  899.46
  4961.0  899.96  4971.6  901.97  5013.7  901.54  5041.9  902.64  5070.2  901.38
  5084.4  902.19  5140.9  903.42  5197.5  905.50  5254.1  906.48  5423.8  912.30
#Mann=3,-1,0
  4391.2    0.05       0  4957.0   0.033       0  4961.0    0.05       0
Bank Sta=4957,4961
Exp/Cntr=0.3,0.1

Type RM Length L Ch R = 1,6437,368,368,368
BEGIN DESCRIPTION:
S83 11.0
END DESCRIPTION:
XS GIS Cut Line= 3
      2286779.00      7076009.96      2286879.00      7075110.00
      2286578.97      7074809.97
#Sta/Elev= 30
  4099.8  915.03  4109.8  914.34  4150.1  913.43  4240.6  910.12  4381.5  907.99
  4492.2  905.61  4562.6  905.05  4612.9  905.61  4623.0  904.86  4633.0  904.93
  4653.1  903.01  4904.7  902.69  4924.8  901.40  4934.9  901.57  4965.1  900.70
  4983.2  898.36  4983.4  897.86  4986.9  897.86  4987.2  898.36  4995.2  899.47
  5002.8  899.91  5047.7  900.66  5090.2  902.57  5118.4  903.04  5231.6  907.09
  5344.7  907.74  5373.0  908.40  5401.3  914.04  5415.4  915.27  5429.6  915.89
#Mann=3,-1,0
  4099.8    0.05       0  4983.2   0.033       0  4987.2    0.05       0
Bank Sta=4983.2,4987.2
Exp/Cntr=0.3,0.1

Type RM Length L Ch R = 1,6069,325,325,325
BEGIN DESCRIPTION:
S83 10.0
END DESCRIPTION:
XS GIS Cut Line= 3
      2287479.00      7075710.00      2287179.00      7075110.00
      2286629.01      7074610.01
#Sta/Elev= 30
  4333.0  909.08  4430.8  905.65  4525.9  904.26  4548.2  904.68  4609.7  902.54
  4757.8  901.06  4838.9  901.11  4892.0  898.49  4950.7  898.30  4967.5  897.21
  4981.5  897.27  4993.4  895.49  4993.7  894.99  4997.4  895.49  5001.0  898.91
  5010.9  898.89  5017.7  900.11  5237.3  901.40  5301.1  902.85  5308.2  903.88
  5315.0  903.58  5322.4  905.92  5336.6  906.41  5421.8  906.11  5471.1  907.27
  5485.3  906.89  5527.8  909.92  5542.0  909.99  5648.1  915.60  5747.1  918.32
#Mann=3,-1,0
  4333.0    0.05       0  4993.4   0.033       0  4997.4    0.05       0
Bank Sta=4993.4,4997.4
Exp/Cntr=0.3,0.1

Type RM Length L Ch R = 1,5744,369,369,369
BEGIN DESCRIPTION:
S83 9.0
END DESCRIPTION:
XS GIS Cut Line= 3
      2287579.00      7075510.00      2287429.00      7075060.00
      2286829.03      7074610.02
#Sta/Elev= 30
  4533.1  905.70  4535.7  905.70  4543.6  904.44  4564.7  903.06  4596.3  902.33
  4649.0  901.77  4712.3  900.51  4849.3  899.92  4891.5  898.81  4933.7  898.55
  4975.8  897.48  4986.4  895.99  5002.8  895.37  5003.1  894.87  5006.6  894.87
  5006.8  895.37  5010.6  895.37  5014.7  897.00  5029.3  897.09  5035.6  897.69
  5100.1  897.62  5129.3  898.45  5150.1  898.43  5207.4  899.45  5329.3  899.78
  5450.1  901.06  5557.4  904.77  5635.6  906.72  5721.0  909.57  5757.4  911.49
#Mann=3,-1,0
  4533.1    0.05       0  5002.8   0.033       0  5006.8    0.05       0
Bank Sta=5002.8,5006.8
Exp/Cntr=0.3,0.1

Type RM Length L Ch R = 1,5375,377,377,377
BEGIN DESCRIPTION:
S83 8.0
END DESCRIPTION:
XS GIS Cut Line= 3
      2287879.00      7075660.01      2287579.00      7074760.00
      2287279.00      7074610.00
#Sta/Elev= 30
  4057.7  910.09  4121.0  907.60  4184.2  906.67  4205.3  906.97  4226.4  906.15
  4236.9  905.13  4247.4  904.68  4342.3  901.83  4521.5  898.82  4732.3  897.51
  4753.4  897.69  4816.7  896.92  4869.4  895.73  4943.1  895.65  4953.7  895.36
  4983.3  892.85  4983.6  892.35  4987.1  892.35  4987.3  892.85  4995.8  894.55
  5003.8  895.51  5028.8  896.70  5037.1  896.79  5051.1  895.76  5081.9  897.02
  5162.9  898.74  5297.1  900.39  5305.5  900.97  5327.8  904.81  5341.8  905.89
#Mann=3,-1,0
  4057.7    0.05       0  4983.3   0.033       0  4987.3    0.05       0
Bank Sta=4983.3,4987.3
Exp/Cntr=0.3,0.1

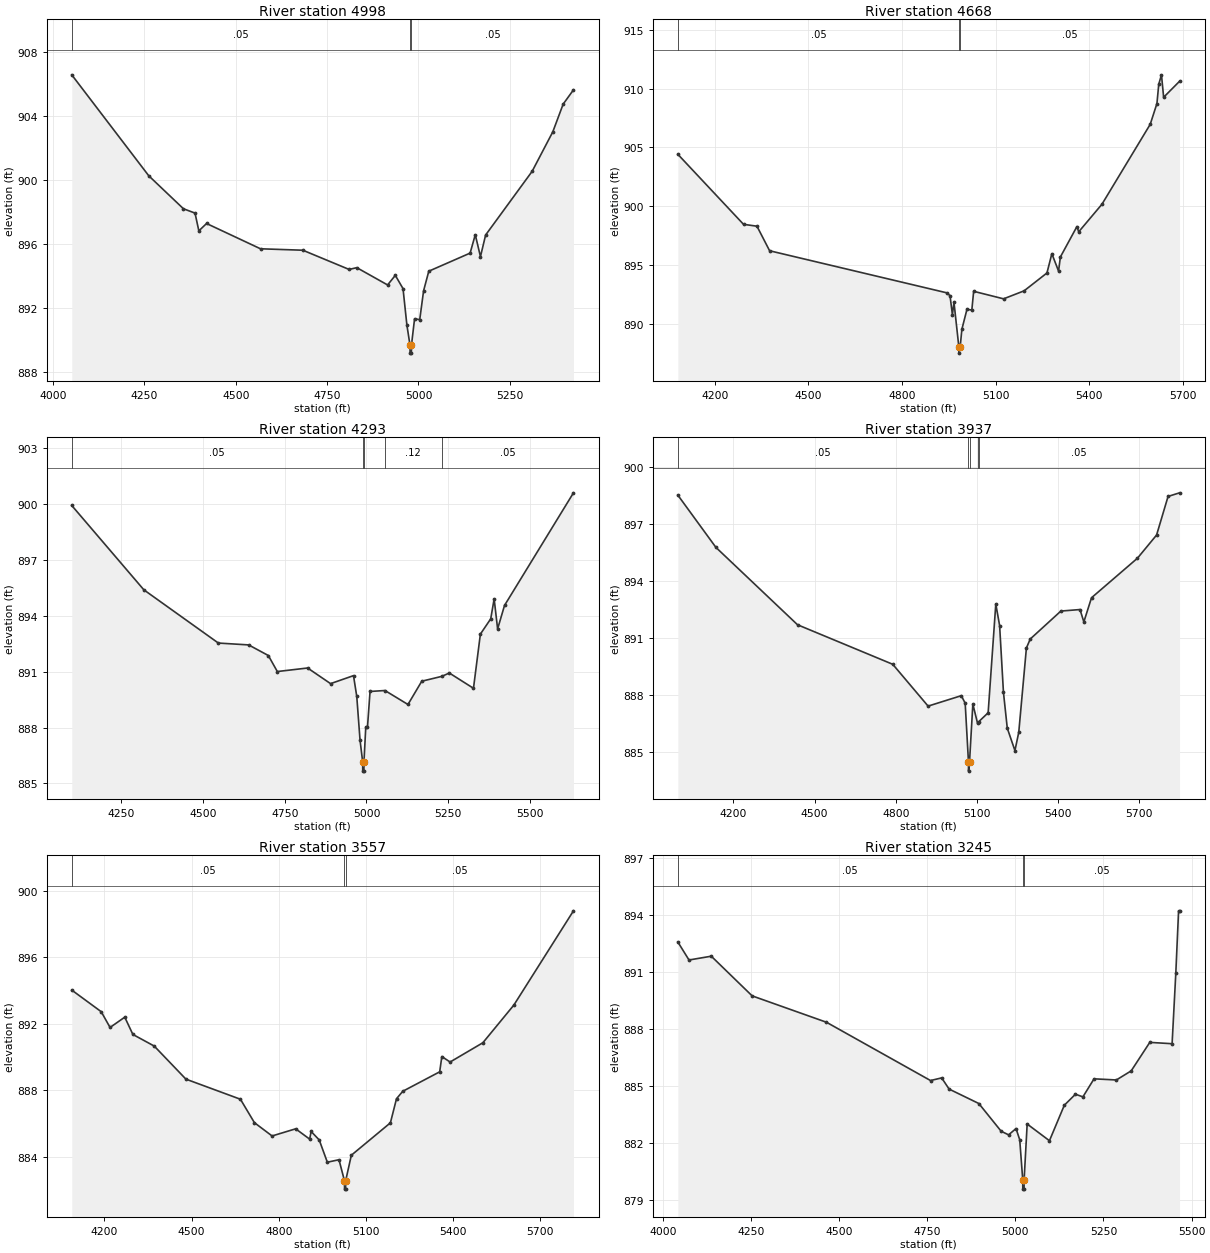
Type RM Length L Ch R = 1,4998,330,330,330
BEGIN DESCRIPTION:
S83 7.0
END DESCRIPTION:
XS GIS Cut Line= 3
      2288179.00      7075459.99      2287879.00      7074560.00
      2287579.03      7074260.03
#Sta/Elev= 30
  4051.3  906.60  4262.1  900.29  4357.0  898.23  4388.6  897.96  4399.1  896.85
  4420.2  897.31  4567.8  895.73  4683.7  895.64  4810.2  894.44  4831.3  894.55
  4915.6  893.47  4936.7  894.07  4957.8  893.24  4968.4  890.96  4976.9  889.71
  4977.1  889.21  4980.6  889.21  4980.9  889.71  4989.4  891.36  5003.5  891.30
  5014.1  893.11  5028.3  894.33  5141.4  895.46  5155.5  896.61  5169.7  895.24
  5183.8  896.59  5311.1  900.57  5367.7  903.04  5396.0  904.77  5424.2  905.66
#Mann=3,-1,0
  4051.3    0.05       0  4976.9   0.033       0  4980.9    0.05       0
Bank Sta=4976.9,4980.9
Exp/Cntr=0.3,0.1

Type RM Length L Ch R = 1,4668,375,375,375
BEGIN DESCRIPTION:
S83 6.0
END DESCRIPTION:
XS GIS Cut Line= 3
      2288329.00      7075360.02      2288179.00      7074460.00
      2287578.96      7074109.98
#Sta/Elev= 30
  4082.1  904.41  4292.5  898.45  4335.6  898.29  4376.1  896.20  4943.8  892.62
  4954.0  892.38  4961.6  890.77  4966.7  891.81  4982.4  887.99  4982.6  887.49
  4986.4  887.99  4992.0  889.52  5008.2  891.21  5023.9  891.16  5029.7  892.75
  5125.6  892.11  5191.3  892.79  5264.5  894.31  5280.2  895.95  5301.7  894.47
  5307.5  895.67  5360.5  898.26  5366.2  897.81  5440.7  900.16  5595.3  906.96
  5616.8  908.73  5622.6  910.36  5631.3  911.17  5638.3  909.26  5689.2  910.62
#Mann=3,-1,0
  4082.1    0.05       0  4982.4   0.033       0  4986.4    0.05       0
Bank Sta=4982.4,4986.4
Exp/Cntr=0.3,0.1

Type RM Length L Ch R = 1,4293,356,356,356
BEGIN DESCRIPTION:
S83 5.0
END DESCRIPTION:
XS GIS Cut Line= 3
      2288529.00      7075160.04      2288479.00      7074260.00
      2287878.98      7074059.99
#Sta/Elev= 30
  4098.9  899.93  4319.3  895.40  4547.1  892.54  4639.8  892.44  4699.9  891.87
  4727.4  891.01  4820.0  891.20  4890.2  890.36  4960.3  890.79  4970.3  889.67
  4980.3  887.32  4988.3  886.16  4988.6  885.66  4992.1  885.66  4992.3  886.16
  4997.8  888.02  5003.0  888.02  5010.9  889.94  5056.5  889.99  5126.8  889.24
  5169.0  890.49  5230.0  890.75  5253.3  890.93  5327.1  890.11  5348.2  893.02
  5379.8  893.84  5390.3  894.91  5400.9  893.30  5422.0  894.56  5632.8  900.61
#Mann=5,-1,0
  4098.9    0.05       0  4988.3   0.033       0  4992.3    0.05       0
  5056.5    0.12       0  5230.0    0.05       0
Bank Sta=4988.3,4992.3
Exp/Cntr=0.3,0.1

Type RM Length L Ch R = 1,3937,380,380,380
BEGIN DESCRIPTION:
S83 4.0
END DESCRIPTION:
XS GIS Cut Line= 3
      2288629.00      7075060.01      2288729.00      7074060.00
      2288129.02      7073460.02
#Sta/Elev= 30
  3995.0  898.51  4135.7  895.76  4437.2  891.69  4789.0  889.61  4919.6  887.41
  5042.4  887.96  5056.6  887.56  5068.7  884.49  5069.0  883.99  5072.7  884.49
  5084.9  887.52  5102.4  886.50  5106.6  886.59  5141.4  887.06  5169.7  892.78
  5183.8  891.65  5198.0  888.13  5212.1  886.25  5240.4  885.07  5254.6  886.04
  5282.8  890.47  5297.0  890.94  5410.1  892.41  5480.8  892.49  5495.0  891.84
  5523.3  893.11  5693.0  895.19  5763.7  896.41  5806.1  898.44  5848.5  898.63
#Mann=5,-1,0
  3995.0    0.05       0  5068.7   0.033       0  5072.7    0.05       0
  5102.4    0.12       0  5106.6    0.05       0
Bank Sta=5068.7,5072.7
Exp/Cntr=0.3,0.1

Type RM Length L Ch R = 1,3557,312,312,312
BEGIN DESCRIPTION:
S83 3.0
END DESCRIPTION:
XS GIS Cut Line= 3
      2288879.01      7074759.96      2289029.00      7073860.00
      2288429.01      7073310.01
#Sta/Elev= 30
  4087.6  894.03  4188.9  892.73  4219.4  891.78  4270.0  892.40  4297.9  891.36
  4371.4  890.66  4480.4  888.67  4668.0  887.46  4716.1  886.05  4776.9  885.25
  4858.0  885.68  4906.2  885.06  4911.3  885.52  4939.1  885.01  4967.0  883.67
  5007.1  883.82  5026.0  882.55  5026.3  882.05  5029.8  882.05  5030.0  882.55
  5049.6  884.09  5184.0  886.04  5205.0  887.49  5226.6  887.94  5353.6  889.11
  5361.0  890.03  5389.4  889.70  5502.2  890.86  5608.9  893.13  5813.9  898.80
#Mann=3,-1,0
  4087.6    0.05       0  5026.0   0.033       0  5030.0    0.05       0
Bank Sta=5026,5030
Exp/Cntr=0.3,0.1

Type RM Length L Ch R = 1,3245,497,497,497
BEGIN DESCRIPTION:
S83 2.0
END DESCRIPTION:
XS GIS Cut Line= 3
      2288978.99      7074660.03      2289279.00      7073760.00
      2289128.99      7073309.96
#Sta/Elev= 30
  4042.6  892.60  4074.3  891.65  4137.5  891.85  4253.4  889.76  4464.3  888.37
  4759.4  885.30  4791.0  885.44  4812.1  884.85  4896.4  884.09  4959.7  882.63
  4980.8  882.44  5001.9  882.77  5012.4  882.18  5020.9  880.08  5021.2  879.58
  5024.7  879.58  5024.9  880.08  5033.5  883.01  5096.7  882.13  5138.9  884.00
  5170.5  884.58  5191.6  884.44  5223.2  885.39  5286.5  885.33  5328.6  885.81
  5381.3  887.31  5444.6  887.24  5455.1  890.95  5463.0  894.24  5465.7  894.24
#Mann=3,-1,0
  4042.6    0.05       0  5020.9   0.033       0  5024.9    0.05       0
Bank Sta=5020.9,5024.9
Exp/Cntr=0.3,0.1

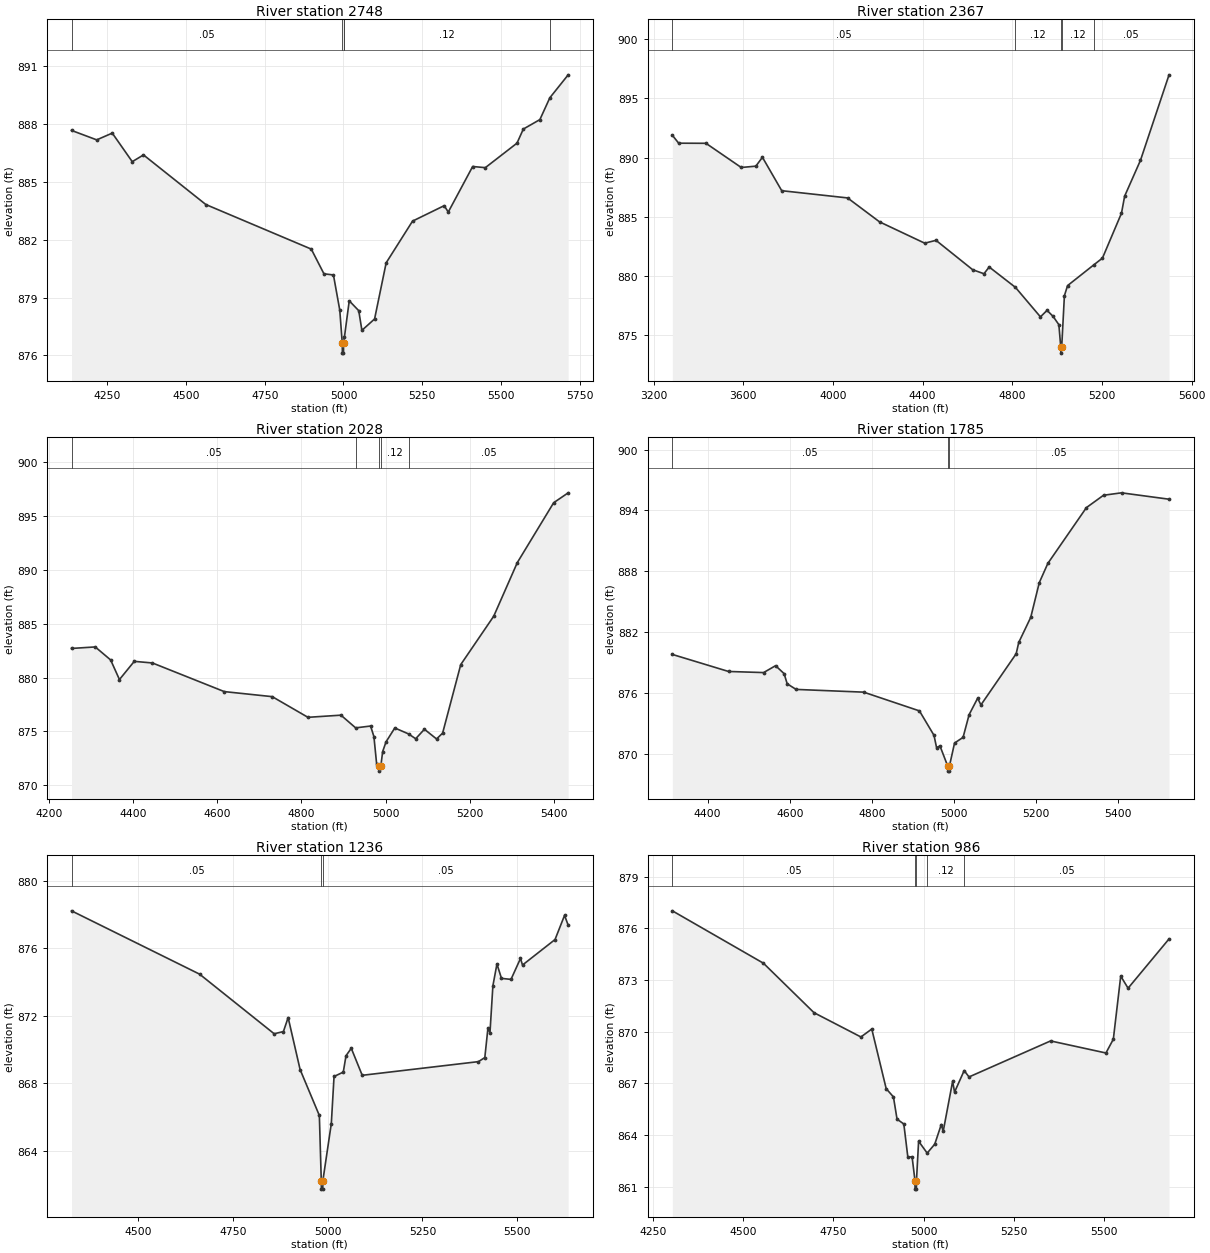
Type RM Length L Ch R = 1,2748,381,381,381
BEGIN DESCRIPTION:
1096
END DESCRIPTION:
XS GIS Cut Line= 3
      2289237.94      7074322.00      2289725.01      7073790.65
      2289813.57      7072938.25
#Sta/Elev= 30
  4136.1  887.66  4216.2  887.17  4265.6  887.52  4329.1  886.04  4364.8  886.39
  4562.8  883.82  4897.8  881.51  4938.0  880.23  4968.2  880.17  4988.3  878.35
  4996.3  876.62  4996.6  876.12  5000.1  876.12  5000.4  876.62  5003.1  876.95
  5018.4  878.83  5048.6  878.32  5058.6  877.30  5098.9  877.89  5135.7  880.80
  5219.5  882.96  5320.0  883.76  5333.0  883.43  5410.5  885.79  5450.7  885.73
  5551.3  887.00  5571.4  887.73  5624.0  888.22  5655.6  889.35  5713.9  890.54
#Mann=5,-1,0
  4136.1    0.05       0  4996.3   0.033       0  5000.4    0.05       0
  5003.1    0.12       0  5655.6    0.05       0
Bank Sta=4996.3,5000.4
Exp/Cntr=0.3,0.1

Type RM Length L Ch R = 1,2367,339,339,339
BEGIN DESCRIPTION:
S83 1.0
END DESCRIPTION:
XS GIS Cut Line= 3
      2289029.02      7074909.98      2290029.00      7073510.00
      2290378.99      7073160.01
#Sta/Elev= 30
  3283.7  891.89  3311.9  891.22  3433.6  891.21  3590.9  889.17  3656.0  889.28
  3685.5  890.03  3771.5  887.21  4065.3  886.60  4207.8  884.58  4409.3  882.78
  4459.7  883.02  4623.2  880.54  4673.6  880.20  4696.9  880.77  4814.0  879.05
  4925.5  876.56  4955.0  877.11  4982.0  876.60  5007.7  875.90  5016.2  874.00
  5016.5  873.50  5020.3  874.00  5032.4  878.35  5046.6  879.20  5162.2  880.93
  5202.1  881.52  5287.0  885.31  5301.1  886.75  5371.8  889.78  5499.1  896.99
#Mann=5,-1,0
  3283.7    0.05       0  4814.0    0.12       0  5016.2    0.07       0
  5020.3    0.12       0  5162.2    0.05       0
Bank Sta=5016.2,5020.3
Exp/Cntr=0.3,0.1

Type RM Length L Ch R = 1,2028,243,243,243
BEGIN DESCRIPTION:
1095
END DESCRIPTION:
XS GIS Cut Line= 2
      2289791.43      7074222.37      2290532.54      7073304.27
#Sta/Elev= 30
  4253.8  882.71  4310.2  882.85  4346.8  881.64  4367.7  879.82  4402.9  881.51
  4446.1  881.36  4616.7  878.70  4730.7  878.23  4815.5  876.31  4893.9  876.51
  4928.8  875.33  4964.3  875.50  4972.2  874.52  4978.6  872.01  4984.5  871.81
  4984.8  871.31  4988.7  871.81  4993.0  873.13  5001.0  874.03  5021.8  875.32
  5054.4  874.77  5071.4  874.32  5092.2  875.20  5121.0  874.30  5135.4  874.84
  5178.5  881.21  5256.9  885.71  5312.9  890.69  5399.2  896.25  5433.7  897.17
#Mann=5,-1,0
  4253.8    0.05       0  4928.8    0.12       0  4984.5    0.07       0
  4988.7    0.12       0  5054.4    0.05       0
Bank Sta=4984.5,4988.7
Exp/Cntr=0.3,0.1

Type RM Length L Ch R = 1,1785,549,549,549
BEGIN DESCRIPTION:
1093
END DESCRIPTION:
XS GIS Cut Line= 2
      2290012.80      7074355.24      2290732.35      7073381.07
#Sta/Elev= 30
  4313.9  879.79  4450.8  878.11  4536.4  878.00  4565.6  878.68  4586.5  877.89
  4593.9  876.89  4615.7  876.34  4780.4  876.07  4916.4  874.22  4951.9  871.81
  4958.1  870.61  4966.5  870.76  4985.3  868.78  4985.6  868.28  4989.1  868.28
  4989.5  868.78  5002.0  871.05  5022.8  871.61  5037.5  873.85  5058.3  875.47
  5066.3  874.81  5152.3  879.86  5158.5  880.97  5187.8  883.45  5208.6  886.87
  5229.5  888.77  5323.5  894.27  5365.2  895.49  5409.1  895.73  5525.0  895.10
#Mann=3,-1,0
  4313.9    0.05       0  4985.3   0.033       0  4989.5    0.05       0
Bank Sta=4985.3,4989.5
Exp/Cntr=0.3,0.1

Type RM Length L Ch R = 1,1236,250,250,250
BEGIN DESCRIPTION:
1092
END DESCRIPTION:
XS GIS Cut Line= 3
      2290068.18      7074454.82      2290798.76      7074211.29
      2290986.40      7073703.56
#Sta/Elev= 30
  4323.5  878.21  4661.7  874.46  4858.6  870.93  4883.0  871.06  4895.5  871.89
  4927.1  868.81  4977.9  866.09  4983.0  862.23  4983.3  861.73  4986.9  861.73
  4987.2  862.23  5009.5  865.61  5016.7  868.40  5041.1  868.66  5048.3  869.63
  5062.2  870.07  5091.1  868.47  5398.0  869.28  5414.8  869.52  5423.1  871.28
  5428.4  870.99  5436.1  873.77  5446.8  875.06  5458.8  874.21  5483.9  874.15
  5509.0  875.39  5514.3  875.00  5600.2  876.51  5625.3  877.94  5634.9  877.36
#Mann=3,-1,0
  4323.5    0.05       0  4983.0   0.033       0  4987.2    0.05       0
Bank Sta=4983,4987.2
Exp/Cntr=0.3,0.1

Type RM Length L Ch R = 1,986,261,261,261
BEGIN DESCRIPTION:
4545
END DESCRIPTION:
XS GIS Cut Line= 4
      2290196.87      7074482.44      2290855.85      7074444.18
      2290919.62      7074254.98      2291030.16      7073749.06
#Sta/Elev= 30
  4303.4  877.02  4556.0  873.98  4696.2  871.11  4826.4  869.70  4856.5  870.16
  4896.5  866.70  4916.6  866.22  4926.6  864.93  4945.4  864.65  4956.6  862.72
  4968.3  862.75  4976.3  861.37  4976.6  860.87  4980.2  860.87  4980.5  861.37
  4986.4  863.65  5010.2  862.96  5031.2  863.48  5049.3  864.62  5054.6  864.22
  5080.8  867.13  5086.1  866.50  5112.8  867.75  5126.2  867.38  5352.5  869.47
  5506.0  868.77  5526.5  869.57  5547.0  873.23  5567.4  872.53  5681.0  875.39
#Mann=5,-1,0
  4303.4    0.05       0  4976.3   0.033       0  4980.5    0.05       0
  5010.2    0.12       0  5112.8    0.05       0
Bank Sta=4976.3,4980.5
Exp/Cntr=0.3,0.1

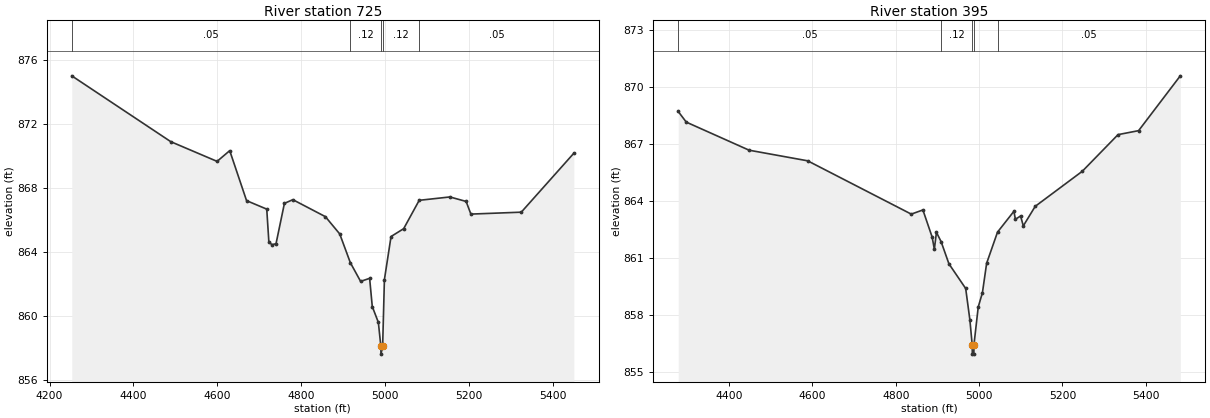
Type RM Length L Ch R = 1,725,330,330,330
BEGIN DESCRIPTION:
45458
END DESCRIPTION:
XS GIS Cut Line= 4
      2290373.67      7074488.61      2291005.26      7074443.08
      2291075.31      7074354.35      2291095.15      7073904.97
#Sta/Elev= 30
  4253.0  875.00  4488.9  870.89  4599.2  869.66  4629.3  870.33  4669.4  867.21
  4717.5  866.68  4722.5  864.65  4729.6  864.46  4739.6  864.52  4759.6  867.04
  4779.7  867.27  4857.2  866.21  4891.4  865.13  4916.6  863.34  4941.1  862.17
  4962.6  862.36  4968.9  860.60  4983.4  859.61  4989.3  858.13  4989.6  857.63
  4993.6  858.13  4997.8  862.28  5013.6  864.97  5043.7  865.46  5080.7  867.23
  5153.8  867.44  5192.5  867.16  5203.8  866.37  5323.9  866.49  5449.1  870.17
#Mann=5,-1,0
  4253.0    0.05       0  4916.6    0.12       0  4989.3    0.07       0
  4993.6    0.12       0  5080.7    0.05       0
Bank Sta=4989.3,4993.6
Exp/Cntr=0.3,0.1

Type RM Length L Ch R = 1,395,0,0,0
BEGIN DESCRIPTION:
1091
END DESCRIPTION:
XS GIS Cut Line= 5
      2290799.77      7074490.95      2291274.76      7074443.76
      2291385.45      7074388.41      2291363.31      7074178.09
      2291108.70      7073879.20
#Sta/Elev= 30
  4277.9  868.71  4297.2  868.15  4448.0  866.67  4588.6  866.11  4837.3  863.30
  4865.2  863.52  4887.4  862.09  4892.7  861.45  4897.7  862.34  4908.9  861.85
  4927.7  860.68  4967.9  859.38  4977.9  857.74  4983.5  856.42  4983.9  855.92
  4987.5  855.92  4987.8  856.42  4998.0  858.40  5008.1  859.16  5018.2  860.71
  5044.3  862.35  5083.7  863.45  5087.2  863.03  5099.7  863.20  5106.2  862.68
  5134.8  863.71  5247.9  865.56  5333.6  867.49  5383.0  867.70  5483.1  870.59
#Mann=5,-1,0
  4277.9    0.05       0  4908.9    0.12       0  4983.5    0.07       0
  4987.8    0.12       0  5044.3    0.05       0
Bank Sta=4983.5,4987.8
Exp/Cntr=0.3,0.1

Chan Stop Cuts=-1