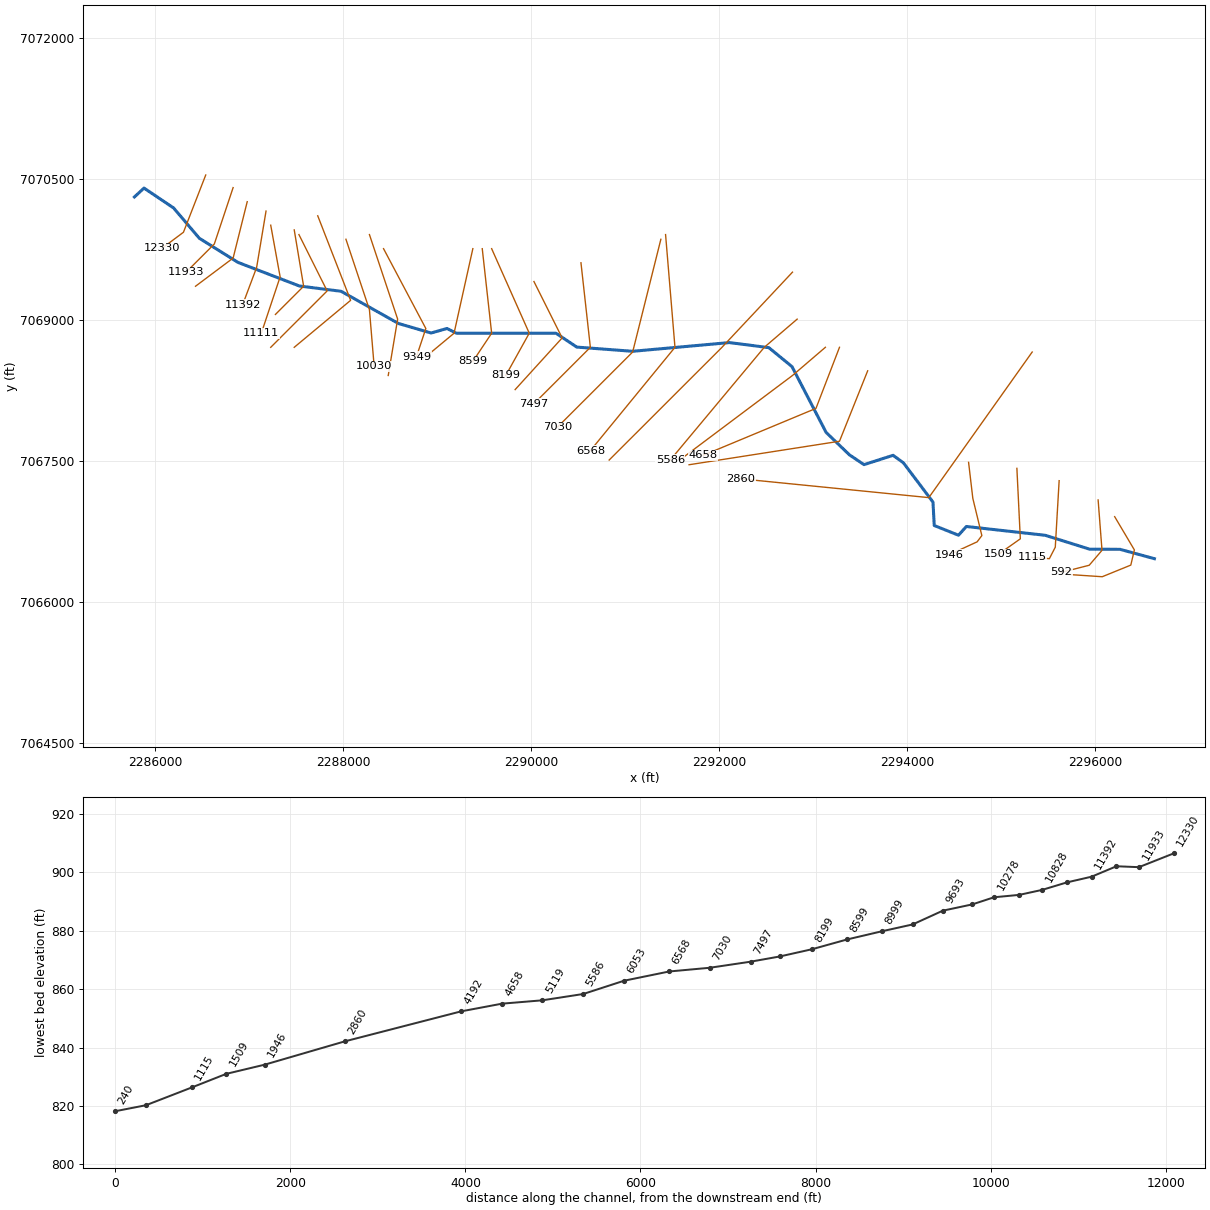
--- S84.prj (project) ---

Proj Title=S84 Base Level Engineering
Current Plan=p01
Default Exp/Contr=0.3,0.1
English Units
Geom File=g01
Flow File=f01
Plan File=p01
BEGIN DESCRIPTION:
S84
END DESCRIPTION:

--- S84.p01 (plan) ---

Plan Title=Multiple Run
Short Identifier=Multiple
Geom File=g01
Flow File=f01
Subcritical Flow
K Sum by GR= 0
Std Step Tol= 0.01
Critical Tol= 0.01
Num of Std Step Trials= 20
Max Error Tol= 0.3
Flow Tol Ratio= 0.001
Split Flow NTrial= 30
Split Flow Tol= 0.02
Split Flow Ratio= 0.02
Log Output Level= 0
Friction Slope Method= 1
Unsteady Friction Slope Method= 2
Unsteady Bridges Friction Slope Method= 1
Parabolic Critical Depth
Global Vel Dist=  1 , 1 , 1
Global Log Level= 0
CheckData=True
Encroach Param= -1, 0, 0, 0
BEGIN DESCRIPTION:
Multiple Run
END DESCRIPTION:

--- S84.f01 (steady flow) ---

Flow Title=Multiple
Number of Profiles=7
Profile Names=10-year,25-year,50-year,1pct_min,100-year,1pct_plu,500-year
River Rch & RM= S84,Reach-1,12330
     392     524     630     377     753    1500    1070
River Rch & RM= S84,Reach-1,9693
     624     858    1050     640    1280    2550    1890
River Rch & RM= S84,Reach-1,6053
     793    1100    1360     836    1670    3330    2500
Boundary for River Rch & Prof#=S84,Reach-1,1
Up Type=0
Dn Type=3
Dn Slope=0.005
Boundary for River Rch & Prof#=S84,Reach-1,2
Up Type=0
Dn Type=3
Dn Slope=0.005
Boundary for River Rch & Prof#=S84,Reach-1,3
Up Type=0
Dn Type=3
Dn Slope=0.005
Boundary for River Rch & Prof#=S84,Reach-1,4
Up Type=0
Dn Type=3
Dn Slope=0.005
Boundary for River Rch & Prof#=S84,Reach-1,5
Up Type=0
Dn Type=3
Dn Slope=0.005
Boundary for River Rch & Prof#=S84,Reach-1,6
Up Type=0
Dn Type=3
Dn Slope=0.005
Boundary for River Rch & Prof#=S84,Reach-1,7
Up Type=0
Dn Type=3
Dn Slope=0.005

--- S84.g01 (geometry) ---

Geom Title=Existing Conditions

River Reach=S84,Reach-1
Reach XY= 30
      2285779.00      7070310.00      2285880.96      7070405.07
      2286195.68      7070193.36      2286469.30      7069870.76
      2286880.58      7069613.83      2287534.94      7069362.26
      2287977.53      7069306.44      2288587.50      7068963.55
      2288934.98      7068862.17      2289104.00      7068910.40
      2289203.91      7068859.81      2290263.84      7068859.61
      2290484.93      7068712.24      2291079.00      7068667.56
      2292108.85      7068760.36      2292527.50      7068706.39
      2292773.74      7068504.53      2293137.02      7067803.66
      2293384.62      7067565.62      2293539.44      7067461.04
      2293849.21      7067560.37      2293959.23      7067480.14
      2294273.54      7067062.45      2294286.95      7066813.00
      2294544.76      7066709.88      2294628.70      7066802.74
      2295468.50      7066708.78      2295939.50      7066561.22
      2296263.78      7066559.48      2296629.00      7066460.00

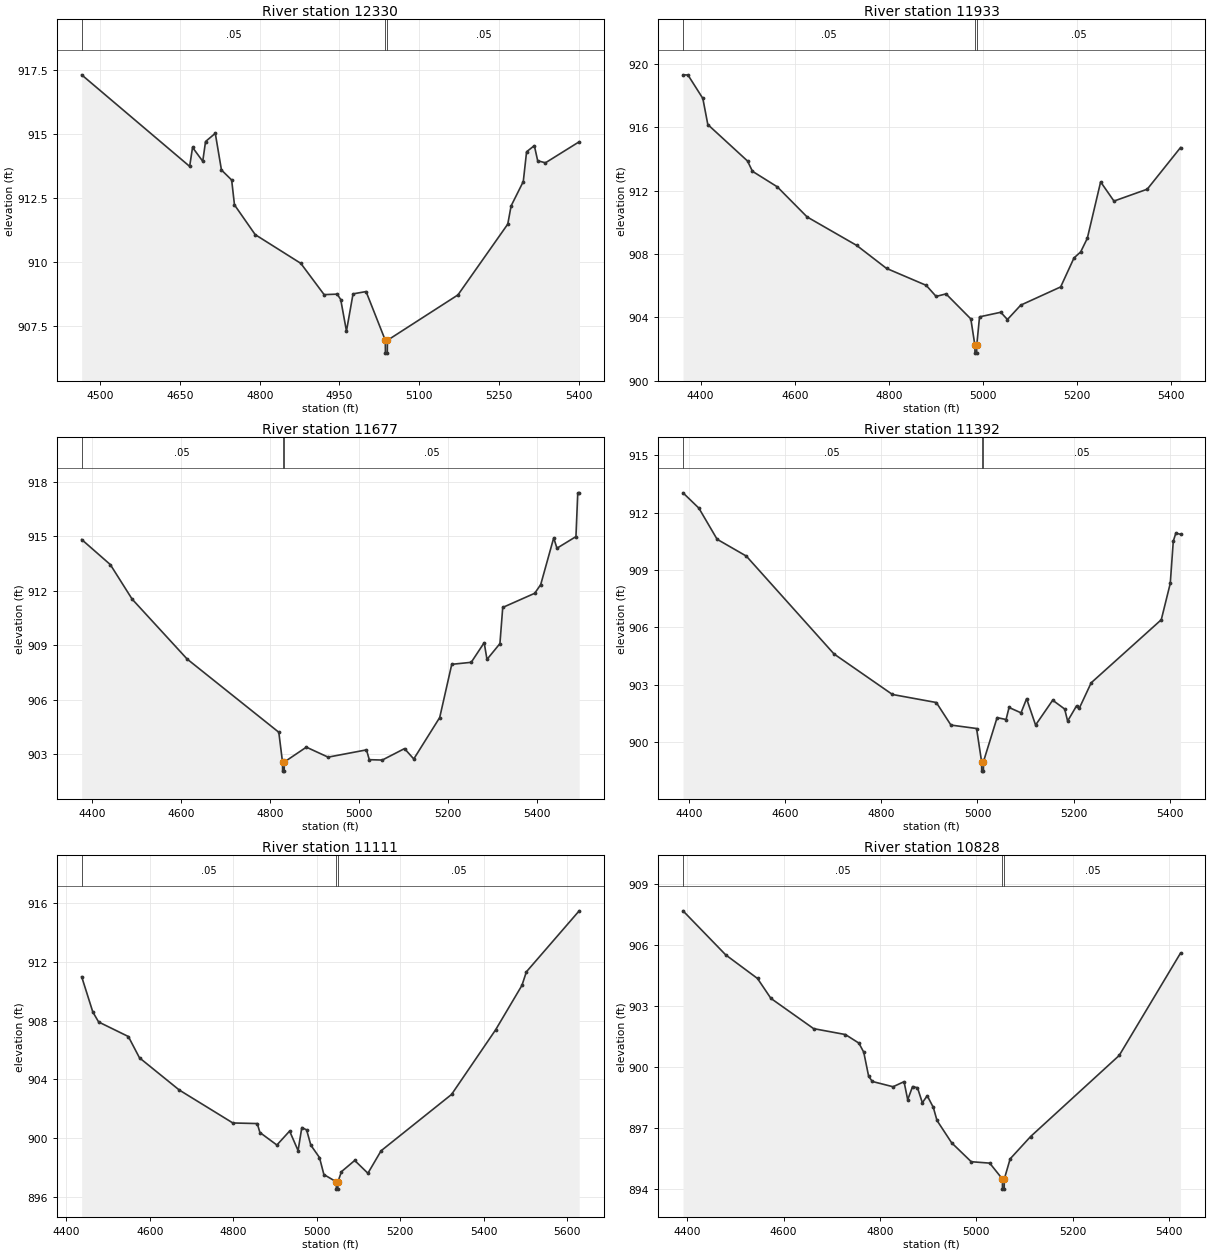
Type RM Length L Ch R = 1,12330,397,397,397
BEGIN DESCRIPTION:
1081
END DESCRIPTION:
XS GIS Cut Line= 3
      2286537.71      7070544.30      2286300.70      7069934.84
      2286074.96      7069765.53
#Sta/Elev= 30
  4465.0  917.31  4668.2  913.74  4673.6  914.48  4692.8  913.94  4698.1  914.71
  4716.4  915.03  4728.0  913.60  4747.2  913.21  4752.5  912.24  4791.5  911.08
  4877.3  909.96  4921.2  908.74  4945.7  908.76  4952.4  908.55  4963.2  907.32
  4975.6  908.77  5000.1  908.86  5036.3  906.96  5036.5  906.46  5040.0  906.46
  5040.3  906.96  5173.0  908.73  5266.7  911.49  5273.0  912.20  5295.9  913.15
  5302.1  914.31  5316.7  914.55  5323.0  913.96  5337.6  913.88  5401.1  914.70
#Mann=3,-1,0
  4465.0    0.05       0  5036.3   0.033       0  5040.3    0.05       0
Bank Sta=5036.3,5040.3
Exp/Cntr=0.3,0.1

Type RM Length L Ch R = 1,11933,256,256,256
BEGIN DESCRIPTION:
S84 23.0
END DESCRIPTION:
XS GIS Cut Line= 3
      2286828.99      7070409.97      2286629.00      7069810.00
      2286328.99      7069509.99
#Sta/Elev= 30
  4362.8  919.32  4373.3  919.31  4404.9  917.83  4415.5  916.18  4499.8  913.88
  4510.3  913.23  4563.0  912.25  4626.3  910.35  4731.7  908.55  4795.0  907.10
  4879.3  906.03  4900.4  905.33  4921.4  905.49  4974.1  903.91  4982.7  902.25
  4982.9  901.75  4986.4  901.75  4986.7  902.25  4992.6  904.04  5037.7  904.33
  5051.8  903.87  5080.1  904.78  5164.9  905.93  5193.2  907.76  5207.4  908.14
  5221.5  909.00  5249.8  912.56  5278.1  911.35  5348.8  912.10  5419.5  914.73
#Mann=3,-1,0
  4362.8    0.05       0  4982.7   0.033       0  4986.7    0.05       0
Bank Sta=4982.7,4986.7
Exp/Cntr=0.3,0.1

Type RM Length L Ch R = 1,11677,285,285,285
BEGIN DESCRIPTION:
S84 22.0
END DESCRIPTION:
XS GIS Cut Line= 3
      2286979.00      7070260.01      2286829.00      7069660.00
      2286428.98      7069359.98
#Sta/Elev= 30
  4376.0  914.81  4440.4  913.43  4489.4  911.53  4613.1  908.23  4819.2  904.20
  4827.5  902.56  4827.8  902.06  4831.3  902.06  4831.5  902.56  4881.1  903.38
  4930.0  902.83  5016.3  903.23  5022.6  902.69  5051.8  902.67  5101.8  903.30
  5122.6  902.73  5180.9  905.01  5208.0  907.94  5251.8  908.05  5280.9  909.13
  5287.2  908.21  5316.3  909.08  5322.6  911.07  5394.5  911.85  5408.0  912.33
  5437.2  914.90  5444.5  914.33  5487.2  914.97  5491.3  917.38  5494.5  917.38
#Mann=3,-1,0
  4376.0    0.05       0  4827.5   0.033       0  4831.5    0.05       0
Bank Sta=4827.5,4831.5
Exp/Cntr=0.3,0.1

Type RM Length L Ch R = 1,11392,281,281,281
BEGIN DESCRIPTION:
S84 21.0
END DESCRIPTION:
XS GIS Cut Line= 3
      2287179.00      7070160.01      2287079.00      7069560.00
      2286929.00      7069159.99
#Sta/Elev= 30
  4387.2  913.04  4420.2  912.24  4458.2  910.61  4519.0  909.73  4701.5  904.61
  4823.1  902.49  4914.4  902.07  4944.8  900.89  4998.2  900.71  5008.6  898.98
  5008.9  898.48  5012.4  898.48  5012.6  898.98  5040.9  901.28  5059.6  901.18
  5065.8  901.81  5090.7  901.53  5102.3  902.27  5121.0  900.89  5156.6  902.19
  5181.5  901.73  5187.7  901.10  5206.4  901.90  5211.8  901.76  5236.7  903.10
  5382.6  906.40  5401.3  908.30  5407.6  910.51  5412.9  910.93  5422.7  910.87
#Mann=3,-1,0
  4387.2    0.05       0  5008.6    0.05       0  5012.6    0.05       0
Bank Sta=5008.6,5012.6
Exp/Cntr=0.3,0.1

Type RM Length L Ch R = 1,11111,283,283,283
BEGIN DESCRIPTION:
S84 20.0
END DESCRIPTION:
XS GIS Cut Line= 3
      2287229.00      7070009.98      2287329.00      7069460.00
      2287128.98      7068859.95
#Sta/Elev= 30
  4436.8  910.99  4463.5  908.59  4477.4  907.91  4548.6  906.92  4575.3  905.47
  4670.6  903.28  4798.9  901.04  4857.3  901.00  4863.7  900.39  4904.3  899.54
  4934.8  900.49  4955.1  899.16  4964.0  900.73  4975.5  900.57  4985.6  899.53
  5006.3  898.69  5016.9  897.53  5046.5  897.04  5046.8  896.54  5050.3  896.54
  5050.5  897.04  5059.0  897.73  5090.7  898.49  5122.3  897.62  5153.9  899.15
  5322.6  902.98  5428.0  907.37  5491.2  910.40  5501.8  911.32  5628.3  915.47
#Mann=3,-1,0
  4436.8    0.05       0  5046.5    0.05       0  5050.5    0.05       0
Bank Sta=5046.5,5050.5
Exp/Cntr=0.3,0.1

Type RM Length L Ch R = 1,10828,262,262,262
BEGIN DESCRIPTION:
S84 19.0
END DESCRIPTION:
XS GIS Cut Line= 3
      2287479.01      7069959.95      2287579.00      7069360.00
      2287278.99      7069059.99
#Sta/Elev= 30
  4391.2  907.67  4479.9  905.50  4545.8  904.34  4573.6  903.36  4662.3  901.87
  4728.2  901.58  4756.1  901.16  4766.3  900.71  4776.4  899.53  4784.0  899.27
  4827.1  899.01  4849.9  899.26  4857.5  898.37  4867.6  899.02  4877.8  898.96
  4887.9  898.22  4898.0  898.57  4910.7  897.99  4918.3  897.35  4948.7  896.25
  4989.3  895.32  5027.7  895.25  5054.0  894.47  5054.2  893.97  5057.7  893.97
  5058.0  894.47  5070.1  895.46  5112.6  896.56  5296.4  900.55  5423.7  905.59
#Mann=3,-1,0
  4391.2    0.05       0  5054.0   0.035       0  5058.0    0.05       0
Bank Sta=5054,5058
Exp/Cntr=0.3,0.1

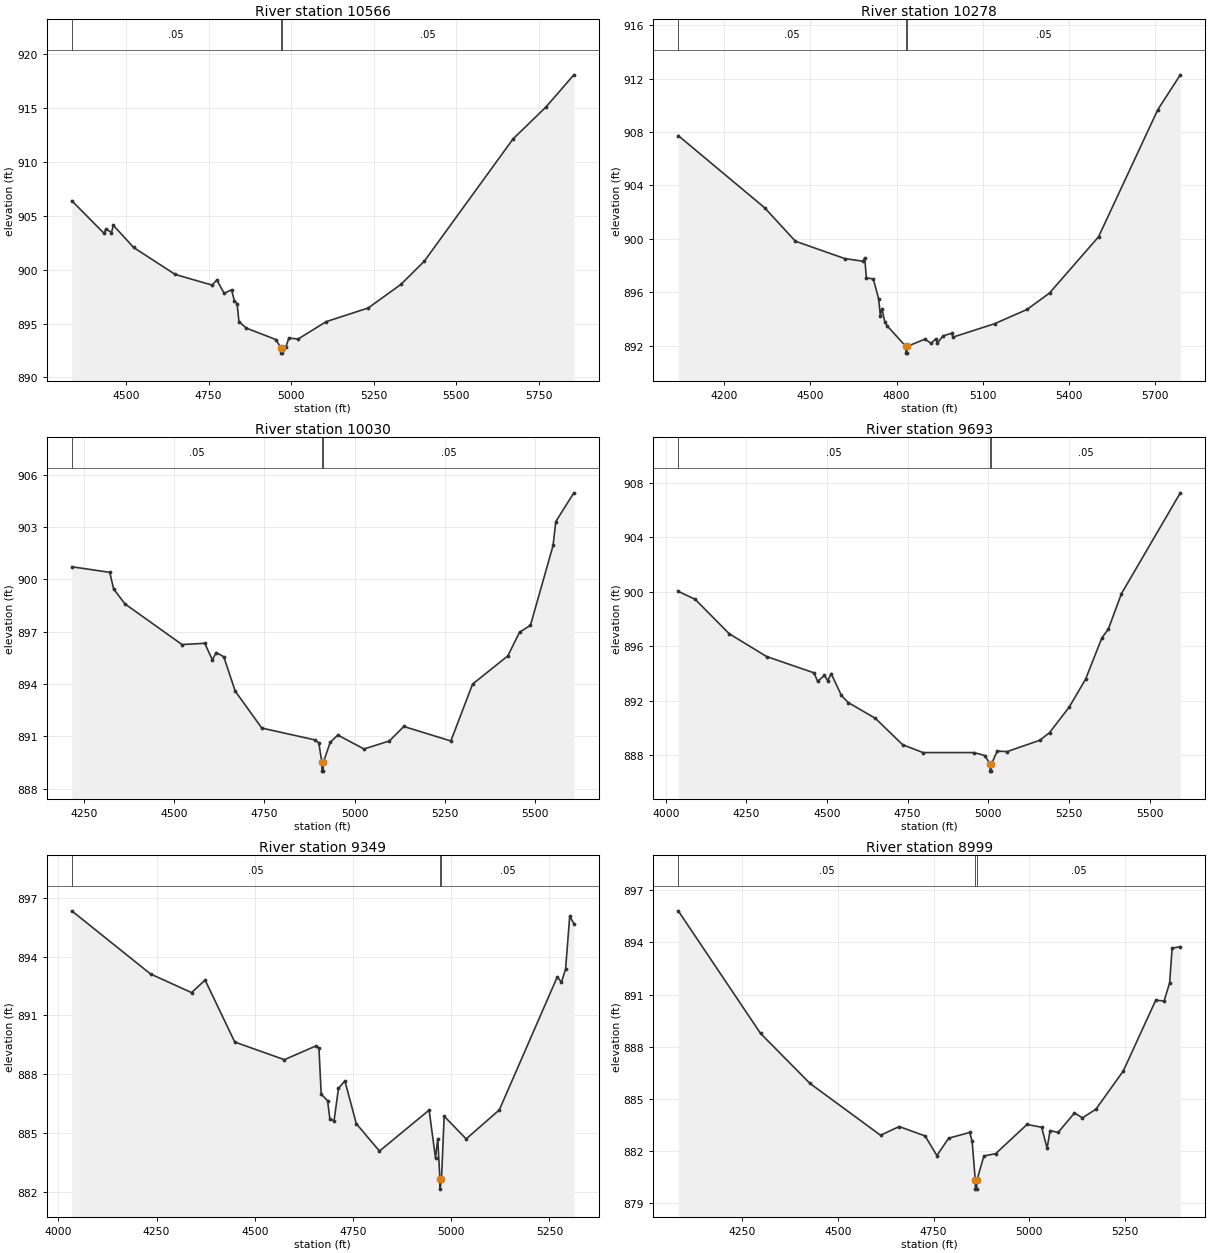
Type RM Length L Ch R = 1,10566,288,288,288
BEGIN DESCRIPTION:
S84 18.0
END DESCRIPTION:
XS GIS Cut Line= 3
      2287529.00      7069909.99      2287829.00      7069310.00
      2287229.03      7068710.03
#Sta/Elev= 30
  4336.2  906.40  4434.0  903.37  4439.6  903.79  4456.4  903.45  4462.0  904.12
  4523.5  902.06  4649.2  899.56  4761.0  898.57  4775.0  899.05  4797.4  897.81
  4819.7  898.14  4828.1  897.14  4836.5  896.84  4842.1  895.18  4864.5  894.58
  4953.9  893.52  4968.7  892.76  4968.9  892.26  4972.4  892.26  4972.7  892.76
  4984.6  892.87  4993.0  893.66  5021.2  893.57  5106.0  895.18  5233.3  896.45
  5332.3  898.64  5403.0  900.79  5671.7  912.14  5770.7  915.08  5855.5  918.08
#Mann=3,-1,0
  4336.2    0.05       0  4968.7   0.035       0  4972.7    0.05       0
Bank Sta=4968.7,4972.7
Exp/Cntr=0.3,0.1

Type RM Length L Ch R = 1,10278,248,248,248
BEGIN DESCRIPTION:
S84 17.0
END DESCRIPTION:
XS GIS Cut Line= 3
      2287729.01      7070109.97      2288079.00      7069210.00
      2287478.97      7068709.97
#Sta/Elev= 30
  4040.2  907.73  4340.6  902.33  4447.9  899.82  4619.6  898.52  4683.6  898.32
  4688.9  898.58  4694.7  897.07  4718.8  897.00  4737.6  895.49  4743.3  894.25
  4748.7  894.77  4759.1  893.76  4767.9  893.46  4832.2  891.94  4832.4  891.44
  4835.9  891.44  4836.2  891.94  4898.5  892.49  4920.0  892.17  4936.5  892.52
  4941.8  892.18  4961.0  892.73  4990.9  892.92  4996.3  892.64  5140.6  893.64
  5253.8  894.71  5331.9  895.94  5502.4  900.15  5708.8  909.68  5786.9  912.28
#Mann=3,-1,0
  4040.2    0.05       0  4832.2   0.035       0  4836.2    0.05       0
Bank Sta=4832.2,4836.2
Exp/Cntr=0.3,0.1

Type RM Length L Ch R = 1,10030,337,337,337
BEGIN DESCRIPTION:
S84 16.0
END DESCRIPTION:
XS GIS Cut Line= 3
      2288029.00      7069860.00      2288279.00      7069110.00
      2288329.00      7068510.05
#Sta/Elev= 30
  4215.7  900.72  4321.1  900.40  4331.7  899.45  4363.3  898.59  4521.4  896.26
  4584.6  896.33  4605.7  895.38  4616.3  895.80  4637.3  895.56  4669.0  893.59
  4742.7  891.47  4890.3  890.79  4900.9  890.62  4909.4  889.50  4909.7  889.00
  4913.2  889.00  4913.4  889.50  4932.5  890.65  4953.6  891.07  5026.3  890.27
  5096.6  890.73  5136.7  891.56  5267.2  890.73  5327.4  893.99  5425.2  895.61
  5457.8  896.97  5487.9  897.36  5550.7  901.94  5558.2  903.31  5608.3  904.96
#Mann=3,-1,0
  4215.7    0.05       0  4909.4   0.035       0  4913.4    0.05       0
Bank Sta=4909.4,4913.4
Exp/Cntr=0.3,0.1

Type RM Length L Ch R = 1,9693,344,344,344
BEGIN DESCRIPTION:
S84 15.0
END DESCRIPTION:
XS GIS Cut Line= 3
      2288279.00      7069910.00      2288579.00      7069010.00
      2288478.99      7068409.96
#Sta/Elev= 30
  4038.5  900.03  4091.2  899.44  4196.6  896.92  4312.6  895.25  4460.1  894.05
  4470.7  893.43  4491.8  893.86  4502.3  893.48  4512.8  894.00  4544.5  892.40
  4565.6  891.88  4649.9  890.72  4734.2  888.79  4797.5  888.21  4955.6  888.21
  4989.7  887.99  5005.5  887.35  5005.7  886.85  5009.2  886.85  5009.5  887.35
  5027.7  888.32  5058.2  888.28  5159.5  889.11  5189.9  889.67  5250.8  891.54
  5301.5  893.58  5352.2  896.61  5372.4  897.27  5413.0  899.86  5595.5  907.25
#Mann=3,-1,0
  4038.5    0.05       0  5005.5   0.035       0  5009.5    0.05       0
Bank Sta=5005.5,5009.5
Exp/Cntr=0.3,0.1

Type RM Length L Ch R = 1,9349,350,350,350
BEGIN DESCRIPTION:
S84 14.0
END DESCRIPTION:
XS GIS Cut Line= 3
      2288429.00      7069760.00      2288879.00      7068910.00
      2288779.00      7068609.99
#Sta/Elev= 30
  4034.1  896.33  4234.6  893.11  4339.0  892.16  4373.5  892.80  4449.0  889.64
  4575.3  888.74  4656.4  889.45  4663.3  889.32  4669.0  886.98  4685.3  886.65
  4691.0  885.72  4701.7  885.62  4713.0  887.28  4729.3  887.66  4758.3  885.48
  4817.3  884.08  4943.7  886.17  4960.0  883.72  4965.7  884.72  4971.2  882.64
  4971.5  882.14  4975.2  882.64  4982.0  885.86  5038.0  884.70  5122.4  886.18
  5269.9  892.96  5280.5  892.69  5291.0  893.35  5301.6  896.06  5312.1  895.68
#Mann=3,-1,0
  4034.1    0.05       0  4971.2   0.033       0  4975.2    0.05       0
Bank Sta=4971.2,4975.2
Exp/Cntr=0.3,0.1

Type RM Length L Ch R = 1,8999,400,400,400
BEGIN DESCRIPTION:
S84 13.0
END DESCRIPTION:
XS GIS Cut Line= 3
      2289379.00      7069759.98      2289179.00      7068860.00
      2288879.04      7068610.03
#Sta/Elev= 30
  4082.3  895.82  4297.4  888.77  4426.7  885.89  4611.1  882.91  4659.8  883.41
  4727.6  882.87  4758.4  881.74  4789.1  882.74  4844.2  883.07  4850.6  882.56
  4858.8  880.31  4859.1  879.81  4862.6  879.81  4862.8  880.31  4881.3  881.72
  4912.0  881.85  4994.0  883.53  5032.2  883.37  5046.5  882.16  5054.3  883.18
  5075.2  883.07  5118.1  884.19  5139.0  883.91  5174.1  884.41  5245.7  886.61
  5330.3  890.67  5352.4  890.64  5366.8  891.68  5373.3  893.67  5394.7  893.76
#Mann=3,-1,0
  4082.3    0.05       0  4858.8   0.033       0  4862.8    0.05       0
Bank Sta=4858.8,4862.8
Exp/Cntr=0.3,0.1

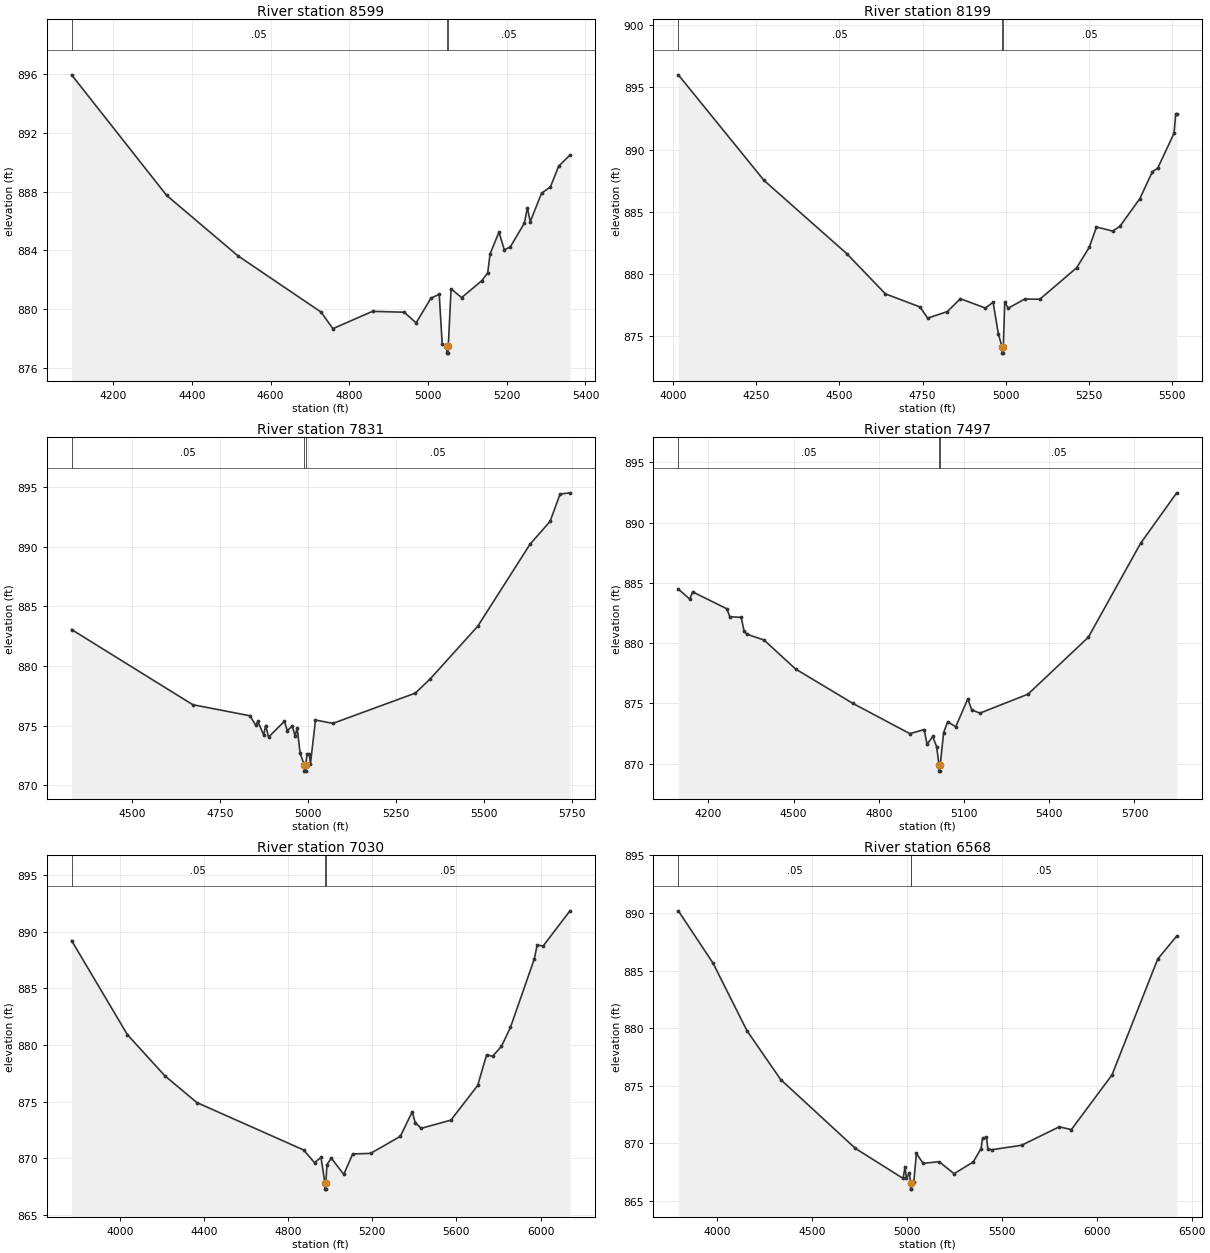
Type RM Length L Ch R = 1,8599,400,400,400
BEGIN DESCRIPTION:
S84 12.0
END DESCRIPTION:
XS GIS Cut Line= 3
      2289479.00      7069759.96      2289579.00      7068860.00
      2289378.97      7068559.96
#Sta/Elev= 30
  4094.5  895.97  4335.9  887.75  4517.0  883.63  4728.3  879.79  4758.5  878.66
  4859.1  879.84  4939.6  879.78  4969.8  879.05  5007.5  880.74  5028.5  881.00
  5036.1  877.61  5047.6  877.49  5047.8  876.99  5051.3  876.99  5051.6  877.49
  5058.6  881.37  5085.6  880.78  5136.7  881.93  5151.7  882.47  5157.7  883.76
  5180.3  885.24  5193.8  884.04  5208.8  884.22  5244.9  885.86  5252.4  886.89
  5259.9  885.96  5288.4  887.89  5311.0  888.33  5332.0  889.74  5360.6  890.50
#Mann=3,-1,0
  4094.5    0.05       0  5047.6   0.033       0  5051.6    0.05       0
Bank Sta=5047.6,5051.6
Exp/Cntr=0.3,0.1

Type RM Length L Ch R = 1,8199,368,368,368
BEGIN DESCRIPTION:
S84 11.0
END DESCRIPTION:
XS GIS Cut Line= 3
      2289578.99      7069760.02      2289979.00      7068860.00
      2289729.00      7068409.99
#Sta/Elev= 30
  4015.1  896.00  4273.0  887.52  4521.9  881.64  4638.2  878.41  4742.2  877.36
  4765.4  876.46  4824.9  876.99  4863.9  878.02  4939.1  877.27  4962.4  877.74
  4978.1  875.20  4989.1  874.15  4989.4  873.65  4992.9  873.65  4993.1  874.15
  4997.3  877.73  5008.0  877.26  5057.2  877.99  5103.0  877.98  5213.9  880.51
  5251.7  882.15  5273.4  883.78  5322.6  883.45  5344.3  883.85  5403.8  886.05
  5441.6  888.22  5457.6  888.50  5506.8  891.31  5511.9  892.85  5514.8  892.85
#Mann=3,-1,0
  4015.1    0.05       0  4989.1   0.033       0  4993.1    0.05       0
Bank Sta=4989.1,4993.1
Exp/Cntr=0.3,0.1

Type RM Length L Ch R = 1,7831,334,334,334
BEGIN DESCRIPTION:
S84 10.0
END DESCRIPTION:
XS GIS Cut Line= 3
      2290028.99      7069410.01      2290329.00      7068810.00
      2289829.03      7068260.03
#Sta/Elev= 30
  4329.3  883.06  4673.1  876.75  4835.2  875.82  4852.0  875.02  4857.6  875.35
  4874.4  874.21  4879.9  875.00  4888.3  874.03  4933.1  875.35  4941.4  874.57
  4955.4  874.95  4963.8  874.12  4969.4  874.82  4977.8  872.68  4989.8  871.67
  4990.0  871.17  4993.5  871.17  4993.8  871.67  4997.3  872.60  5003.5  872.60
  5007.2  871.81  5021.4  875.46  5070.8  875.18  5304.6  877.72  5347.1  878.92
  5481.6  883.33  5630.3  890.23  5687.0  892.14  5715.4  894.44  5743.4  894.54
#Mann=3,-1,0
  4329.3    0.05       0  4989.8   0.033       0  4993.8    0.05       0
Bank Sta=4989.8,4993.8
Exp/Cntr=0.3,0.1

Type RM Length L Ch R = 1,7497,467,467,467
BEGIN DESCRIPTION:
S84 9.0
END DESCRIPTION:
XS GIS Cut Line= 3
      2290529.00      7069610.02      2290629.00      7068710.00
      2290028.99      7068109.99
#Sta/Elev= 30
  4094.4  884.49  4134.7  883.66  4144.7  884.26  4265.5  882.85  4275.5  882.20
  4315.8  882.14  4325.8  881.00  4335.9  880.74  4396.3  880.26  4506.9  877.86
  4708.2  875.01  4909.4  872.49  4959.7  872.83  4969.8  871.61  4989.9  872.26
  5003.5  871.41  5012.1  869.88  5012.3  869.38  5015.8  869.38  5016.1  869.88
  5028.2  872.58  5042.4  873.48  5070.7  873.06  5113.1  875.37  5127.2  874.47
  5155.5  874.19  5325.2  875.77  5537.4  880.49  5721.2  888.28  5848.5  892.48
#Mann=3,-1,0
  4094.4    0.05       0  5012.1   0.035       0  5016.1    0.05       0
Bank Sta=5012.1,5016.1
Exp/Cntr=0.3,0.1

Type RM Length L Ch R = 1,7030,462,462,462
BEGIN DESCRIPTION:
S84 8.0
END DESCRIPTION:
XS GIS Cut Line= 3
      2291379.00      7069859.98      2291079.00      7068660.00
      2290278.99      7067859.99
#Sta/Elev= 30
  3771.2  889.21  4036.6  880.91  4214.4  877.29  4366.5  874.93  4874.1  870.75
  4925.7  869.63  4956.6  870.10  4975.2  867.80  4975.4  867.30  4978.9  867.30
  4979.2  867.80  4984.9  869.47  5005.5  870.03  5064.7  868.60  5107.1  870.40
  5192.0  870.45  5333.4  871.95  5390.0  874.12  5404.1  873.16  5432.4  872.66
  5573.8  873.38  5701.1  876.44  5743.5  879.14  5771.8  879.01  5814.2  879.89
  5856.6  881.55  5969.8  887.57  5983.9  888.81  6012.2  888.73  6139.5  891.83
#Mann=3,-1,0
  3771.2    0.05       0  4975.2   0.035       0  4979.2    0.05       0
Bank Sta=4975.2,4979.2
Exp/Cntr=0.3,0.1

Type RM Length L Ch R = 1,6568,515,515,515
BEGIN DESCRIPTION:
S84 7.0
END DESCRIPTION:
XS GIS Cut Line= 3
      2291429.00      7069910.04      2291529.00      7068710.00
      2290628.98      7067609.97
#Sta/Elev= 30
  3795.8  890.19  3979.0  885.64  4157.1  879.79  4335.2  875.54  4729.1  869.56
  4979.9  866.96  4990.0  867.97  4997.5  866.96  5013.6  867.44  5019.5  866.53
  5019.8  866.03  5023.3  866.03  5023.6  866.53  5035.9  866.62  5050.2  869.13
  5085.4  868.27  5170.1  868.41  5248.4  867.37  5348.9  868.38  5390.5  869.55
  5398.4  870.43  5419.2  870.56  5426.4  869.52  5447.9  869.45  5604.4  869.84
  5802.5  871.44  5866.4  871.20  6080.3  875.94  6321.5  886.01  6421.3  888.00
#Mann=3,-1,0
  3795.8    0.05       0  5019.5   0.035       0  5023.6    0.05       0
Bank Sta=5019.5,5023.6
Exp/Cntr=0.3,0.1

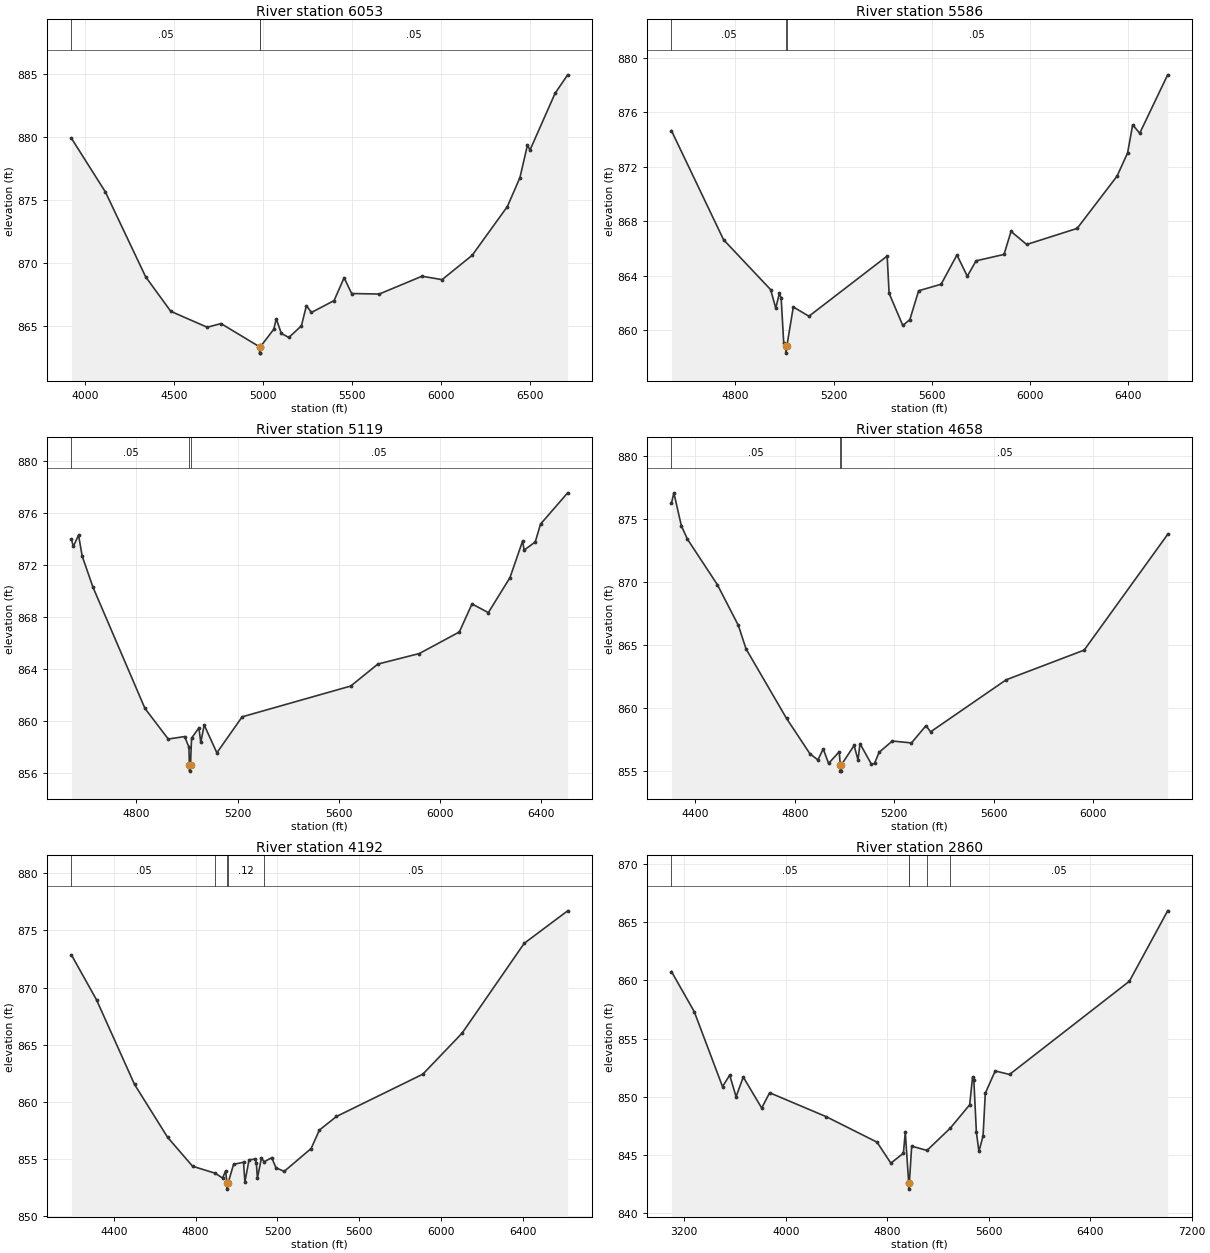
Type RM Length L Ch R = 1,6053,467,467,467
BEGIN DESCRIPTION:
S84 6.0
END DESCRIPTION:
XS GIS Cut Line= 3
      2292778.98      7069509.98      2292029.00      7068710.00
      2290829.01      7067510.01
#Sta/Elev= 30
  3921.2  879.88  4112.4  875.63  4338.6  868.92  4480.2  866.18  4685.4  864.92
  4763.0  865.21  4980.3  863.37  4980.6  862.87  4984.1  862.87  4984.4  863.37
  5060.2  864.76  5074.3  865.59  5102.6  864.43  5145.0  864.11  5215.7  865.03
  5244.0  866.63  5272.3  866.09  5399.6  867.03  5456.2  868.84  5498.6  867.59
  5654.2  867.55  5894.6  868.96  6007.7  868.69  6177.4  870.62  6375.4  874.48
  6446.1  876.77  6488.5  879.35  6502.7  878.95  6644.1  883.45  6714.8  884.91
#Mann=3,-1,0
  3921.2    0.05       0  4980.3   0.035       0  4984.4    0.05       0
Bank Sta=4980.3,4984.4
Exp/Cntr=0.3,0.1

Type RM Length L Ch R = 1,5586,467,467,467
BEGIN DESCRIPTION:
S84 5.0
END DESCRIPTION:
XS GIS Cut Line= 3
      2292828.99      7069009.99      2292479.00      7068710.00
      2291479.01      7067510.01
#Sta/Elev= 30
  4539.1  874.66  4751.5  866.65  4943.5  862.98  4964.4  861.62  4978.7  862.70
  4986.3  862.39  4996.8  859.06  5005.1  858.82  5005.4  858.32  5009.4  858.82
  5035.9  861.71  5099.6  861.03  5418.6  865.45  5426.4  862.72  5482.3  860.35
  5511.0  860.78  5546.8  862.90  5638.5  863.38  5703.0  865.53  5745.3  863.97
  5781.1  865.10  5895.0  865.57  5923.6  867.26  5987.4  866.30  6193.1  867.48
  6355.8  871.32  6398.7  873.02  6419.6  875.09  6448.2  874.47  6562.1  878.76
#Mann=3,-1,0
  4539.1    0.05       0  5005.1   0.035       0  5009.4    0.05       0
Bank Sta=5005.1,5009.4
Exp/Cntr=0.3,0.1

Type RM Length L Ch R = 1,5119,461,461,461
BEGIN DESCRIPTION:
S84 4.0
END DESCRIPTION:
XS GIS Cut Line= 3
      2293129.03      7068710.02      2292779.00      7068410.00
      2291579.01      7067510.01
#Sta/Elev= 30
  4543.5  873.99  4550.7  873.45  4571.5  874.33  4585.8  872.71  4628.6  870.31
  4833.8  860.99  4926.0  858.63  4990.8  858.82  5007.6  858.01  5009.6  856.66
  5010.0  856.16  5014.0  856.66  5018.1  858.70  5047.2  859.49  5054.5  858.37
  5068.1  859.71  5118.1  857.57  5218.1  860.34  5647.2  862.71  5754.5  864.40
  5918.1  865.21  6076.4  866.87  6126.4  869.03  6191.0  868.36  6276.4  871.05
  6326.4  873.87  6332.6  873.17  6376.4  873.80  6397.2  875.17  6504.5  877.58
#Mann=3,-1,0
  4543.5    0.05       0  5009.6   0.033       0  5014.0    0.05       0
Bank Sta=5009.6,5014
Exp/Cntr=0.3,0.1

Type RM Length L Ch R = 1,4658,466,466,466
BEGIN DESCRIPTION:
S84 3.0
END DESCRIPTION:
XS GIS Cut Line= 3
      2293279.01      7068710.03      2293029.00      7068060.00
      2291828.95      7067559.98
#Sta/Elev= 30
  4303.6  876.28  4313.3  877.11  4343.3  874.50  4367.9  873.43  4487.9  869.83
  4572.6  866.59  4603.6  864.72  4766.5  859.20  4860.8  856.39  4892.9  855.90
  4914.3  856.78  4935.8  855.62  4978.6  856.55  4982.9  855.51  4983.3  855.01
  4986.9  855.01  4987.3  855.51  5038.5  857.05  5054.2  855.90  5062.3  857.19
  5108.4  855.55  5120.8  855.63  5139.3  856.51  5192.3  857.40  5269.3  857.25
  5327.8  858.62  5346.2  858.13  5650.1  862.26  5964.2  864.62  6300.1  873.81
#Mann=3,-1,0
  4303.6    0.05       0  4982.9   0.033       0  4987.3    0.05       0
Bank Sta=4982.9,4987.3
Exp/Cntr=0.3,0.1

Type RM Length L Ch R = 1,4192,1332,1332,1332
BEGIN DESCRIPTION:
S84 2.0
END DESCRIPTION:
XS GIS Cut Line= 3
      2293579.00      7068460.01      2293279.00      7067710.00
      2291679.00      7067460.00
#Sta/Elev= 30
  4192.5  872.85  4315.0  868.93  4500.8  861.54  4662.4  856.92  4784.9  854.38
  4895.5  853.77  4931.6  853.35  4946.4  853.96  4953.7  852.88  4954.1  852.38
  4958.1  852.88  4985.5  854.55  5034.2  854.73  5040.8  852.99  5061.0  854.94
  5091.4  855.01  5096.9  854.65  5102.0  853.34  5121.7  855.10  5135.0  854.77
  5172.3  855.13  5192.6  854.25  5233.1  853.93  5364.7  855.93  5405.1  857.54
  5488.6  858.73  5911.2  862.43  6103.5  866.02  6407.2  873.87  6619.7  876.71
#Mann=5,-1,0
  4192.5    0.05       0  4895.5    0.12       0  4953.7    0.07       0
  4958.1    0.12       0  5135.0    0.05       0
Bank Sta=4953.7,4958.1
Exp/Cntr=0.3,0.1

Type RM Length L Ch R = 1,2860,914,914,914
BEGIN DESCRIPTION:
S84 1.0
END DESCRIPTION:
XS GIS Cut Line= 3
      2295329.00      7068660.00      2294229.00      7067110.00
      2292229.03      7067310.00
#Sta/Elev= 30
  3099.6  860.75  3279.2  857.31  3501.9  850.88  3558.5  851.86  3608.9  850.01
  3665.5  851.70  3810.7  849.04  3873.4  850.35  4318.7  848.30  4719.8  846.11
  4828.6  844.31  4927.7  845.16  4942.4  846.97  4969.6  842.58  4970.1  842.08
  4974.3  842.58  4992.9  845.77  5113.4  845.40  5296.9  847.31  5450.0  849.32
  5472.6  851.69  5482.7  851.45  5502.8  846.97  5522.9  845.31  5555.5  846.65
  5573.1  850.31  5651.0  852.22  5764.0  851.92  6708.7  859.92  7010.2  865.96
#Mann=5,-1,0
  3099.6    0.05       0  4969.6   0.033       0  4974.3    0.05       0
  5113.4    0.12       0  5296.9    0.05       0
Bank Sta=4969.6,4974.3
Exp/Cntr=0.3,0.1

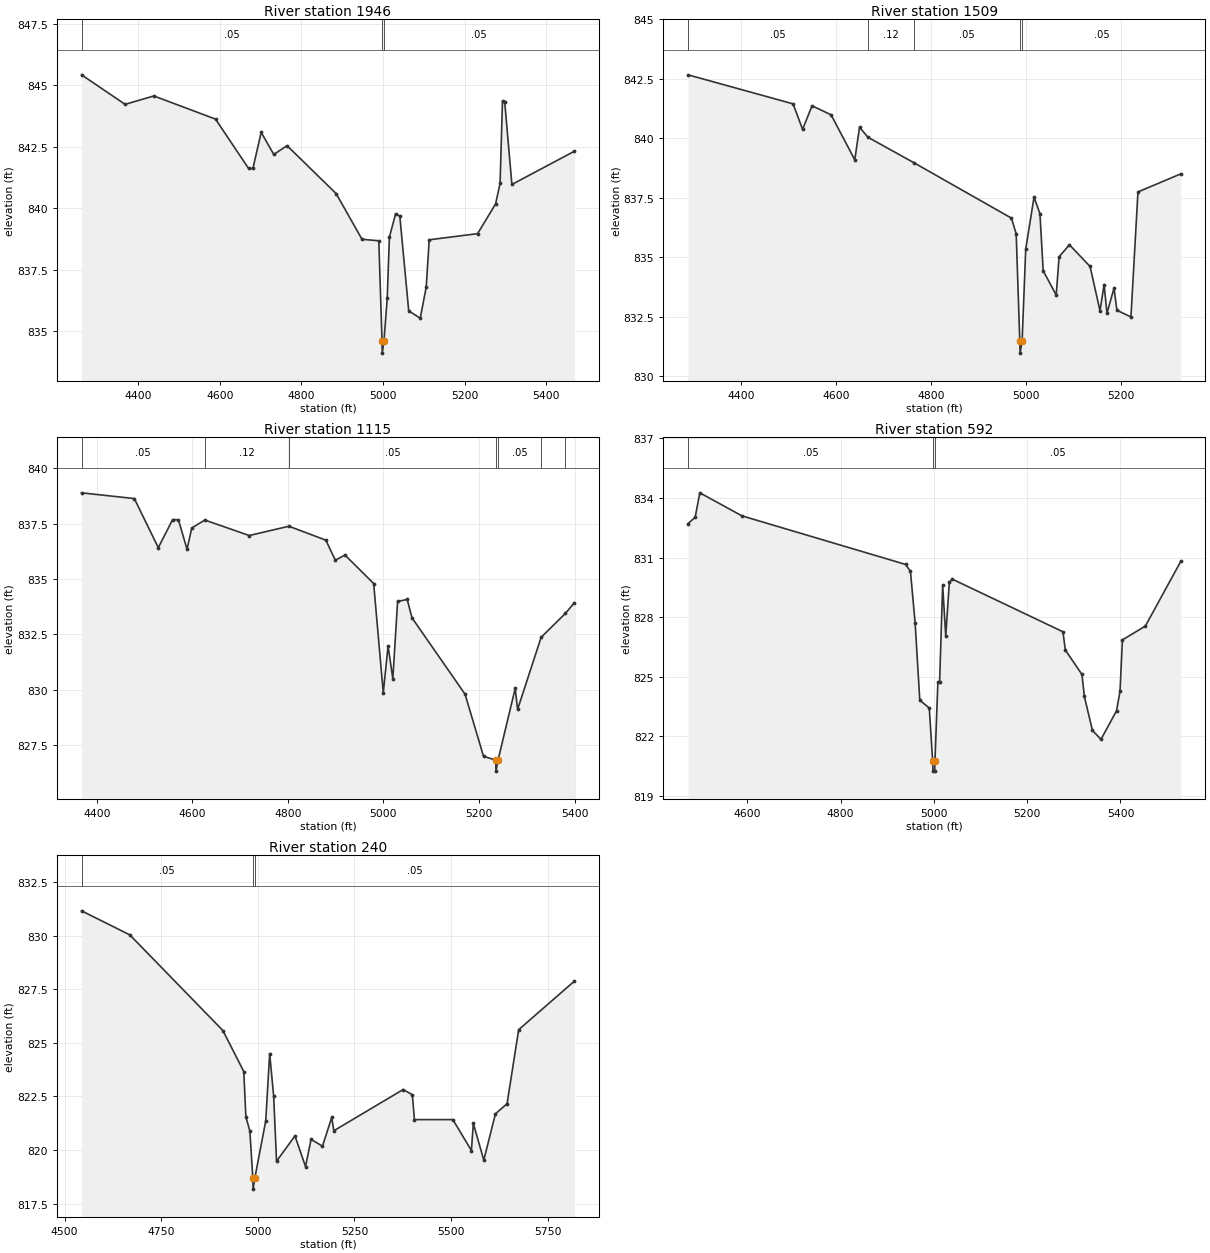
Type RM Length L Ch R = 1,1946,437,437,437
BEGIN DESCRIPTION:
1080
END DESCRIPTION:
XS GIS Cut Line= 5
      2294652.19      7067485.87      2294697.34      7067102.11
      2294793.39      7066705.69      2294743.21      7066639.39
      2294443.83      7066501.62
#Sta/Elev= 30
  4261.5  845.43  4368.1  844.23  4438.6  844.57  4589.6  843.63  4670.7  841.62
  4681.2  841.62  4701.5  843.09  4732.4  842.19  4764.8  842.55  4885.1  840.60
  4948.5  838.74  4989.6  838.68  4997.5  834.61  4998.1  834.11  5002.3  834.61
  5010.2  836.34  5015.6  838.83  5030.8  839.78  5041.1  839.68  5062.9  835.83
  5091.1  835.53  5105.7  836.79  5113.1  838.72  5231.6  838.97  5275.7  840.18
  5286.7  841.02  5292.6  844.37  5298.1  844.31  5315.6  840.97  5468.5  842.32
#Mann=3,-1,0
  4261.5    0.05       0  4997.5   0.033       0  5002.3    0.05       0
Bank Sta=4997.5,5002.3
Exp/Cntr=0.3,0.1

Type RM Length L Ch R = 1,1509,394,394,394
BEGIN DESCRIPTION:
S84 0.3
END DESCRIPTION:
XS GIS Cut Line= 4
      2295166.08      7067421.32      2295201.86      7066689.96
      2295202.76      7066671.41      2294967.18      7066505.06
#Sta/Elev= 30
  4287.8  842.67  4509.4  841.45  4529.4  840.38  4549.4  841.37  4589.5  840.99
  4639.5  839.10  4649.5  840.47  4667.1  840.05  4764.9  838.97  4969.9  836.65
  4979.9  835.99  4987.5  831.48  4988.1  830.98  4992.4  831.48  5000.0  835.35
  5017.5  837.53  5030.0  836.84  5036.8  834.44  5064.3  833.42  5070.4  835.03
  5092.2  835.53  5135.7  834.62  5156.6  832.76  5165.3  833.86  5171.4  832.66
  5186.2  833.71  5192.3  832.78  5221.9  832.50  5236.7  837.75  5327.0  838.51
#Mann=5,-1,0
  4287.8    0.05       0  4667.1    0.12       0  4764.9    0.05       0
  4987.5   0.033       0  4992.4    0.05       0
Bank Sta=4987.5,4992.4
Exp/Cntr=0.3,0.1

Type RM Length L Ch R = 1,1115,523,523,523
BEGIN DESCRIPTION:
S84 0.2
END DESCRIPTION:
XS GIS Cut Line= 4
      2295615.59      7067290.31      2295574.47      7066582.23
      2295511.54      7066460.19      2295327.44      7066474.06
#Sta/Elev= 30
  4368.3  838.90  4478.8  838.64  4528.9  836.42  4558.9  837.69  4571.1  837.68
  4589.0  836.35  4599.0  837.31  4626.3  837.67  4719.2  836.97  4802.3  837.39
  4879.5  836.76  4899.5  835.85  4919.5  836.09  4979.6  834.80  4999.7  829.86
  5009.7  831.98  5019.7  830.50  5029.7  833.99  5049.8  834.08  5059.8  833.25
  5170.8  829.80  5209.5  826.99  5235.0  826.82  5235.6  826.32  5239.9  826.82
  5275.8  830.06  5280.8  829.11  5330.1  832.37  5380.9  833.45  5399.5  833.93
#Mann=7,-1,0
  4368.3    0.05       0  4626.3    0.12       0  4802.3    0.05       0
  5235.0   0.033       0  5239.9    0.05       0  5330.1    0.12       0
  5380.9    0.05       0
Bank Sta=5235,5239.9
Exp/Cntr=0.3,0.1

Type RM Length L Ch R = 1,592,352,352,352
BEGIN DESCRIPTION:
S84 0.1
END DESCRIPTION:
XS GIS Cut Line= 5
      2296030.19      7067085.26      2296069.47      7066574.63
      2296070.23      7066547.58      2295935.45      7066390.13
      2295635.62      7066313.22
#Sta/Elev= 30
  4473.2  832.71  4488.5  833.03  4498.5  834.26  4588.8  833.10  4939.8  830.65
  4949.9  830.30  4959.9  827.71  4969.9  823.81  4990.2  823.42  4997.5  820.74
  4998.1  820.24  5001.8  820.24  5002.4  820.74  5008.7  824.74  5012.4  824.74
  5018.9  829.61  5025.5  827.04  5033.2  829.75  5039.7  829.91  5276.7  827.26
  5281.8  826.34  5317.4  825.11  5322.6  824.00  5339.9  822.29  5358.2  821.84
  5391.5  823.28  5399.0  824.26  5404.1  826.85  5453.4  827.55  5529.2  830.81
#Mann=3,-1,0
  4473.2    0.05       0  4997.5   0.033       0  5002.4    0.05       0
Bank Sta=4997.5,5002.4
Exp/Cntr=0.3,0.1

Type RM Length L Ch R = 1,240,0,0,0
BEGIN DESCRIPTION:
1685
END DESCRIPTION:
XS GIS Cut Line= 5
      2296206.20      7066907.41      2296415.85      7066553.40
      2296377.88      7066391.69      2296074.06      7066267.96
      2295705.36      7066292.46
#Sta/Elev= 30
  4543.8  831.15  4668.6  830.03  4909.6  825.57  4963.6  823.66  4969.0  821.55
  4979.3  820.89  4987.1  818.68  4987.7  818.18  4992.0  818.68  5020.4  821.36
  5030.6  824.50  5040.9  822.51  5048.4  819.48  5096.0  820.66  5123.4  819.23
  5137.7  820.50  5167.2  820.18  5191.2  821.52  5196.6  820.90  5375.8  822.82
  5399.8  822.58  5405.2  821.42  5504.6  821.42  5552.6  819.98  5557.6  821.24
  5584.7  819.53  5614.8  821.69  5644.9  822.16  5674.9  825.61  5818.9  827.87
#Mann=3,-1,0
  4543.8    0.05       0  4987.1   0.033       0  4992.0    0.05       0
Bank Sta=4987.1,4992
Exp/Cntr=0.3,0.1

Chan Stop Cuts=-1