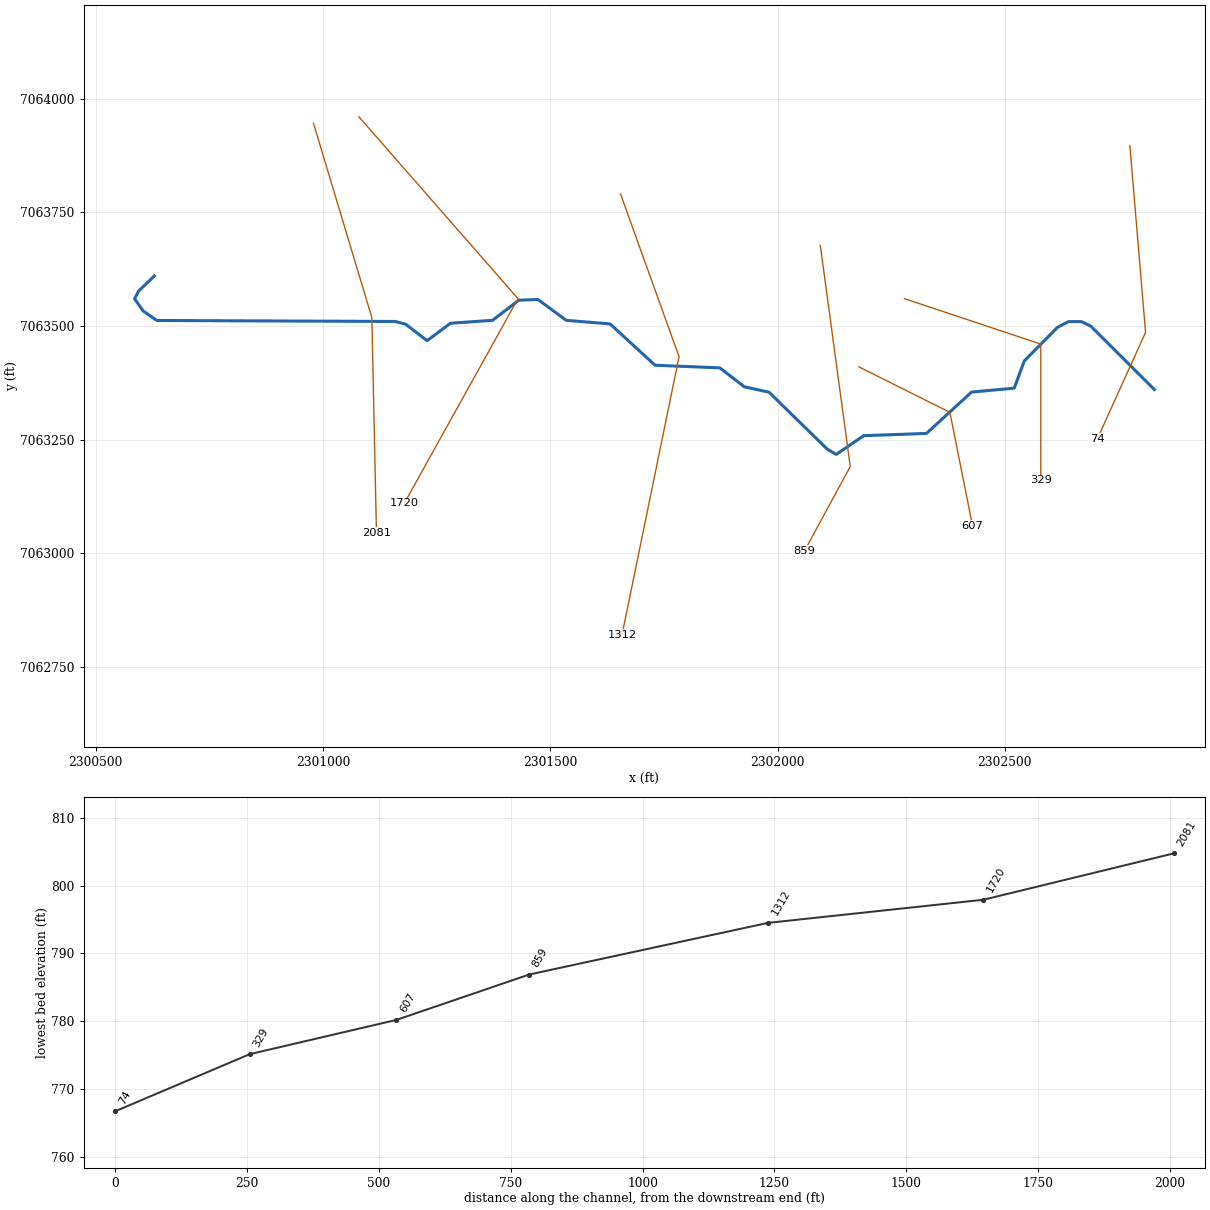
--- S86.prj (project) ---

Proj Title=S86 Base Level Engineering
Current Plan=p01
Default Exp/Contr=0.3,0.1
English Units
Geom File=g01
Flow File=f01
Plan File=p01
BEGIN DESCRIPTION:
S86
END DESCRIPTION:

--- S86.p01 (plan) ---

Plan Title=Multiple Run
Short Identifier=Multiple
Geom File=g01
Flow File=f01
Subcritical Flow
K Sum by GR= 0
Std Step Tol= 0.01
Critical Tol= 0.01
Num of Std Step Trials= 20
Max Error Tol= 0.3
Flow Tol Ratio= 0.001
Split Flow NTrial= 30
Split Flow Tol= 0.02
Split Flow Ratio= 0.02
Log Output Level= 0
Friction Slope Method= 1
Unsteady Friction Slope Method= 2
Unsteady Bridges Friction Slope Method= 1
Parabolic Critical Depth
Global Vel Dist=  1 , 1 , 1
Global Log Level= 0
CheckData=True
Encroach Param= -1, 0, 0, 0
BEGIN DESCRIPTION:
Multiple Run
END DESCRIPTION:

--- S86.f01 (steady flow) ---

Flow Title=Multiple
Number of Profiles=7
Profile Names=10-year,25-year,50-year,1pct_min,100-year,1pct_plu,500-year
River Rch & RM= S86,Reach-1,2081
     332     442     530     317     632    1260     899
Boundary for River Rch & Prof#=S86,Reach-1,1
Up Type=0
Dn Type=3
Dn Slope=0.005
Boundary for River Rch & Prof#=S86,Reach-1,2
Up Type=0
Dn Type=3
Dn Slope=0.005
Boundary for River Rch & Prof#=S86,Reach-1,3
Up Type=0
Dn Type=3
Dn Slope=0.005
Boundary for River Rch & Prof#=S86,Reach-1,4
Up Type=0
Dn Type=3
Dn Slope=0.005
Boundary for River Rch & Prof#=S86,Reach-1,5
Up Type=0
Dn Type=3
Dn Slope=0.005
Boundary for River Rch & Prof#=S86,Reach-1,6
Up Type=0
Dn Type=3
Dn Slope=0.005
Boundary for River Rch & Prof#=S86,Reach-1,7
Up Type=0
Dn Type=3
Dn Slope=0.005

--- S86.g01 (geometry) ---

Geom Title=Existing Conditions

River Reach=S86,Reach-1
Reach XY= 30
      2300629.00      7063610.00      2300594.33      7063576.62
      2300585.44      7063559.67      2300604.59      7063532.75
      2300634.49      7063512.02      2301159.02      7063509.82
      2301181.45      7063503.98      2301229.00      7063467.56
      2301280.50      7063505.91      2301373.03      7063512.38
      2301430.73      7063556.63      2301472.88      7063558.18
      2301534.97      7063512.38      2301631.42      7063504.46
      2301730.47      7063413.56      2301873.07      7063407.75
      2301926.83      7063366.14      2301981.30      7063354.17
      2302108.97      7063229.29      2302128.90      7063217.32
      2302189.44      7063258.60      2302327.53      7063263.56
      2302426.64      7063354.44      2302520.66      7063363.17
      2302542.73      7063422.98      2302615.76      7063496.90
      2302639.63      7063509.46      2302668.36      7063509.46
      2302688.68      7063499.84      2302829.00      7063360.00

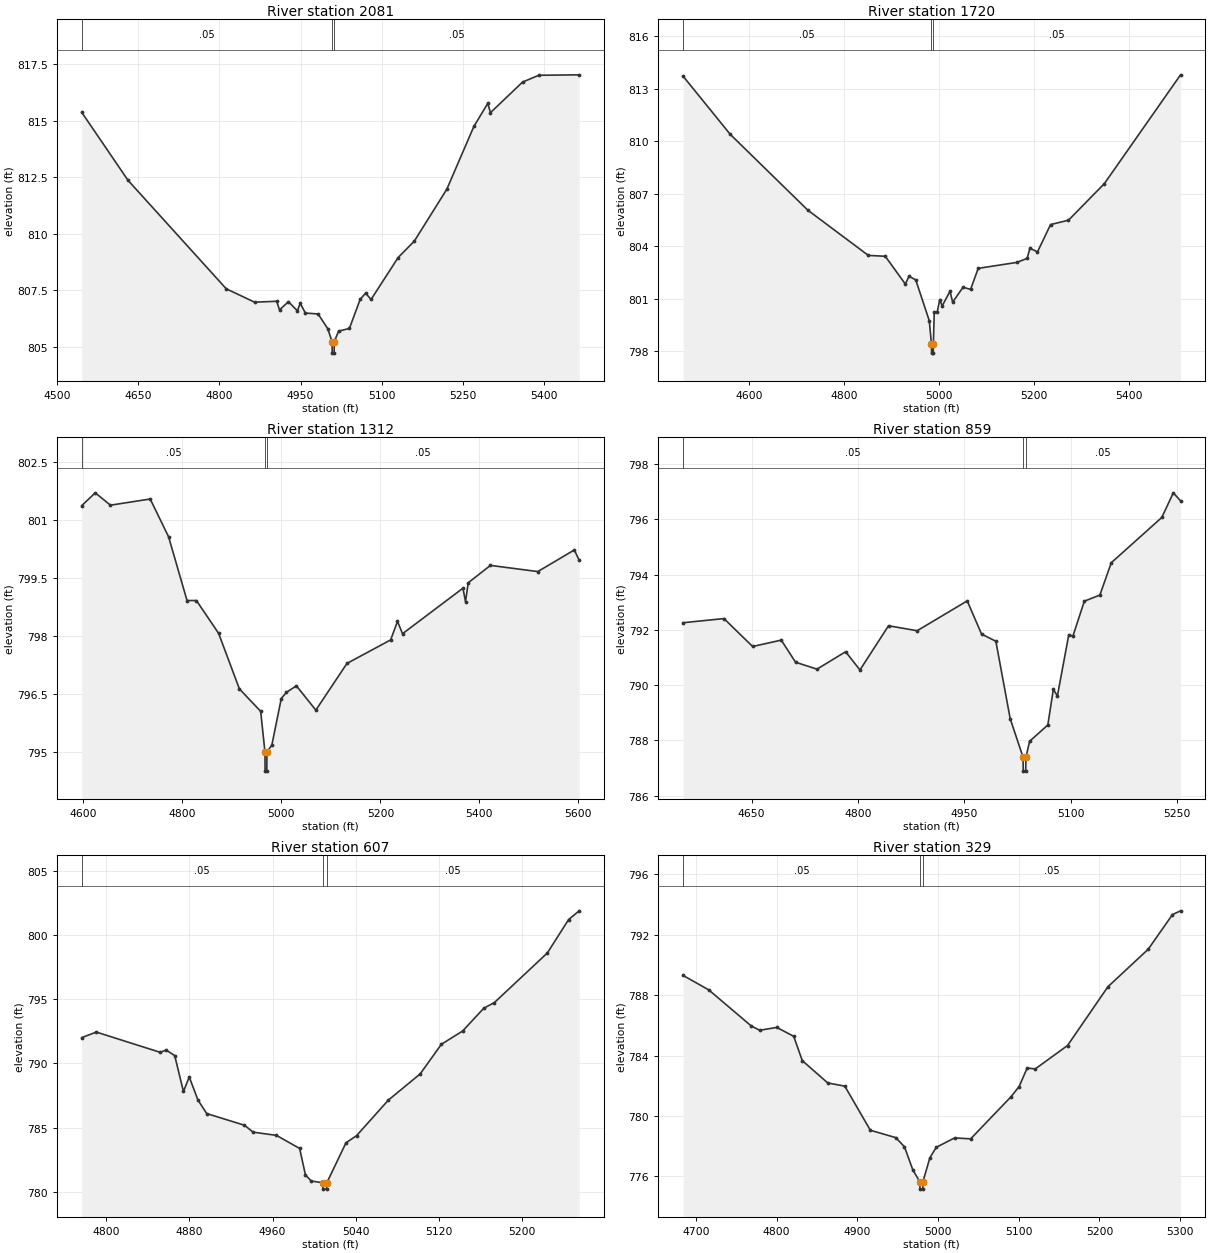
Type RM Length L Ch R = 1,2081,361,361,361
BEGIN DESCRIPTION:
s86 4.0
END DESCRIPTION:
XS GIS Cut Line= 3
      2300979.07      7063945.85      2301107.47      7063518.40
      2301117.61      7063045.33
#Sta/Elev= 30
  4545.5  815.36  4631.0  812.36  4812.6  807.57  4864.9  806.98  4905.8  807.02
  4911.0  806.64  4927.5  807.00  4944.1  806.60  4949.3  806.93  4958.8  806.50
  4982.3  806.46  5000.2  805.81  5008.2  805.23  5008.5  804.73  5012.0  804.73
  5012.2  805.23  5020.2  805.70  5040.2  805.82  5060.2  807.11  5070.2  807.38
  5080.2  807.10  5130.3  808.95  5160.3  809.68  5220.3  811.97  5270.3  814.74
  5296.0  815.76  5301.0  815.35  5360.3  816.70  5390.3  817.00  5465.0  817.02
#Mann=3,-1,0
  4545.5    0.05       0  5008.2   0.033       0  5012.2    0.05       0
Bank Sta=5008.2,5012.2
Exp/Cntr=0.3,0.1

Type RM Length L Ch R = 1,1720,408,408,408
BEGIN DESCRIPTION:
S86 3.0
END DESCRIPTION:
XS GIS Cut Line= 3
      2301078.99      7063960.01      2301429.00      7063560.00
      2301179.00      7063110.00
#Sta/Elev= 30
  4461.4  813.71  4560.6  810.39  4723.8  806.06  4851.0  803.48  4886.6  803.43
  4928.9  801.84  4936.4  802.29  4950.7  802.08  4979.2  799.75  4983.8  798.40
  4984.0  797.90  4987.5  797.90  4987.8  798.40  4989.6  800.24  4995.8  800.24
  5000.9  800.92  5006.6  800.61  5022.7  801.43  5028.4  800.81  5050.1  801.66
  5066.1  801.54  5082.1  802.74  5163.4  803.08  5185.1  803.31  5190.8  803.89
  5206.8  803.68  5234.3  805.24  5272.0  805.49  5347.5  807.58  5507.7  813.79
#Mann=3,-1,0
  4461.4    0.05       0  4983.8   0.033       0  4987.8    0.05       0
Bank Sta=4983.8,4987.8
Exp/Cntr=0.3,0.1

Type RM Length L Ch R = 1,1312,453,453,453
BEGIN DESCRIPTION:
1077
END DESCRIPTION:
XS GIS Cut Line= 3
      2301654.62      7063790.07      2301783.30      7063432.29
      2301657.77      7062820.35
#Sta/Elev= 30
  4596.7  801.38  4623.9  801.71  4654.6  801.39  4734.9  801.55  4772.1  800.57
  4809.3  798.92  4828.3  798.92  4873.1  798.07  4915.1  796.63  4958.1  796.05
  4966.7  795.00  4967.0  794.50  4970.5  794.50  4970.7  795.00  4980.6  795.17
  4999.7  796.38  5009.9  796.54  5030.3  796.71  5069.5  796.08  5132.4  797.29
  5220.7  797.90  5234.5  798.38  5244.7  798.06  5366.8  799.24  5371.9  798.89
  5377.4  799.38  5422.3  799.83  5518.0  799.67  5591.7  800.23  5601.6  799.96
#Mann=3,-1,0
  4596.7    0.05       0  4966.7   0.033       0  4970.7    0.05       0
Bank Sta=4966.7,4970.7
Exp/Cntr=0.3,0.1

Type RM Length L Ch R = 1,859,252,252,252
BEGIN DESCRIPTION:
1078
END DESCRIPTION:
XS GIS Cut Line= 3
      2302093.98      7063677.12      2302159.89      7063190.64
      2302059.44      7063005.45
#Sta/Elev= 30
  4553.5  792.26  4611.1  792.41  4651.5  791.40  4691.9  791.63  4712.1  790.83
  4742.3  790.58  4782.7  791.21  4802.9  790.55  4843.2  792.15  4883.6  791.97
  4954.2  793.05  4974.4  791.85  4994.6  791.59  5014.8  788.79  5033.0  787.39
  5033.2  786.89  5036.7  786.89  5037.0  787.39  5042.2  787.97  5067.9  788.56
  5075.7  789.85  5081.4  789.61  5097.5  791.83  5103.2  791.77  5119.4  793.04
  5141.3  793.26  5157.4  794.43  5228.7  796.07  5244.9  796.96  5255.1  796.67
#Mann=3,-1,0
  4553.5    0.05       0  5033.0   0.033       0  5037.0    0.05       0
Bank Sta=5033,5037
Exp/Cntr=0.3,0.1

Type RM Length L Ch R = 1,607,278,278,278
BEGIN DESCRIPTION:
S86 2.0
END DESCRIPTION:
XS GIS Cut Line= 3
      2302179.00      7063410.00      2302379.00      7063310.00
      2302429.01      7063059.95
#Sta/Elev= 30
  4776.4  792.01  4790.4  792.44  4851.9  790.86  4857.5  791.04  4865.8  790.61
  4874.2  787.81  4879.8  788.94  4888.2  787.14  4896.6  786.09  4932.9  785.18
  4941.3  784.64  4963.7  784.39  4986.0  783.37  4991.6  781.31  4997.2  780.83
  5008.2  780.70  5008.4  780.20  5011.9  780.20  5012.2  780.70  5030.6  783.81
  5040.8  784.37  5071.4  787.14  5102.0  789.18  5122.4  791.49  5142.8  792.52
  5163.2  794.30  5173.4  794.74  5224.4  798.61  5244.8  801.21  5255.0  801.89
#Mann=3,-1,0
  4776.4    0.05       0  5008.2   0.033       0  5012.2    0.05       0
Bank Sta=5008.2,5012.2
Exp/Cntr=0.3,0.1

Type RM Length L Ch R = 1,329,255,255,255
BEGIN DESCRIPTION:
S86 1.0
END DESCRIPTION:
XS GIS Cut Line= 3
      2302279.00      7063560.00      2302579.00      7063460.00
      2302579.00      7063160.03
#Sta/Elev= 30
  4684.3  789.31  4715.9  788.36  4768.6  785.97  4779.2  785.68  4800.3  785.87
  4821.3  785.28  4831.9  783.67  4863.5  782.19  4884.6  781.98  4916.2  779.06
  4947.8  778.57  4958.4  777.97  4968.9  776.43  4977.4  775.66  4977.7  775.16
  4981.2  775.16  4981.4  775.66  4990.0  777.24  4997.9  777.93  5020.5  778.55
  5040.5  778.49  5090.5  781.28  5100.5  781.95  5110.5  783.18  5120.5  783.12
  5160.5  784.67  5210.5  788.56  5260.5  791.05  5290.5  793.34  5300.5  793.59
#Mann=3,-1,0
  4684.3    0.05       0  4977.4   0.033       0  4981.4    0.05       0
Bank Sta=4977.4,4981.4
Exp/Cntr=0.3,0.1

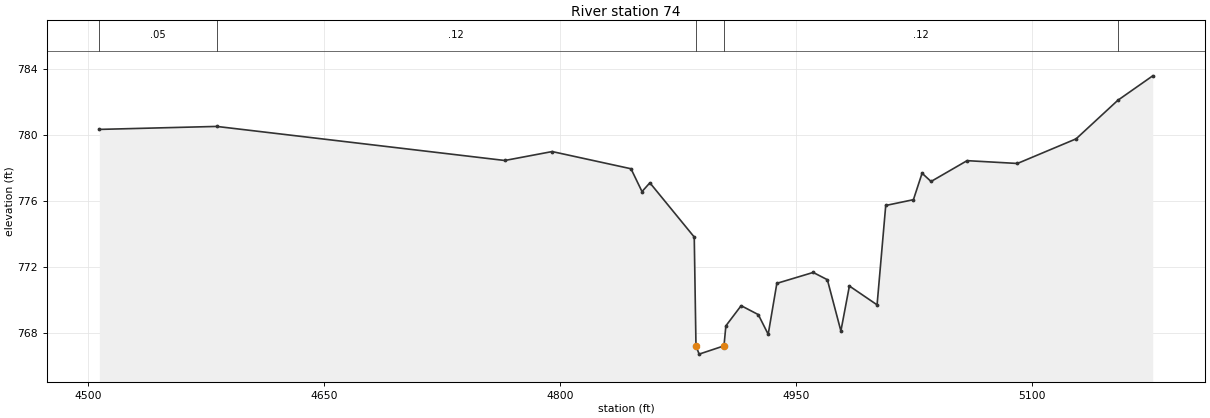
Type RM Length L Ch R = 1,74,0,0,0
BEGIN DESCRIPTION:
1079
END DESCRIPTION:
XS GIS Cut Line= 3
      2302774.98      7063896.76      2302809.50      7063485.64
      2302703.42      7063251.63
#Sta/Elev= 30
  4507.3  780.34  4581.9  780.52  4765.0  778.46  4795.1  779.00  4845.2  777.96
  4852.2  776.58  4857.2  777.11  4885.4  773.83  4886.5  767.25  4888.5  766.75
  4904.3  767.25  4905.5  768.46  4915.2  769.68  4926.1  769.14  4932.4  767.95
  4937.9  771.03  4961.0  771.69  4970.0  771.25  4978.6  768.15  4984.0  770.87
  5001.6  769.73  5007.1  775.74  5024.7  776.09  5030.2  777.69  5035.9  777.19
  5058.8  778.45  5090.8  778.28  5128.1  779.77  5154.6  782.10  5176.8  783.58
#Mann=5,-1,0
  4507.3    0.05       0  4581.9    0.12       0  4886.5    0.07       0
  4904.3    0.12       0  5154.6    0.05       0
Bank Sta=4886.5,4904.3
Exp/Cntr=0.3,0.1

Chan Stop Cuts=-1