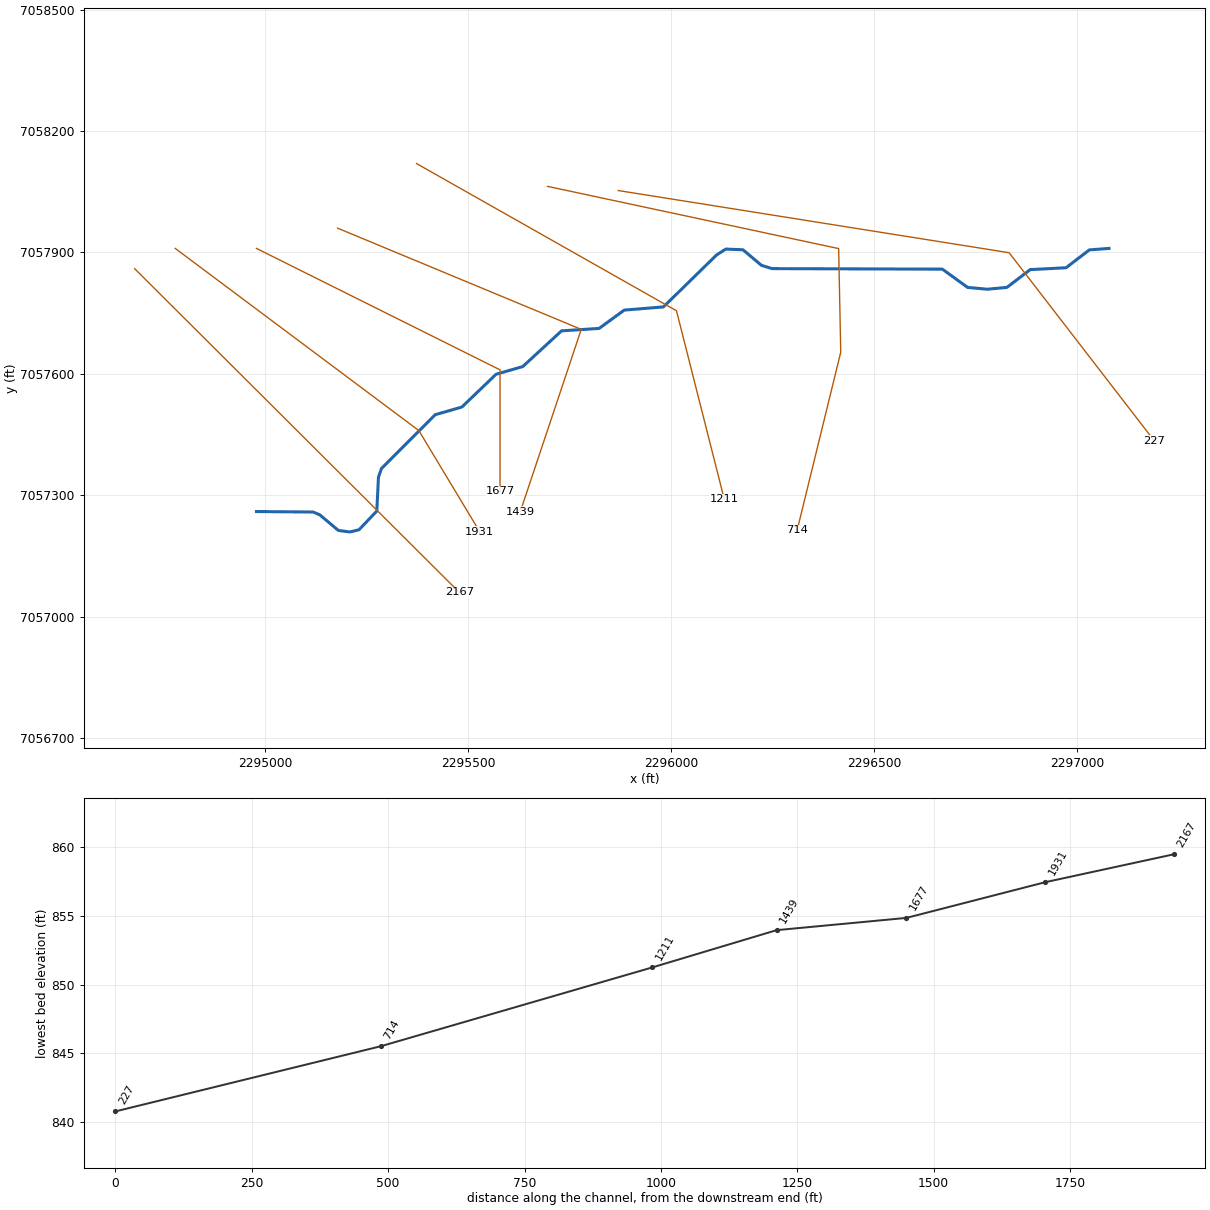
--- S88.prj (project) ---

Proj Title=S88 Base Level Engineering
Current Plan=p01
Default Exp/Contr=0.3,0.1
English Units
Geom File=g01
Flow File=f01
Plan File=p01
BEGIN DESCRIPTION:
S88
END DESCRIPTION:

--- S88.p01 (plan) ---

Plan Title=Multiple Run
Short Identifier=Multiple
Geom File=g01
Flow File=f01
Subcritical Flow
K Sum by GR= 0
Std Step Tol= 0.01
Critical Tol= 0.01
Num of Std Step Trials= 20
Max Error Tol= 0.3
Flow Tol Ratio= 0.001
Split Flow NTrial= 30
Split Flow Tol= 0.02
Split Flow Ratio= 0.02
Log Output Level= 0
Friction Slope Method= 1
Unsteady Friction Slope Method= 2
Unsteady Bridges Friction Slope Method= 1
Parabolic Critical Depth
Global Vel Dist=  1 , 1 , 1
Global Log Level= 0
CheckData=True
Encroach Param= -1, 0, 0, 0
BEGIN DESCRIPTION:
Multiple Run
END DESCRIPTION:

--- S88.f01 (steady flow) ---

Flow Title=Multiple
Number of Profiles=7
Profile Names=10-year,25-year,50-year,1pct_min,100-year,1pct_plu,500-year
River Rch & RM= S88,Reach-1,2167
     244     318     376     222     443     883     613
Boundary for River Rch & Prof#=S88,Reach-1,1
Up Type=0
Dn Type=3
Dn Slope=0.005
Boundary for River Rch & Prof#=S88,Reach-1,2
Up Type=0
Dn Type=3
Dn Slope=0.005
Boundary for River Rch & Prof#=S88,Reach-1,3
Up Type=0
Dn Type=3
Dn Slope=0.005
Boundary for River Rch & Prof#=S88,Reach-1,4
Up Type=0
Dn Type=3
Dn Slope=0.005
Boundary for River Rch & Prof#=S88,Reach-1,5
Up Type=0
Dn Type=3
Dn Slope=0.005
Boundary for River Rch & Prof#=S88,Reach-1,6
Up Type=0
Dn Type=3
Dn Slope=0.005
Boundary for River Rch & Prof#=S88,Reach-1,7
Up Type=0
Dn Type=3
Dn Slope=0.005

--- S88.g01 (geometry) ---

Geom Title=Existing Conditions

River Reach=S88,Reach-1
Reach XY= 30
      2294979.00      7057260.00      2295118.53      7057258.81
      2295135.08      7057251.82      2295180.78      7057213.32
      2295208.99      7057209.55      2295231.58      7057214.97
      2295275.47      7057261.22      2295279.53      7057344.78
      2295286.86      7057366.17      2295419.32      7057499.22
      2295485.04      7057518.18      2295569.33      7057599.20
      2295635.04      7057618.18      2295730.50      7057706.38
      2295823.02      7057712.36      2295884.98      7057757.64
      2295981.43      7057765.52      2296112.32      7057893.78
      2296135.03      7057908.38      2296177.25      7057906.66
      2296222.92      7057868.19      2296249.03      7057860.09
      2296668.50      7057858.78      2296730.60      7057813.70
      2296779.00      7057809.18      2296827.40      7057813.70
      2296884.97      7057857.65      2296973.08      7057862.23
      2297030.51      7057906.36      2297079.00      7057910.00

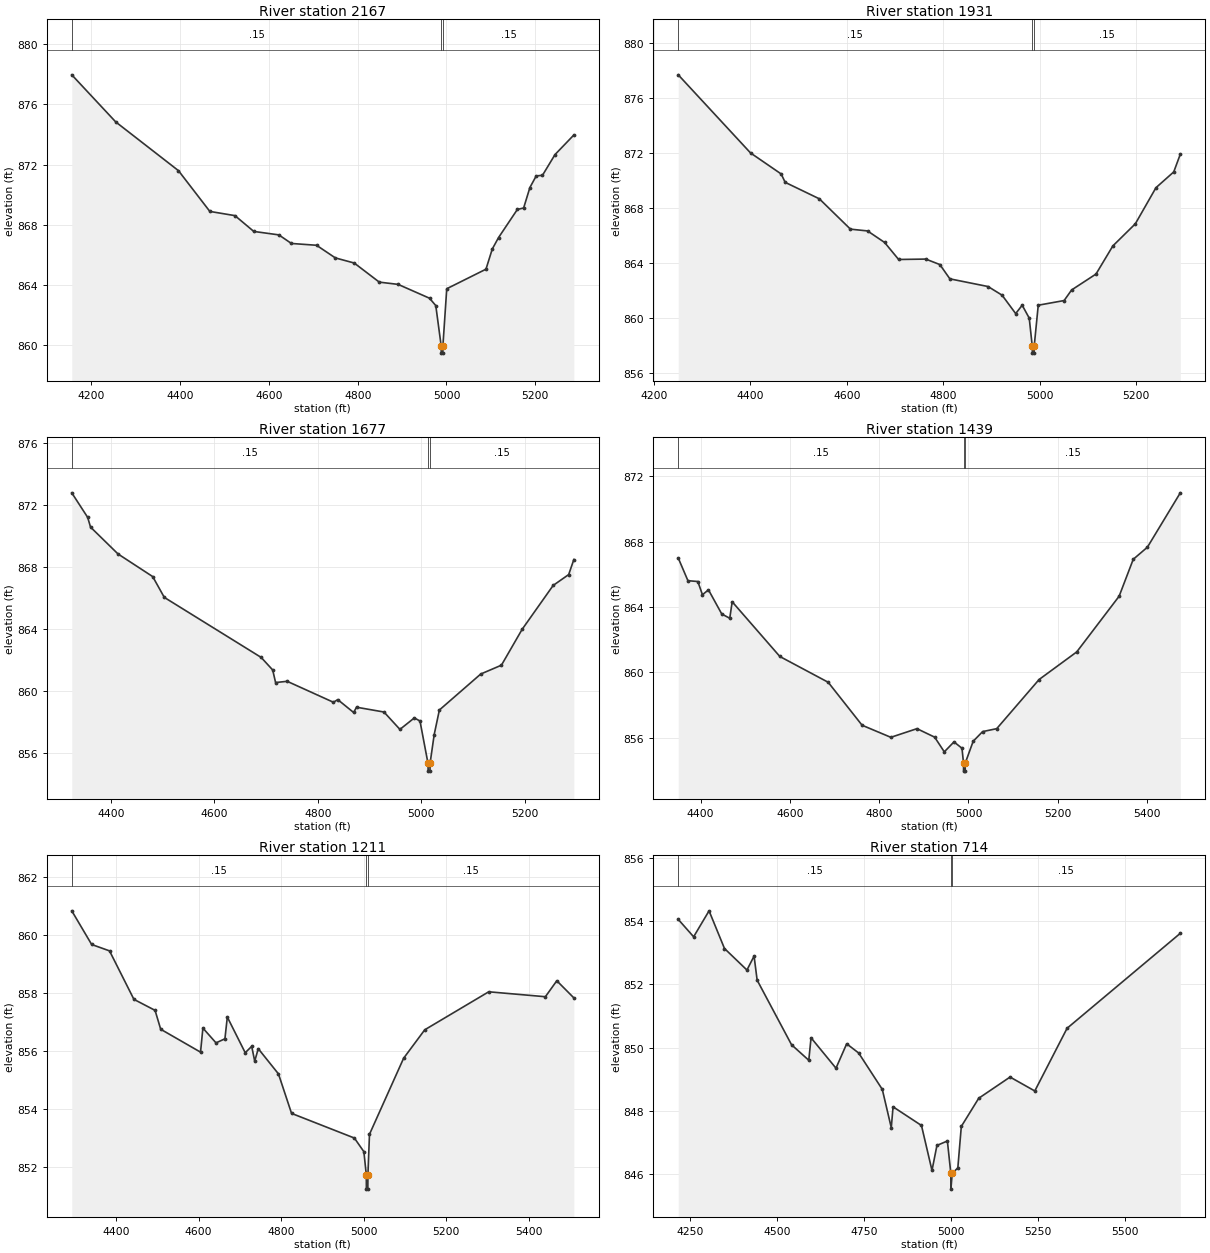
Type RM Length L Ch R = 1,2167,236,236,236
BEGIN DESCRIPTION:
S88 4.0
END DESCRIPTION:
XS GIS Cut Line= 3
      2294679.03      7057859.97      2295279.00      7057260.00
      2295478.98      7057060.02
#Sta/Elev= 30
  4155.7  877.97  4254.7  874.84  4396.1  871.60  4466.8  868.89  4523.4  868.61
  4565.8  867.56  4622.3  867.33  4650.6  866.76  4707.2  866.64  4749.6  865.80
  4792.1  865.46  4848.6  864.19  4891.0  864.04  4961.8  863.12  4975.9  862.63
  4988.0  859.97  4988.3  859.47  4991.8  859.47  4992.0  859.97  5000.6  863.75
  5089.0  865.05  5103.2  866.39  5117.3  867.15  5159.7  869.02  5173.9  869.12
  5188.0  870.48  5202.2  871.25  5216.3  871.29  5244.6  872.67  5287.0  873.97
#Mann=3,-1,0
  4155.7    0.15       0  4988.0    0.05       0  4992.0    0.15       0
Bank Sta=4988,4992
Exp/Cntr=0.3,0.1

Type RM Length L Ch R = 1,1931,254,254,254
BEGIN DESCRIPTION:
S88 3.0
END DESCRIPTION:
XS GIS Cut Line= 3
      2294779.04      7057909.97      2295379.00      7057460.00
      2295529.00      7057210.00
#Sta/Elev= 30
  4250.3  877.71  4400.3  872.02  4463.8  870.49  4472.1  869.88  4543.0  868.68
  4607.5  866.47  4643.0  866.34  4678.4  865.50  4707.5  864.26  4763.8  864.29
  4793.0  863.89  4813.8  862.85  4893.0  862.29  4922.1  861.66  4950.3  860.32
  4963.8  860.93  4978.4  859.99  4984.7  857.94  4985.0  857.44  4988.5  857.44
  4988.7  857.94  4997.1  860.93  5050.8  861.27  5066.3  862.04  5116.9  863.20
  5151.9  865.25  5198.5  866.86  5241.3  869.49  5278.2  870.64  5291.8  871.93
#Mann=3,-1,0
  4250.3    0.15       0  4984.7    0.05       0  4988.7    0.15       0
Bank Sta=4984.7,4988.7
Exp/Cntr=0.3,0.1

Type RM Length L Ch R = 1,1677,238,238,238
BEGIN DESCRIPTION:
S88 2.0
END DESCRIPTION:
XS GIS Cut Line= 3
      2294979.00      7057910.00      2295579.00      7057610.00
      2295579.00      7057310.02
#Sta/Elev= 30
  4324.4  872.79  4355.1  871.21  4360.7  870.58  4413.8  868.85  4480.9  867.39
  4503.3  866.05  4690.6  862.18  4712.9  861.37  4718.5  860.56  4740.9  860.64
  4830.3  859.29  4838.7  859.46  4869.4  858.63  4875.0  858.97  4928.1  858.66
  4958.9  857.54  4986.8  858.28  4997.7  858.08  5013.2  855.35  5013.5  854.85
  5017.0  854.85  5017.2  855.35  5025.2  857.21  5035.2  858.79  5115.2  861.11
  5155.2  861.68  5195.2  863.99  5255.2  866.82  5285.2  867.52  5295.2  868.49
#Mann=3,-1,0
  4324.4    0.15       0  5013.2    0.05       0  5017.2    0.15       0
Bank Sta=5013.2,5017.2
Exp/Cntr=0.3,0.1

Type RM Length L Ch R = 1,1439,228,228,228
BEGIN DESCRIPTION:
S88 1.0
END DESCRIPTION:
XS GIS Cut Line= 3
      2295179.00      7057960.00      2295779.00      7057710.00
      2295629.01      7057260.04
#Sta/Elev= 30
  4350.1  867.01  4371.8  865.62  4394.0  865.57  4404.3  864.76  4417.8  865.06
  4447.6  863.58  4465.5  863.32  4470.9  864.33  4577.6  860.98  4685.9  859.40
  4761.8  856.77  4826.2  856.03  4884.7  856.56  4924.3  856.04  4945.9  855.14
  4967.6  855.75  4985.5  855.36  4988.9  854.46  4989.1  853.96  4992.6  853.96
  4992.9  854.46  5010.6  855.79  5031.7  856.38  5063.3  856.56  5158.2  859.57
  5242.5  861.26  5337.4  864.67  5369.0  866.93  5400.7  867.67  5474.4  871.00
#Mann=3,-1,0
  4350.1    0.15       0  4988.9    0.05       0  4992.9    0.15       0
Bank Sta=4988.9,4992.9
Exp/Cntr=0.3,0.1

Type RM Length L Ch R = 1,1211,497,497,497
BEGIN DESCRIPTION:
1069
END DESCRIPTION:
XS GIS Cut Line= 3
      2295373.42      7058119.59      2296013.59      7057755.97
      2296131.37      7057289.95
#Sta/Elev= 30
  4292.7  860.84  4340.9  859.68  4384.2  859.46  4443.3  857.79  4494.6  857.41
  4508.2  856.76  4604.8  855.97  4610.5  856.80  4642.3  856.29  4663.9  856.43
  4669.7  857.18  4713.1  855.95  4728.8  856.17  4736.1  855.66  4744.7  856.09
  4793.7  855.22  4825.4  853.86  4977.7  853.01  5000.7  852.54  5006.5  851.75
  5006.8  851.25  5010.3  851.25  5010.5  851.75  5014.3  853.14  5097.0  855.76
  5148.2  856.74  5303.3  858.05  5440.6  857.88  5468.3  858.43  5509.6  857.84
#Mann=3,-1,0
  4292.7    0.15       0  5006.5    0.05       0  5010.5    0.15       0
Bank Sta=5006.5,5010.5
Exp/Cntr=0.3,0.1

Type RM Length L Ch R = 1,714,487,487,487
BEGIN DESCRIPTION:
1068
END DESCRIPTION:
XS GIS Cut Line= 4
      2295696.03      7058063.25      2296413.03      7057909.60
      2296418.15      7057653.55      2296310.83      7057214.05
#Sta/Elev= 30
  4217.1  854.05  4261.3  853.50  4305.6  854.32  4349.9  853.13  4414.4  852.45
  4434.9  852.89  4443.7  852.13  4542.5  850.09  4592.0  849.60  4598.5  850.31
  4670.1  849.35  4700.8  850.12  4735.2  849.83  4803.1  848.68  4828.9  847.47
  4834.0  848.13  4915.6  847.54  4945.8  846.12  4960.0  846.91  4990.0  847.05
  4999.9  846.03  5000.1  845.53  5003.9  846.03  5020.0  846.20  5030.0  847.51
  5080.0  848.40  5170.0  849.07  5241.0  848.63  5333.7  850.61  5658.9  853.61
#Mann=3,-1,0
  4217.1    0.15       0  4999.9    0.05       0  5003.9    0.15       0
Bank Sta=4999.9,5003.9
Exp/Cntr=0.3,0.1

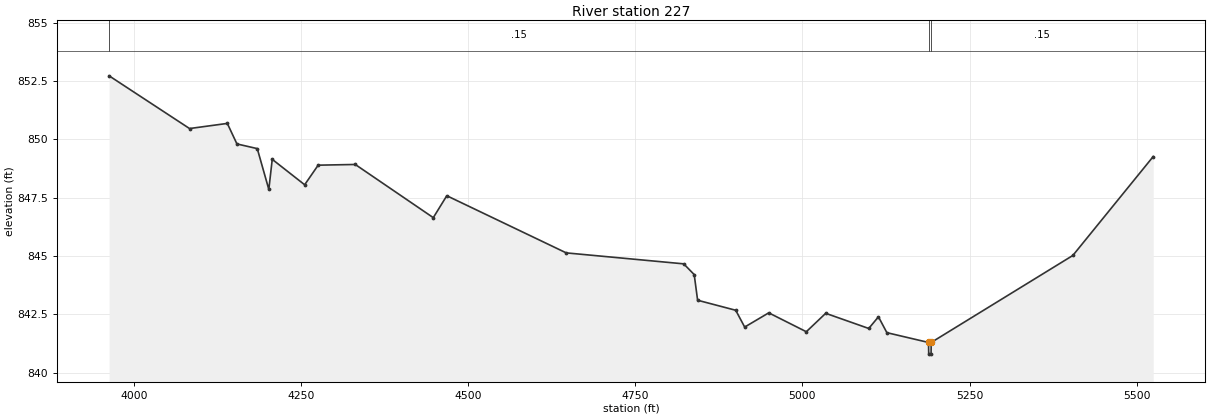
Type RM Length L Ch R = 1,227,0,0,0
BEGIN DESCRIPTION:
1065
END DESCRIPTION:
XS GIS Cut Line= 3
      2295870.20      7058052.99      2296832.97      7057899.36
      2297190.78      7057434.21
#Sta/Elev= 30
  3963.0  852.72  4083.3  850.46  4139.8  850.68  4154.2  849.80  4184.6  849.60
  4201.9  847.85  4207.0  849.14  4255.5  848.05  4275.7  848.89  4331.2  848.92
  4447.9  846.64  4468.1  847.58  4646.8  845.13  4822.5  844.66  4838.2  844.20
  4843.3  843.10  4900.3  842.67  4913.7  841.95  4949.7  842.56  5005.9  841.75
  5034.9  842.54  5099.3  841.89  5113.8  842.39  5126.4  841.71  5188.7  841.29
  5189.0  840.79  5192.5  840.79  5192.7  841.29  5404.6  845.02  5524.8  849.26
#Mann=3,-1,0
  3963.0    0.15       0  5188.7    0.05       0  5192.7    0.15       0
Bank Sta=5188.7,5192.7
Exp/Cntr=0.3,0.1

Chan Stop Cuts=-1