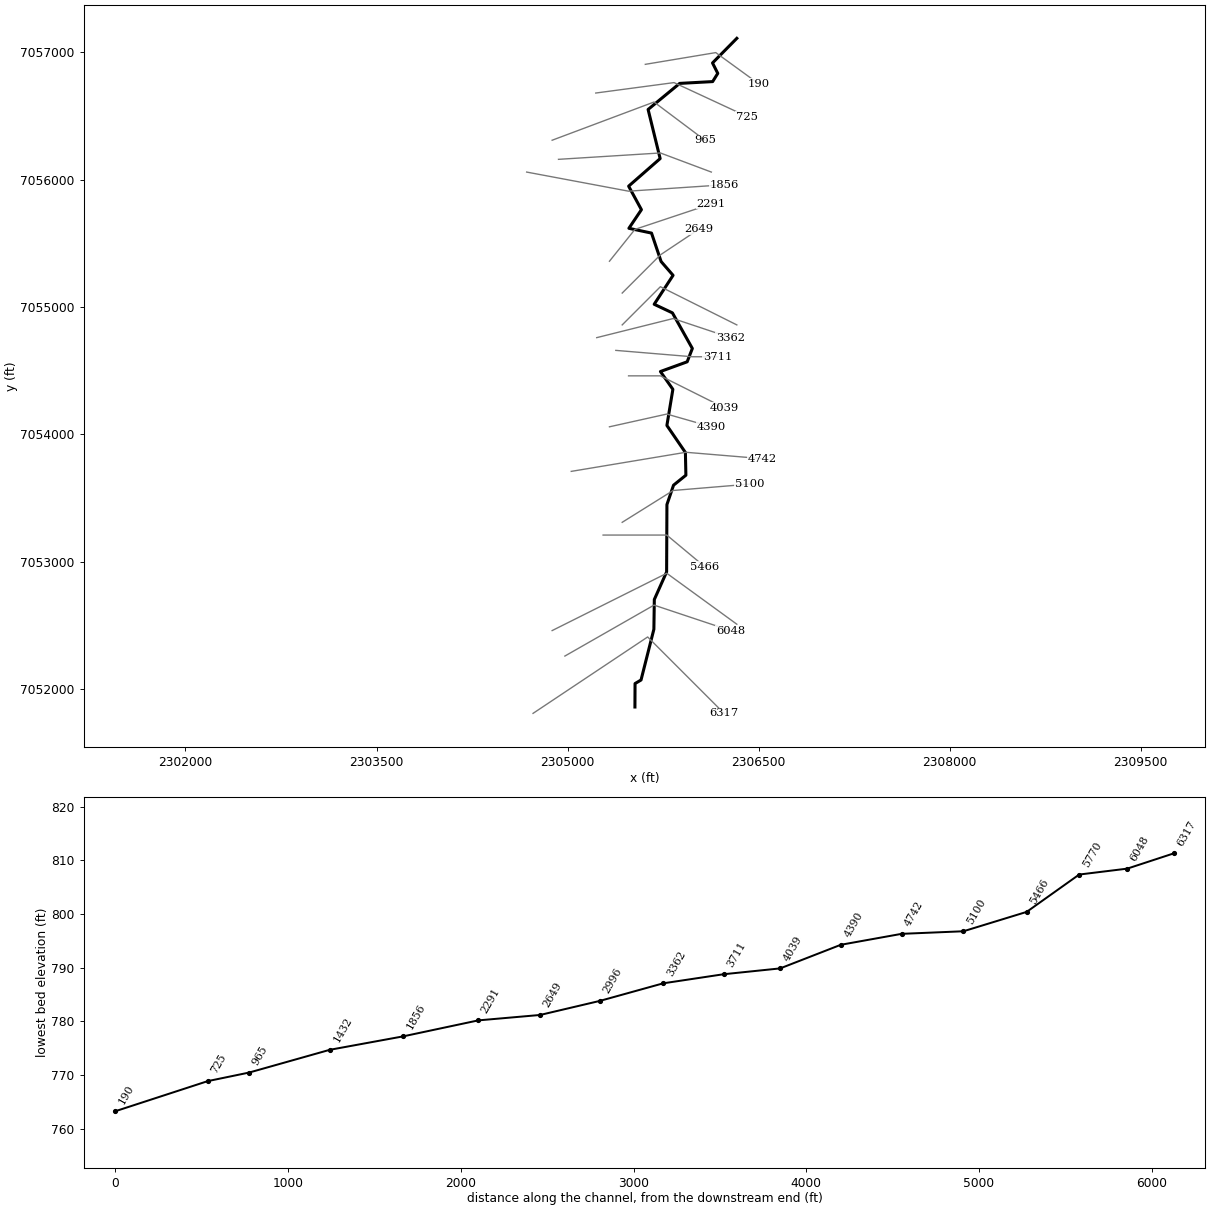
--- S90.prj (project) ---

Proj Title=S90 Base Level Engineering
Current Plan=p01
Default Exp/Contr=0.3,0.1
English Units
Geom File=g01
Flow File=f01
Plan File=p01
BEGIN DESCRIPTION:
S90
END DESCRIPTION:

--- S90.p01 (plan) ---

Plan Title=Multiple Run
Short Identifier=Multiple
Geom File=g01
Flow File=f01
Subcritical Flow
K Sum by GR= 0
Std Step Tol= 0.01
Critical Tol= 0.01
Num of Std Step Trials= 20
Max Error Tol= 0.3
Flow Tol Ratio= 0.001
Split Flow NTrial= 30
Split Flow Tol= 0.02
Split Flow Ratio= 0.02
Log Output Level= 0
Friction Slope Method= 1
Unsteady Friction Slope Method= 2
Unsteady Bridges Friction Slope Method= 1
Parabolic Critical Depth
Global Vel Dist=  1 , 1 , 1
Global Log Level= 0
CheckData=True
Encroach Param= -1, 0, 0, 0
BEGIN DESCRIPTION:
Multiple Run
END DESCRIPTION:

--- S90.f01 (steady flow) ---

Flow Title=Multiple
Number of Profiles=7
Profile Names=10-year,25-year,50-year,1pct_min,100-year,1pct_plu,500-year
River Rch & RM= S90,Reach-1,6317
     407     547     661     397     792    1580    1140
River Rch & RM= S90,Reach-1,5100
     591     808     988     599    1200    2390    1760
River Rch & RM= S90,Reach-1,1856
     666     921    1130     691    1380    2750    2050
Boundary for River Rch & Prof#=S90,Reach-1,1
Up Type=0
Dn Type=3
Dn Slope=0.005
Boundary for River Rch & Prof#=S90,Reach-1,2
Up Type=0
Dn Type=3
Dn Slope=0.005
Boundary for River Rch & Prof#=S90,Reach-1,3
Up Type=0
Dn Type=3
Dn Slope=0.005
Boundary for River Rch & Prof#=S90,Reach-1,4
Up Type=0
Dn Type=3
Dn Slope=0.005
Boundary for River Rch & Prof#=S90,Reach-1,5
Up Type=0
Dn Type=3
Dn Slope=0.005
Boundary for River Rch & Prof#=S90,Reach-1,6
Up Type=0
Dn Type=3
Dn Slope=0.005
Boundary for River Rch & Prof#=S90,Reach-1,7
Up Type=0
Dn Type=3
Dn Slope=0.005

--- S90.g01 (geometry) ---

Geom Title=Existing Conditions

River Reach=S90,Reach-1
Reach XY= 30
      2305529.00      7051860.00      2305529.94      7052044.06
      2305576.92      7052072.01      2305677.78      7052470.50
      2305681.26      7052704.06      2305777.78      7052920.50
      2305780.22      7053449.50      2305832.19      7053601.65
      2305929.07      7053679.89      2305925.25      7053858.45
      2305779.94      7054070.48      2305826.94      7054354.14
      2305729.17      7054493.98      2305939.17      7054570.36
      2305979.79      7054675.06      2305823.42      7054954.42
      2305680.16      7055022.00      2305828.46      7055249.31
      2305734.54      7055357.58      2305659.22      7055580.99
      2305481.58      7055618.48      2305580.00      7055764.71
      2305479.55      7055949.37      2305726.96      7056165.85
      2305632.39      7056551.56      2305880.55      7056756.25
      2306139.24      7056770.34      2306179.44      7056834.91
      2306138.15      7056916.73      2306329.00      7057110.00

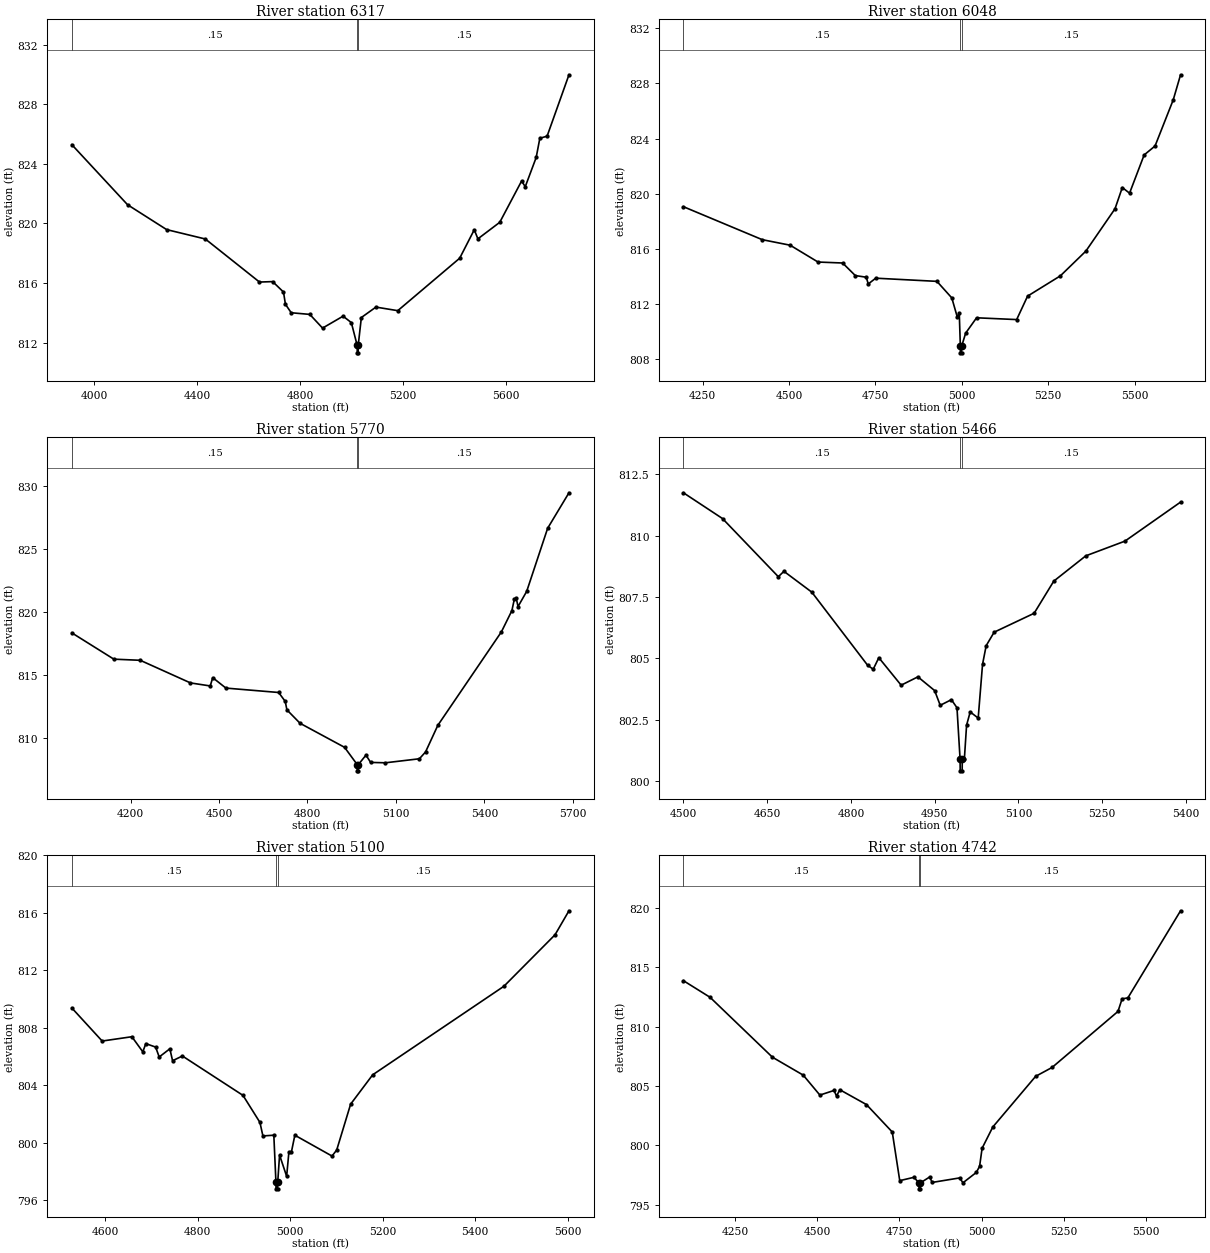
Type RM Length L Ch R = 1,6317,269,269,269
BEGIN DESCRIPTION:
S90 16.0
END DESCRIPTION:
XS GIS Cut Line= 3
      2304729.00      7051810.00      2305629.00      7052410.00
      2306229.01      7051809.99
#Sta/Elev= 30
  3913.8  825.29  4130.1  821.26  4281.9  819.59  4432.1  818.96  4642.4  816.07
  4693.5  816.10  4735.6  815.40  4743.1  814.58  4765.6  814.01  4837.7  813.90
  4887.3  812.98  4966.9  813.78  4999.0  813.35  5021.7  811.82  5022.0  811.32
  5025.5  811.32  5025.7  811.82  5037.9  813.69  5094.5  814.39  5179.3  814.15
  5419.7  817.67  5476.3  819.58  5490.4  818.97  5575.3  820.08  5660.1  822.85
  5674.3  822.47  5716.7  824.43  5730.9  825.72  5759.1  825.86  5844.0  829.98
#Mann=3,-1,0
  3913.8    0.15       0  5021.7    0.05       0  5025.7    0.15       0
Bank Sta=5021.7,5025.7
Exp/Cntr=0.3,0.1

Type RM Length L Ch R = 1,6048,278,278,278
BEGIN DESCRIPTION:
S90 15.0
END DESCRIPTION:
XS GIS Cut Line= 3
      2304978.97      7052259.98      2305679.00      7052660.00
      2306278.99      7052460.00
#Sta/Elev= 30
  4194.2  819.07  4422.4  816.68  4503.0  816.28  4583.7  815.06  4654.9  814.99
  4691.6  814.08  4723.3  813.96  4729.1  813.47  4750.7  813.89  4927.8  813.66
  4970.9  812.46  4986.8  811.07  4992.5  811.36  4995.6  808.98  4995.8  808.48
  4999.3  808.48  4999.6  808.98  5011.0  809.91  5042.6  811.02  5158.6  810.89
  5190.2  812.59  5285.1  814.06  5358.8  815.85  5443.2  818.92  5464.3  820.46
  5485.3  820.05  5527.5  822.82  5559.1  823.47  5611.8  826.82  5632.9  828.63
#Mann=3,-1,0
  4194.2    0.15       0  4995.6    0.05       0  4999.6    0.15       0
Bank Sta=4995.6,4999.6
Exp/Cntr=0.3,0.1

Type RM Length L Ch R = 1,5770,304,304,304
BEGIN DESCRIPTION:
S90 14.0
END DESCRIPTION:
XS GIS Cut Line= 3
      2304879.04      7052460.02      2305779.00      7052910.00
      2306329.03      7052509.98
#Sta/Elev= 30
  4000.8  818.35  4143.3  816.26  4232.8  816.17  4403.3  814.37  4470.3  814.13
  4478.7  814.79  4523.4  813.96  4702.3  813.61  4724.7  812.90  4730.3  812.23
  4775.0  811.16  4925.9  809.25  4968.7  807.88  4968.9  807.38  4972.4  807.38
  4972.7  807.88  4998.6  808.63  5014.3  808.05  5064.6  808.02  5179.7  808.34
  5200.6  808.88  5242.3  811.00  5457.9  818.43  5493.5  820.12  5501.6  821.01
  5508.2  821.12  5514.3  820.44  5543.7  821.65  5614.8  826.67  5687.1  829.49
#Mann=3,-1,0
  4000.8    0.15       0  4968.7    0.05       0  4972.7    0.15       0
Bank Sta=4968.7,4972.7
Exp/Cntr=0.3,0.1

Type RM Length L Ch R = 1,5466,366,366,366
BEGIN DESCRIPTION:
S90 13.0
END DESCRIPTION:
XS GIS Cut Line= 3
      2305278.99      7053210.00      2305779.00      7053210.00
      2306078.98      7052960.02
#Sta/Elev= 30
  4500.0  811.75  4570.0  810.70  4670.0  808.33  4680.0  808.55  4730.0  807.70
  4830.0  804.72  4840.0  804.56  4850.0  805.03  4890.0  803.91  4920.0  804.25
  4950.0  803.69  4960.0  803.09  4980.0  803.32  4990.0  802.99  4995.5  800.92
  4995.8  800.42  4999.3  800.42  4999.5  800.92  5003.3  800.92  5007.2  802.28
  5013.7  802.82  5028.0  802.57  5035.8  804.76  5042.3  805.52  5056.6  806.07
  5128.2  806.84  5163.4  808.15  5220.7  809.18  5290.9  809.78  5390.5  811.37
#Mann=3,-1,0
  4500.0    0.15       0  4995.5    0.05       0  4999.5    0.15       0
Bank Sta=4995.5,4999.5
Exp/Cntr=0.3,0.1

Type RM Length L Ch R = 1,5100,358,358,358
BEGIN DESCRIPTION:
S90 12.0
END DESCRIPTION:
XS GIS Cut Line= 3
      2305429.00      7053310.00      2305829.00      7053560.00
      2306429.02      7053610.00
#Sta/Elev= 30
  4528.5  809.39  4594.0  807.09  4658.2  807.39  4681.8  806.34  4688.3  806.91
  4709.5  806.67  4717.2  805.98  4740.2  806.55  4746.1  805.72  4767.3  806.05
  4898.2  803.31  4934.8  801.43  4941.2  800.49  4964.8  800.54  4969.3  797.31
  4969.6  796.81  4973.1  796.81  4973.3  797.31  4977.2  799.16  4992.5  797.68
  4997.3  799.36  5002.7  799.36  5010.2  800.54  5090.5  799.09  5100.6  799.51
  5130.7  802.70  5178.3  804.74  5461.8  810.90  5572.2  814.48  5602.3  816.15
#Mann=3,-1,0
  4528.5    0.15       0  4969.3    0.05       0  4973.3    0.15       0
Bank Sta=4969.3,4973.3
Exp/Cntr=0.3,0.1

Type RM Length L Ch R = 1,4742,352,352,352
BEGIN DESCRIPTION:
S90 11.0
END DESCRIPTION:
XS GIS Cut Line= 3
      2305028.98      7053710.00      2305929.00      7053860.00
      2306528.98      7053810.00
#Sta/Elev= 30
  4091.8  813.87  4172.9  812.47  4363.0  807.42  4456.8  805.91  4507.5  804.23
  4550.6  804.62  4558.2  804.15  4568.3  804.68  4649.4  803.43  4728.0  801.12
  4750.8  797.02  4793.9  797.30  4809.6  796.83  4809.9  796.33  4813.4  796.33
  4813.6  796.83  4842.0  797.33  4849.6  796.87  4933.3  797.25  4943.4  796.84
  4984.0  797.71  4994.1  798.23  5001.7  799.75  5034.3  801.54  5164.8  805.81
  5215.0  806.56  5415.7  811.28  5428.2  812.34  5445.8  812.42  5606.3  819.76
#Mann=3,-1,0
  4091.8    0.15       0  4809.6    0.05       0  4813.6    0.15       0
Bank Sta=4809.6,4813.6
Exp/Cntr=0.3,0.1

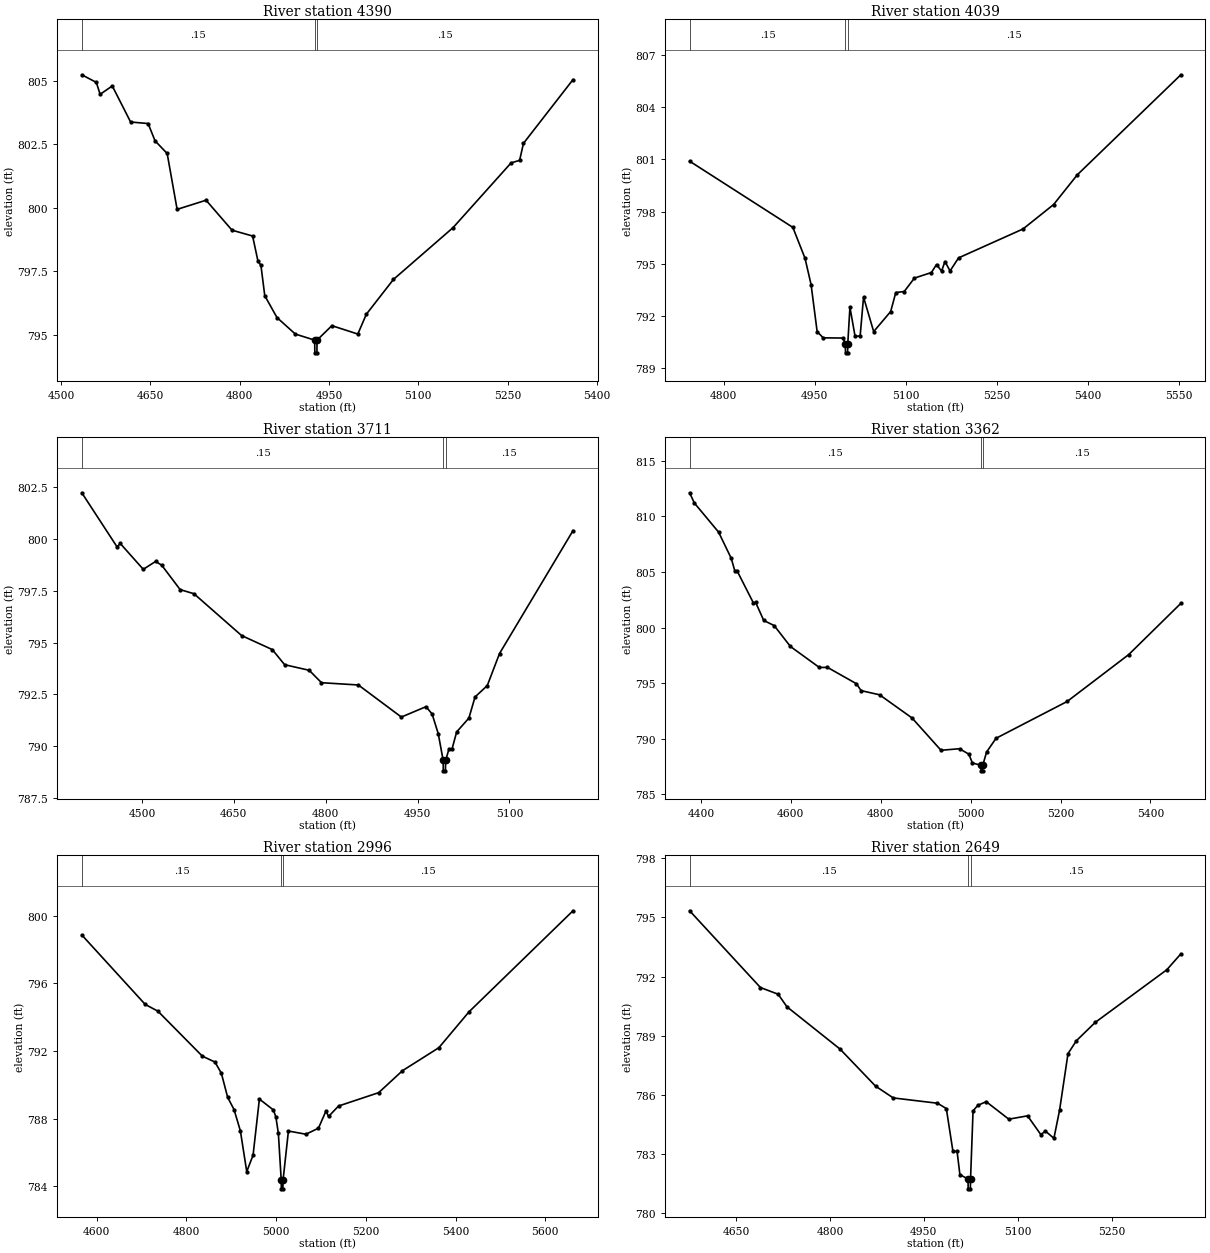
Type RM Length L Ch R = 1,4390,351,351,351
BEGIN DESCRIPTION:
S90 10.0
END DESCRIPTION:
XS GIS Cut Line= 3
      2305328.98      7054059.99      2305779.00      7054160.00
      2306128.99      7054060.00
#Sta/Elev= 30
  4534.9  805.24  4559.3  804.94  4565.7  804.47  4586.1  804.80  4616.9  803.38
  4646.3  803.32  4657.9  802.64  4678.3  802.14  4695.0  799.94  4743.6  800.30
  4787.2  799.12  4821.8  798.89  4830.7  797.91  4835.8  797.73  4842.2  796.54
  4862.7  795.68  4893.5  795.03  4926.0  794.79  4926.3  794.29  4929.8  794.29
  4930.0  794.79  4954.9  795.36  4998.5  795.03  5012.8  795.81  5058.3  797.18
  5158.4  799.22  5255.9  801.77  5270.2  801.87  5276.7  802.54  5359.9  805.05
#Mann=3,-1,0
  4534.9    0.15       0  4926.0    0.05       0  4930.0    0.15       0
Bank Sta=4926,4930
Exp/Cntr=0.3,0.1

Type RM Length L Ch R = 1,4039,328,328,328
BEGIN DESCRIPTION:
S90 9.0
END DESCRIPTION:
XS GIS Cut Line= 3
      2305478.97      7054460.00      2305729.00      7054460.00
      2306228.96      7054210.02
#Sta/Elev= 30
  4743.9  800.89  4913.9  797.09  4933.9  795.32  4943.9  793.81  4953.9  791.11
  4963.9  790.75  4996.7  790.74  5000.3  790.39  5000.6  789.89  5004.1  789.89
  5004.3  790.39  5007.9  792.51  5016.3  790.85  5024.7  790.85  5030.3  793.09
  5047.0  791.11  5075.0  792.26  5083.4  793.35  5097.3  793.41  5114.1  794.18
  5142.1  794.50  5150.5  794.96  5158.8  794.58  5164.4  795.13  5172.8  794.59
  5186.8  795.34  5293.0  797.00  5343.3  798.40  5382.4  800.11  5552.9  805.85
#Mann=3,-1,0
  4743.9    0.15       0  5000.3    0.05       0  5004.3    0.15       0
Bank Sta=5000.3,5004.3
Exp/Cntr=0.3,0.1

Type RM Length L Ch R = 1,3711,349,349,349
BEGIN DESCRIPTION:
S90 8.0
END DESCRIPTION:
XS GIS Cut Line= 3
      2305378.96      7054660.00      2305979.00      7054610.00
      2306178.98      7054610.00
#Sta/Elev= 30
  4401.7  802.24  4459.4  799.62  4464.5  799.79  4502.1  798.54  4522.2  798.92
  4532.2  798.74  4562.3  797.56  4584.9  797.36  4662.6  795.34  4712.8  794.66
  4732.9  793.93  4773.0  793.66  4793.1  793.06  4853.3  792.95  4923.5  791.40
  4963.7  791.90  4973.7  791.55  4983.8  790.59  4991.8  789.30  4992.0  788.80
  4995.5  788.80  4995.8  789.30  5001.3  789.86  5006.3  789.86  5013.8  790.68
  5033.8  791.35  5043.8  792.37  5063.8  792.92  5083.8  794.47  5203.8  800.41
#Mann=3,-1,0
  4401.7    0.15       0  4991.8    0.05       0  4995.8    0.15       0
Bank Sta=4991.8,4995.8
Exp/Cntr=0.3,0.1

Type RM Length L Ch R = 1,3362,366,366,366
BEGIN DESCRIPTION:
S90 7.0
END DESCRIPTION:
XS GIS Cut Line= 3
      2305229.03      7054760.01      2305829.00      7054910.00
      2306279.02      7054759.99
#Sta/Elev= 30
  4374.8  812.13  4385.1  811.22  4439.2  808.59  4467.5  806.22  4475.3  805.10
  4480.4  805.10  4516.5  802.23  4521.7  802.26  4539.7  800.64  4562.9  800.18
  4599.0  798.30  4663.4  796.41  4681.4  796.42  4745.8  794.95  4756.2  794.33
  4797.4  793.95  4869.5  791.87  4934.0  788.96  4975.2  789.10  4995.9  788.61
  5003.8  787.82  5022.9  787.61  5023.1  787.11  5026.6  787.11  5026.9  787.61
  5035.4  788.80  5056.5  790.04  5214.6  793.35  5351.6  797.57  5467.6  802.18
#Mann=3,-1,0
  4374.8    0.15       0  5022.9    0.05       0  5026.9    0.15       0
Bank Sta=5022.9,5026.9
Exp/Cntr=0.3,0.1

Type RM Length L Ch R = 1,2996,347,347,347
BEGIN DESCRIPTION:
S90 6.0
END DESCRIPTION:
XS GIS Cut Line= 3
      2305429.03      7054860.03      2305729.00      7055160.00
      2306328.96      7054860.02
#Sta/Elev= 30
  4566.9  798.86  4708.3  794.75  4736.6  794.35  4835.6  791.69  4863.8  791.34
  4878.0  790.68  4892.1  789.25  4906.3  788.53  4920.4  787.27  4934.6  784.86
  4948.7  785.83  4962.8  789.15  4993.9  788.51  4999.5  788.10  5005.1  787.12
  5011.5  784.34  5011.7  783.84  5015.2  783.84  5015.5  784.34  5027.5  787.26
  5066.6  787.07  5094.5  787.43  5111.3  788.45  5116.9  788.12  5139.3  788.74
  5228.7  789.53  5281.8  790.83  5362.9  792.19  5430.0  794.31  5661.9  800.29
#Mann=3,-1,0
  4566.9    0.15       0  5011.5    0.05       0  5015.5    0.15       0
Bank Sta=5011.5,5015.5
Exp/Cntr=0.3,0.1

Type RM Length L Ch R = 1,2649,358,358,358
BEGIN DESCRIPTION:
S90 5.0
END DESCRIPTION:
XS GIS Cut Line= 3
      2305429.01      7055110.01      2305729.00      7055410.00
      2306029.00      7055610.00
#Sta/Elev= 30
  4575.8  795.34  4688.9  791.44  4717.2  791.10  4731.3  790.46  4816.2  788.31
  4872.8  786.43  4901.1  785.83  4971.8  785.56  4985.9  785.29  4996.5  783.11
  5003.1  783.11  5007.6  781.93  5020.6  781.71  5020.8  781.21  5024.3  781.21
  5024.6  781.71  5028.6  785.17  5036.1  785.45  5049.6  785.64  5085.7  784.75
  5115.7  784.92  5136.8  783.97  5144.3  784.14  5157.8  783.78  5166.8  785.20
  5180.3  788.08  5193.8  788.74  5223.9  789.67  5338.1  792.34  5360.6  793.15
#Mann=3,-1,0
  4575.8    0.15       0  5020.6    0.05       0  5024.6    0.15       0
Bank Sta=5020.6,5024.6
Exp/Cntr=0.3,0.1

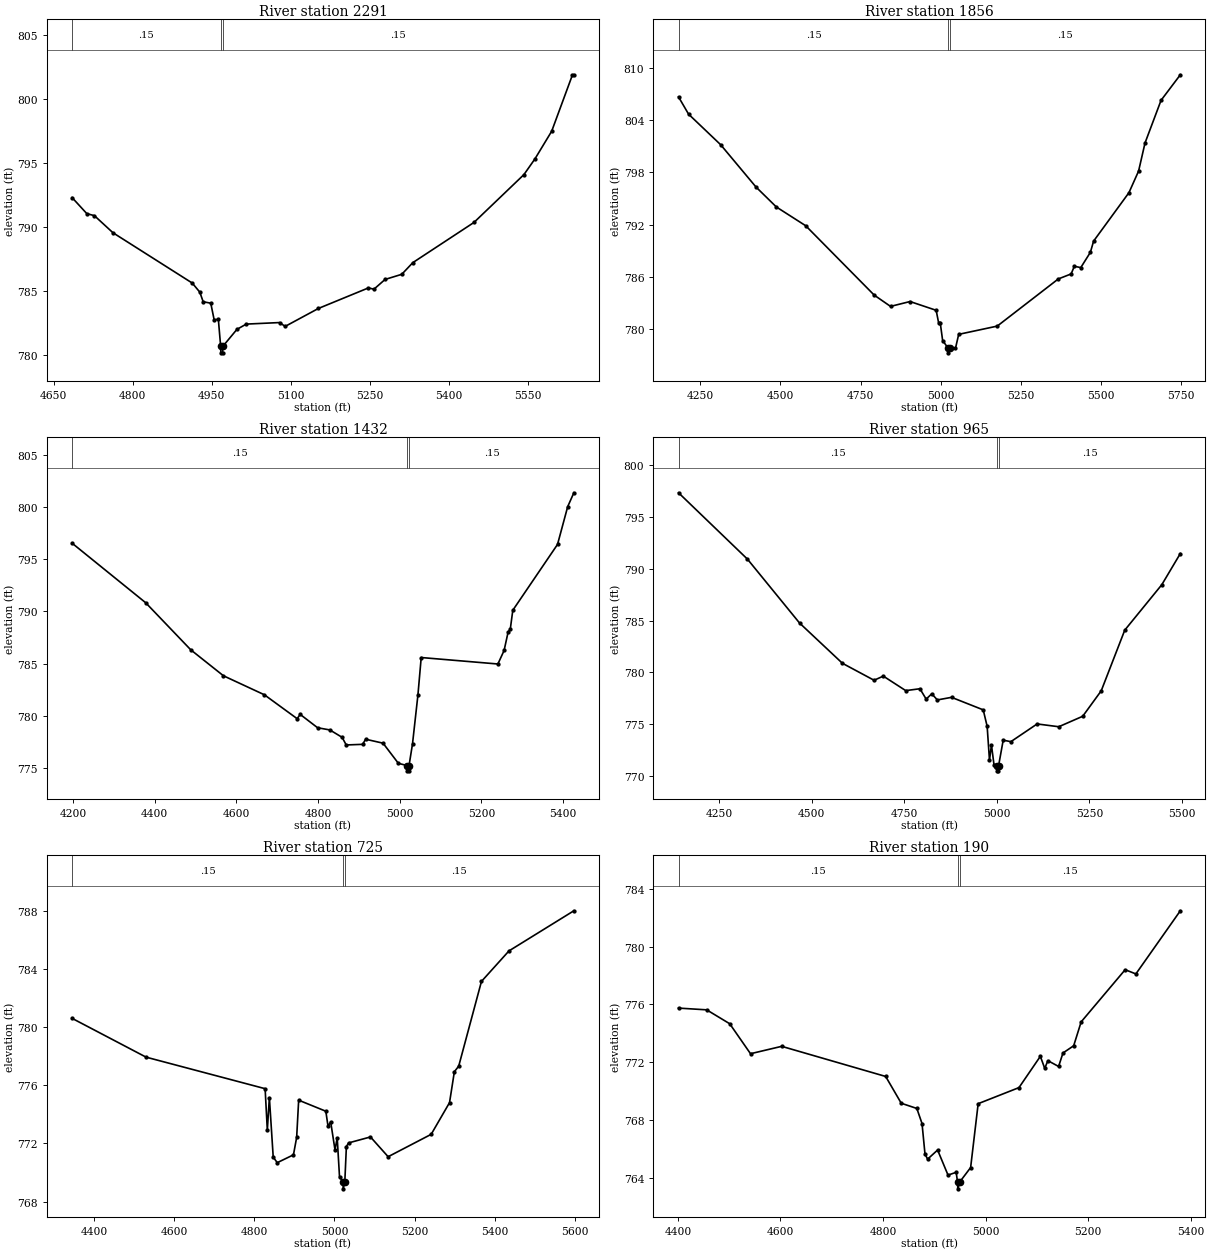
Type RM Length L Ch R = 1,2291,435,435,435
BEGIN DESCRIPTION:
S90 4.0
END DESCRIPTION:
XS GIS Cut Line= 3
      2305329.00      7055359.99      2305529.00      7055610.00
      2306128.98      7055809.99
#Sta/Elev= 30
  4685.2  792.30  4713.2  791.05  4727.6  790.89  4762.8  789.56  4913.3  785.64
  4927.7  784.93  4934.1  784.18  4948.5  784.07  4954.9  782.78  4962.9  782.81
  4967.3  780.70  4967.6  780.20  4971.1  780.20  4971.3  780.70  4998.2  782.03
  5015.9  782.44  5079.2  782.56  5089.7  782.26  5152.9  783.66  5247.8  785.26
  5258.3  785.16  5279.4  785.92  5311.1  786.32  5332.1  787.23  5448.1  790.36
  5543.0  794.09  5564.0  795.32  5595.7  797.47  5635.2  801.87  5637.8  801.87
#Mann=3,-1,0
  4685.2    0.15       0  4967.3    0.05       0  4971.3    0.15       0
Bank Sta=4967.3,4971.3
Exp/Cntr=0.3,0.1

Type RM Length L Ch R = 1,1856,424,424,424
BEGIN DESCRIPTION:
S90 3.0
END DESCRIPTION:
XS GIS Cut Line= 3
      2304678.96      7056060.01      2305479.00      7055910.00
      2306228.95      7055960.00
#Sta/Elev= 30
  4182.2  806.70  4213.6  804.71  4313.7  801.19  4423.9  796.32  4487.5  794.02
  4579.0  791.86  4792.7  783.87  4843.6  782.57  4904.6  783.13  4986.0  782.12
  4993.6  780.69  4998.7  780.69  5006.2  778.64  5024.1  777.72  5024.4  777.22
  5028.4  777.72  5046.3  777.75  5056.3  779.35  5176.6  780.30  5367.0  785.73
  5407.1  786.31  5417.1  787.19  5437.2  787.04  5467.2  788.80  5477.2  790.09
  5587.5  795.67  5617.6  798.16  5637.6  801.39  5687.7  806.31  5747.8  809.25
#Mann=3,-1,0
  4182.2    0.15       0  5024.1    0.05       0  5028.4    0.15       0
Bank Sta=5024.1,5028.4
Exp/Cntr=0.3,0.1

Type RM Length L Ch R = 1,1432,467,467,467
BEGIN DESCRIPTION:
S90 2.0
END DESCRIPTION:
XS GIS Cut Line= 3
      2304929.01      7056160.00      2305729.00      7056210.00
      2306128.95      7056060.02
#Sta/Elev= 30
  4197.9  796.54  4378.2  790.83  4488.5  786.32  4568.6  783.83  4668.8  782.01
  4749.0  779.72  4756.5  780.13  4799.1  778.85  4829.1  778.64  4859.2  777.93
  4869.2  777.20  4909.3  777.26  4916.8  777.75  4959.4  777.37  4996.9  775.44
  5018.7  775.22  5019.0  774.72  5022.6  774.72  5023.0  775.22  5031.5  777.30
  5044.8  782.00  5052.8  785.58  5240.6  784.96  5255.8  786.26  5265.6  788.02
  5270.9  788.29  5277.1  790.11  5386.6  796.42  5411.5  800.04  5426.6  801.37
#Mann=3,-1,0
  4197.9    0.15       0  5018.7    0.05       0  5023.0    0.15       0
Bank Sta=5018.7,5023
Exp/Cntr=0.3,0.1

Type RM Length L Ch R = 1,965,240,240,240
BEGIN DESCRIPTION:
S90 1.0
END DESCRIPTION:
XS GIS Cut Line= 3
      2304879.00      7056310.00      2305679.00      7056610.00
      2306079.00      7056310.00
#Sta/Elev= 30
  4140.9  797.34  4326.9  790.93  4467.5  784.76  4583.2  780.87  4668.7  779.23
  4693.6  779.63  4754.1  778.23  4792.4  778.41  4809.3  777.41  4824.4  777.92
  4839.5  777.33  4877.8  777.58  4963.3  776.37  4973.9  774.78  4980.2  771.50
  4985.5  772.98  4992.6  771.00  5000.4  770.98  5000.8  770.48  5004.4  770.48
  5004.8  770.98  5017.2  773.44  5038.0  773.30  5108.8  775.01  5167.2  774.74
  5231.8  775.75  5281.8  778.21  5345.3  784.07  5445.3  788.46  5495.3  791.47
#Mann=3,-1,0
  4140.9    0.15       0  5000.4    0.05       0  5004.8    0.15       0
Bank Sta=5000.4,5004.8
Exp/Cntr=0.3,0.1

Type RM Length L Ch R = 1,725,535,535,535
BEGIN DESCRIPTION:
1076
END DESCRIPTION:
XS GIS Cut Line= 3
      2305221.38      7056680.54      2305835.90      7056762.47
      2306409.44      7056496.19
#Sta/Elev= 30
  4345.1  780.61  4529.8  777.94  4826.9  775.77  4832.4  772.92  4837.5  775.16
  4847.1  771.06  4857.2  770.68  4897.6  771.22  4905.6  772.42  4910.6  774.98
  4978.4  774.22  4983.9  773.18  4990.5  773.49  5001.3  771.56  5006.8  772.39
  5012.6  769.69  5021.4  769.38  5021.8  768.88  5025.8  769.38  5029.7  771.79
  5035.2  772.04  5089.8  772.45  5133.9  771.09  5241.3  772.63  5287.1  774.81
  5299.2  776.94  5310.0  777.32  5366.8  783.15  5435.5  785.25  5597.4  788.01
#Mann=3,-1,0
  4345.1    0.15       0  5021.4    0.05       0  5025.8    0.15       0
Bank Sta=5021.4,5025.8
Exp/Cntr=0.3,0.1

Type RM Length L Ch R = 1,190,0,0,0
BEGIN DESCRIPTION:
1075
END DESCRIPTION:
XS GIS Cut Line= 3
      2305610.54      7056905.86      2306163.65      7056998.04
      2306501.67      7056752.22
#Sta/Elev= 30
  4401.2  775.75  4456.1  775.63  4501.0  774.67  4541.6  772.60  4602.4  773.11
  4805.2  771.03  4835.6  769.18  4866.0  768.82  4876.1  767.78  4881.9  765.67
  4887.0  765.32  4906.5  765.95  4926.8  764.22  4942.7  764.41  4945.3  763.77
  4945.9  763.27  4950.2  763.77  4970.9  764.74  4985.6  769.15  5065.2  770.26
  5106.9  772.42  5115.4  771.59  5121.6  772.12  5142.5  771.72  5151.0  772.65
  5171.9  773.15  5186.5  774.80  5272.3  778.40  5293.2  778.11  5379.9  782.47
#Mann=3,-1,0
  4401.2    0.15       0  4945.3    0.05       0  4950.2    0.15       0
Bank Sta=4945.3,4950.2
Exp/Cntr=0.3,0.1

Chan Stop Cuts=-1