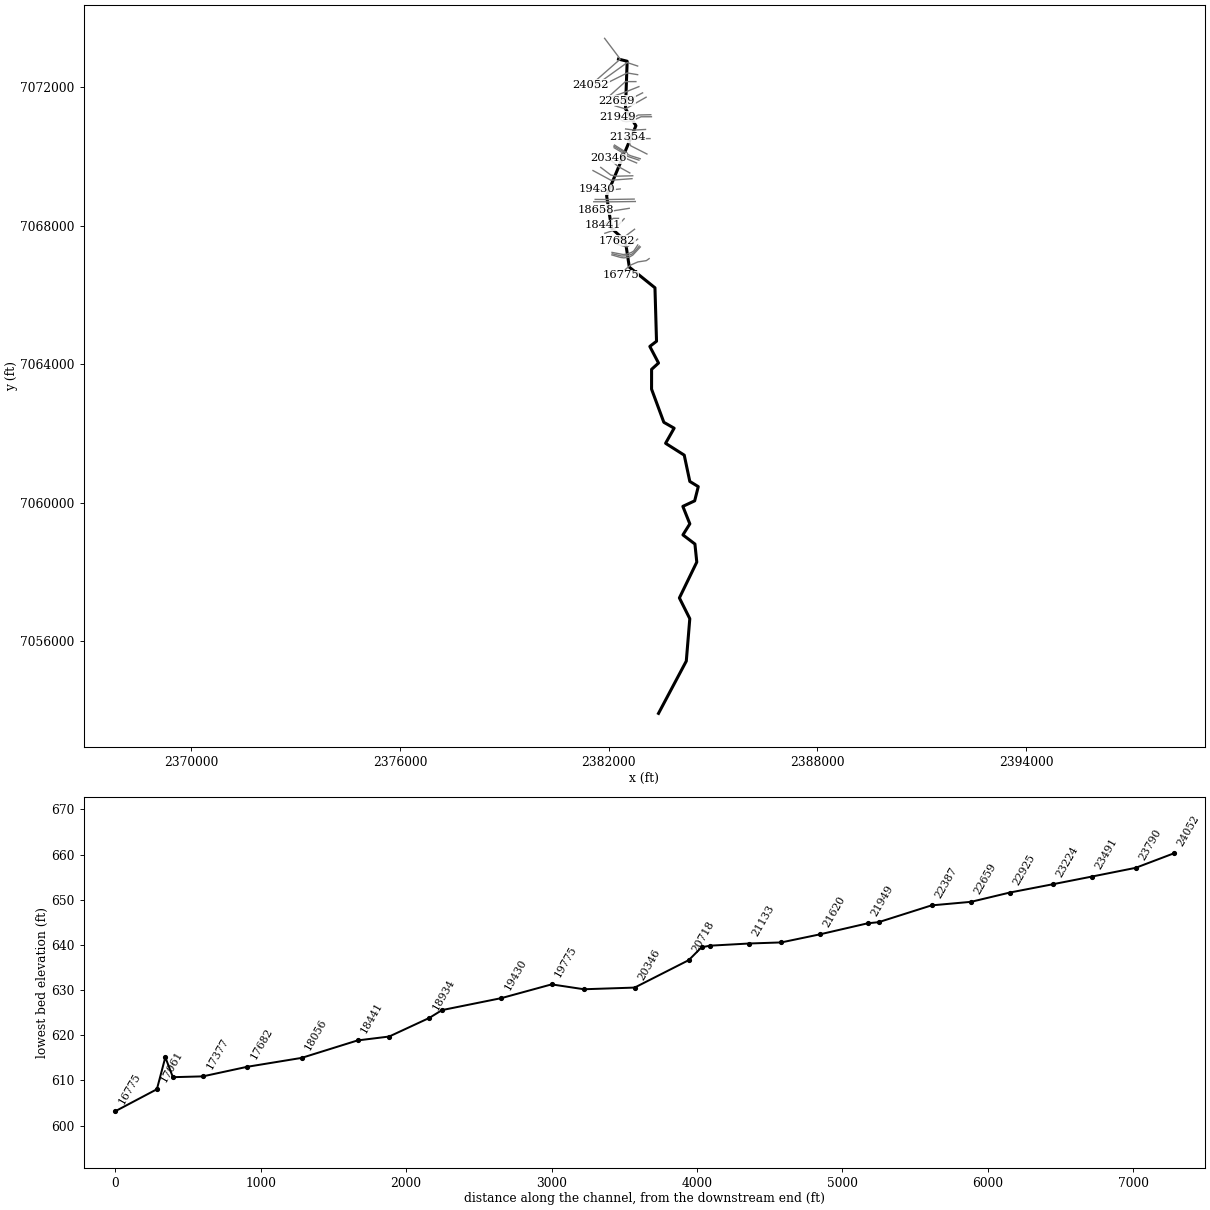
--- Sharps Branch.prj (project) ---

Proj Title=Sharps Branch Base Level Engineering
Current Plan=p01
Default Exp/Contr=0.3,0.1
English Units
Geom File=g01
Flow File=f01
Plan File=p01
Y Axis Title=Elevation
X Axis Title(PF)=Main Channel Distance
X Axis Title(XS)=Station
BEGIN DESCRIPTION:
Sharps Branch
END DESCRIPTION:
DSS Export Rating Curves= 0
DSS Export Rating Curve Sorted= 0
DSS Export Volume Flow Curves= 0
DXF OffsetX= 0
DXF OffsetY= 0
DXF ScaleX= 1
DXF ScaleY= 10

--- Sharps Branch.p01 (plan) ---

Plan Title=Multiple Run
Short Identifier=Multiple
Geom File=g01
Flow File=f01
Subcritical Flow
K Sum by GR= 0
Std Step Tol= 0.01
Critical Tol= 0.01
Num of Std Step Trials= 20
Max Error Tol= 0.3
Flow Tol Ratio= 0.001
Split Flow NTrial= 30
Split Flow Tol= 0.02
Split Flow Ratio= 0.02
Log Output Level= 0
Friction Slope Method= 1
Unsteady Friction Slope Method= 2
Unsteady Bridges Friction Slope Method= 1
Parabolic Critical Depth
Global Vel Dist=  1 , 1 , 1
Global Log Level= 0
CheckData=True
Encroach Param= -1, 0, 0, 0
BEGIN DESCRIPTION:
Multiple Run
END DESCRIPTION:

--- Sharps Branch.f01 (steady flow) ---

Flow Title=Multiple
Program Version=4.10
Number of Profiles= 7
Profile Names=10-year,25-year,50-year,1pct_min,100-year,1pct_plu,500-year
River Rch & RM=Sharps Branch,Reach-1         ,24052
     242     312     367     215     429     856     585
River Rch & RM=Sharps Branch,Reach-1         ,20865
     391     521     625     373     745    1486    1059
River Rch & RM=Sharps Branch,Reach-1         ,19430
     485     654     792     476     950    1896    1372
River Rch & RM=Sharps Branch,Reach-1         ,15769
     879    1229    1524     937    1870    3730    2822
River Rch & RM=Sharps Branch,Reach-1         ,13568
    1032    1455    1813    1120    2235    4459    3406
River Rch & RM=Sharps Branch,Reach-1         ,10835
    1066    1504    1876    1160    2314    4617    3530
River Rch & RM=Sharps Branch,Reach-1         ,8345
    1500    2147    2703    1685    3362    6708    5215
River Rch & RM=Sharps Branch,Reach-1         ,2728
    1577    2256    2839    1768    3528    7039    5465
Boundary for River Rch & Prof#=Sharps Branch,Reach-1         , 1
Up Type= 0
Dn Type= 3
Dn Slope=0.005
Boundary for River Rch & Prof#=Sharps Branch,Reach-1         , 2
Up Type= 0
Dn Type= 3
Dn Slope=0.005
Boundary for River Rch & Prof#=Sharps Branch,Reach-1         , 3
Up Type= 0
Dn Type= 3
Dn Slope=0.005
Boundary for River Rch & Prof#=Sharps Branch,Reach-1         , 4
Up Type= 0
Dn Type= 3
Dn Slope=0.005
Boundary for River Rch & Prof#=Sharps Branch,Reach-1         , 5
Up Type= 0
Dn Type= 3
Dn Slope=0.005
Boundary for River Rch & Prof#=Sharps Branch,Reach-1         , 6
Up Type= 0
Dn Type= 3
Dn Slope=0.005
Boundary for River Rch & Prof#=Sharps Branch,Reach-1         , 7
Up Type= 0
Dn Type= 3
Dn Slope=0.005
DSS Import GetInterval= 0
DSS Import GetPeak= 0
DSS Import FillOption= 0

--- Sharps Branch.g01 (geometry) ---

Geom Title=Existing Conditions
Program Version=4.10

River Reach=Sharps Branch   ,Reach-1
Reach XY= 30
        2382279.        7072810.      2382527.52      7072748.51
      2382479.15      7071375.21      2382779.23      7070884.93
      2381936.66      7068863.63       2382079.6      7067920.62
      2382475.19      7067558.45      2382589.59      7066799.95
      2383326.93      7066204.14      2383371.77      7064659.68
        2383179.        7064510.      2383429.37       7064030.2
      2383230.06      7063848.28      2383229.15      7063276.09
      2383582.08      7062318.31        2383878.      7062148.26
      2383632.12      7061711.62      2384168.53      7061369.82
        2384329.        7060610.      2384572.03      7060460.24
      2384468.72      7060049.84      2384128.49      7059889.77
      2384329.58        7059385.      2384130.97       7059065.9
      2384475.94      7058801.72      2384529.36      7058280.15
      2384029.38      7057244.84      2384328.62      7056644.84
      2384227.78       7055420.5        2383429.        7053910.

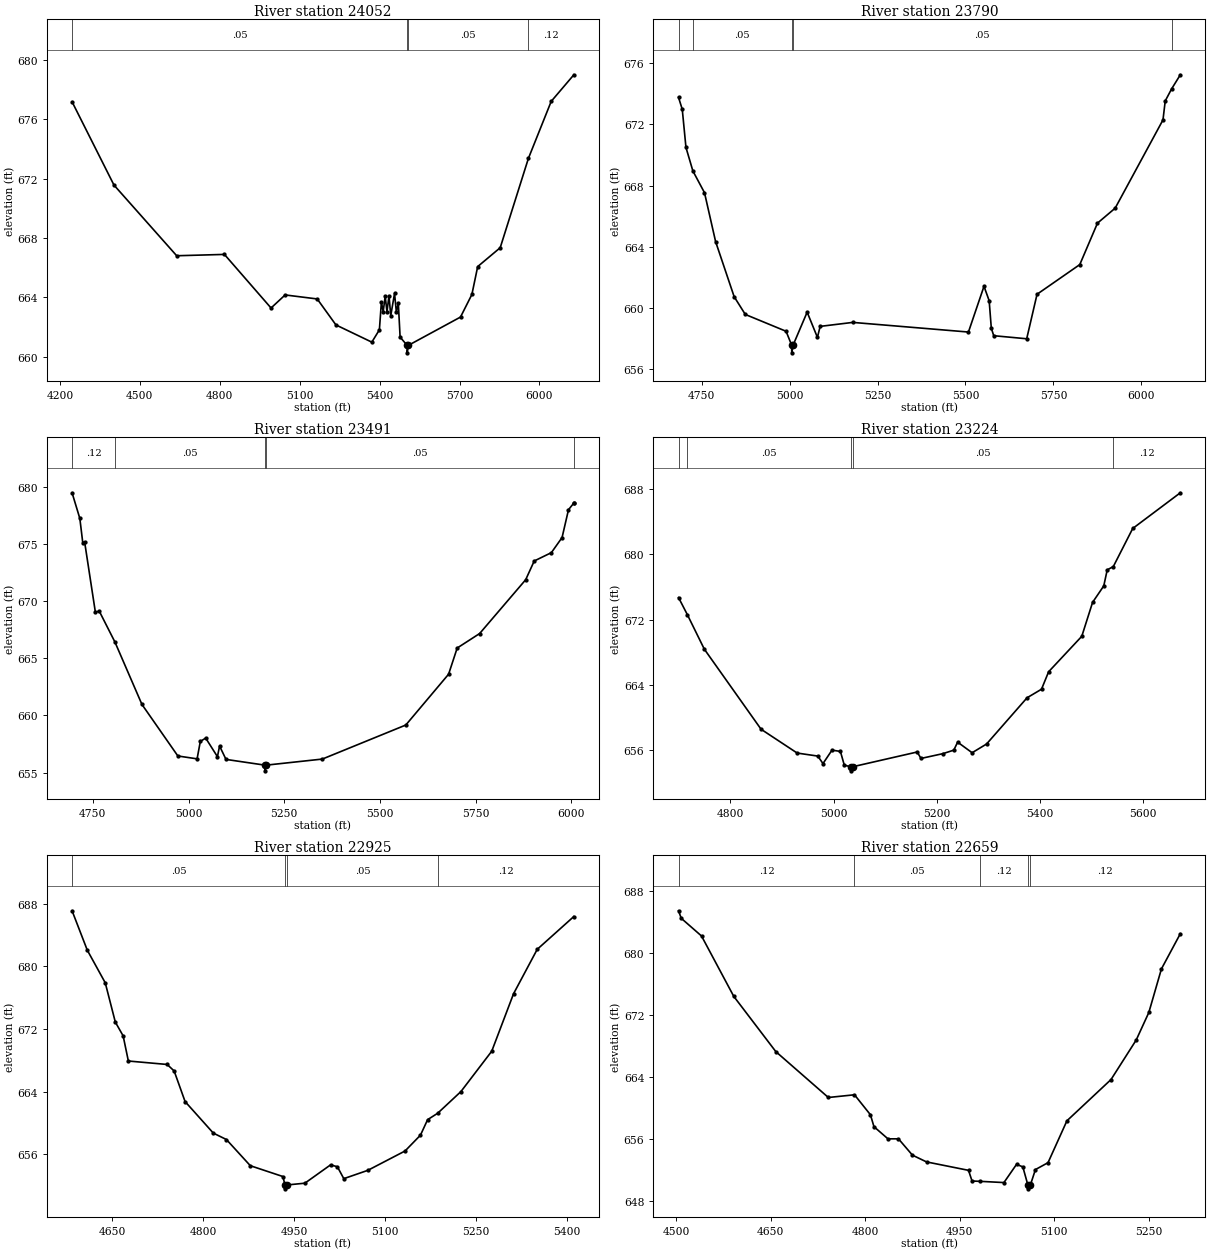
Type RM Length L Ch R = 1 ,24052   ,262,262,262
BEGIN DESCRIPTION:
Sharps Branch 61.0
END DESCRIPTION:
XS GIS Cut Line= 3
      2381879.01      7073409.98        2382329.        7072810.
      2381478.97      7072059.97
#Sta/Elev= 30
  4245.5  677.18  4402.8  671.57  4638.2  666.81  4817.4   666.9  4992.4  663.29
  5045.3  664.17  5165.7   663.9    5236  662.15  5370.7  660.99  5399.1  661.82
  5406.7   663.7  5413.3  663.04  5420.9  664.08  5427.6  663.03  5435.1  664.12
  5441.8  662.78    5456  664.27  5462.7  663.04  5470.2   663.6  5476.9  661.33
  5503.4  660.77  5503.6  660.27  5507.4  660.77  5703.6  662.68  5746.3   664.2
  5768.1  666.08  5852.6  667.35  5958.5  673.37  6044.1  677.21  6129.1     679
#Mann= 4 ,-1 , 0
  4245.5     .05       0  5503.4    .033       0  5507.4     .05       0
  5958.5     .12       0
Bank Sta=5503.4,5507.4
XS Rating Curve= 0 ,0
Exp/Cntr=0.3,0.1

Type RM Length L Ch R = 1 ,23790   ,299,299,299
BEGIN DESCRIPTION:
Sharps Branch 60.0
END DESCRIPTION:
XS GIS Cut Line= 3
      2382829.02      7072609.99        2382529.        7072710.
      2381629.02      7072060.01
#Sta/Elev= 30
  4684.4  673.77    4695  672.99  4705.5   670.5  4725.2  668.96  4758.2  667.54
  4789.8  664.34  4842.5  660.74  4874.2  659.58  4990.1  658.48    5006  657.57
  5006.2  657.07    5010  657.57    5050  659.73  5079.2  658.08    5087   658.8
  5179.7  659.06  5508.5  658.43  5552.7  661.42  5567.4  660.48  5573.5  658.68
  5580.4  658.19  5674.1  657.99  5703.5   660.9    5825  662.84  5875.3  665.55
  5925.6  666.53  6061.5   672.3  6067.9  673.54  6086.1  674.33  6110.8  675.25
#Mann= 5 ,-1 , 0
  4684.4     .12       0  4725.2     .05       0    5006    .033       0
    5010     .05       0  6086.1     .12       0
Bank Sta=5006,5010
XS Rating Curve= 0 ,0
Exp/Cntr=0.3,0.1

Type RM Length L Ch R = 1 ,23491   ,267,267,267
BEGIN DESCRIPTION:
Sharps Branch 59.0
END DESCRIPTION:
XS GIS Cut Line= 3
      2382828.99        7072360.        2382529.        7072410.
      2381628.97      7071959.98
#Sta/Elev= 30
  4695.9  679.49  4716.2  677.24  4723.8  675.13  4728.8  675.16  4756.7  669.05
  4766.9  669.13  4807.9  666.42  4878.4  660.96  4972.2  656.45  5022.4   656.2
  5030.8  657.72  5044.8  658.02  5075.5  656.39  5081.1  657.32  5097.9  656.15
  5199.3  655.65  5199.5  655.15  5203.3  655.65  5349.4  656.18  5567.4  659.16
  5679.2  663.61  5701.6   665.9  5760.3  667.17  5880.5  671.88  5902.8  673.52
  5947.6  674.25  5975.5  675.57  5992.3  678.01  6005.5  678.56  6006.3  678.56
#Mann= 5 ,-1 , 0
  4695.9     .12       0  4807.9     .05       0  5199.3    .033       0
  5203.3     .05       0  6005.5     .12       0
Bank Sta=5199.3,5203.3
XS Rating Curve= 0 ,0
Exp/Cntr=0.3,0.1

Type RM Length L Ch R = 1 ,23224   ,299,299,299
BEGIN DESCRIPTION:
Sharps Branch 58.0
END DESCRIPTION:
XS GIS Cut Line= 3
      2382778.99        7072160.        2382479.        7072160.
      2381978.98      7071709.98
#Sta/Elev= 30
  4699.5  674.71  4716.7   672.6  4749.5  668.38  4859.5  658.56  4929.5  655.64
  4969.5  655.27  4979.5  654.35    4997     656  5013.3  655.84  5020.8  654.16
    5033  653.96  5033.2  653.46    5037  653.96  5162.1  655.77  5169.5  654.98
  5212.1  655.57  5233.1     656  5240.5  656.98  5268.6  655.68  5296.6  656.75
  5375.1  662.42  5403.1  663.47  5416.9  665.61  5481.2  669.96  5502.1  674.12
  5523.8  676.14  5530.5  678.11  5542.3  678.51  5579.9  683.18  5672.2  687.56
#Mann= 5 ,-1 , 0
  4699.5     .12       0  4716.7     .05       0    5033    .033       0
    5037     .05       0  5542.3     .12       0
Bank Sta=5033,5037
XS Rating Curve= 0 ,0
Exp/Cntr=0.3,0.1

Type RM Length L Ch R = 1 ,22925   ,266,266,266
BEGIN DESCRIPTION:
Sharps Branch 57.0
END DESCRIPTION:
XS GIS Cut Line= 3
      2382865.14      7072015.21        2382479.        7071860.
      2382092.17      7071720.71
#Sta/Elev= 30
  4583.8  687.08  4608.9  682.05  4638.5  677.89  4655.1  672.88    4668  671.12
  4676.6  667.91  4740.6  667.47  4752.1  666.64  4770.1  662.74  4816.7  658.71
  4838.3  657.89  4877.7  654.55  4931.4  653.17  4934.8   652.1  4935.1   651.6
  4938.8   652.1  4967.6  652.32    5010  654.66  5021.2  654.42  5031.8   652.9
  5071.4  653.96  5132.8  656.43  5158.2  658.45    5170  660.43  5186.5  661.24
  5224.9  664.01  5275.7  669.16  5311.7   676.5  5350.7  682.16  5411.1  686.35
#Mann= 4 ,-1 , 0
  4583.8     .05       0  4934.8    .033       0  4938.8     .05       0
  5186.5     .12       0
Bank Sta=4934.8,4938.8
XS Rating Curve= 0 ,0
Exp/Cntr=0.3,0.1

Type RM Length L Ch R = 1 ,22659   ,272,272,272
BEGIN DESCRIPTION:
Sharps Branch 56.0
END DESCRIPTION:
XS GIS Cut Line= 3
      2382971.51       7071835.1        2382529.        7071610.
      2382228.97        7071610.
#Sta/Elev= 30
    4504  685.47  4508.3   684.5  4540.5  682.21  4591.7  674.41  4658.4  667.28
  4741.8  661.35  4783.3   661.7  4808.6  659.12  4814.2  657.58  4836.4  656.01
  4853.1  656.01  4875.3   653.9  4897.6  653.03  4964.3  651.94  4969.9  650.56
  4982.5  650.52  5020.5  650.36  5040.5  652.71  5050.5  652.39  5058.5  650.05
  5058.7  649.55  5062.5  650.05  5070.5  652.04  5090.5  652.93  5120.5  658.34
  5190.5  663.67  5230.5  668.78  5250.5  672.33  5270.5  677.96  5300.5  682.51
#Mann= 5 ,-1 , 0
    4504     .12       0  4783.3     .05       0  4982.5     .12       0
  5058.5     .07       0  5062.5     .12       0
Bank Sta=5058.5,5062.5
XS Rating Curve= 0 ,0
Exp/Cntr=0.3,0.1

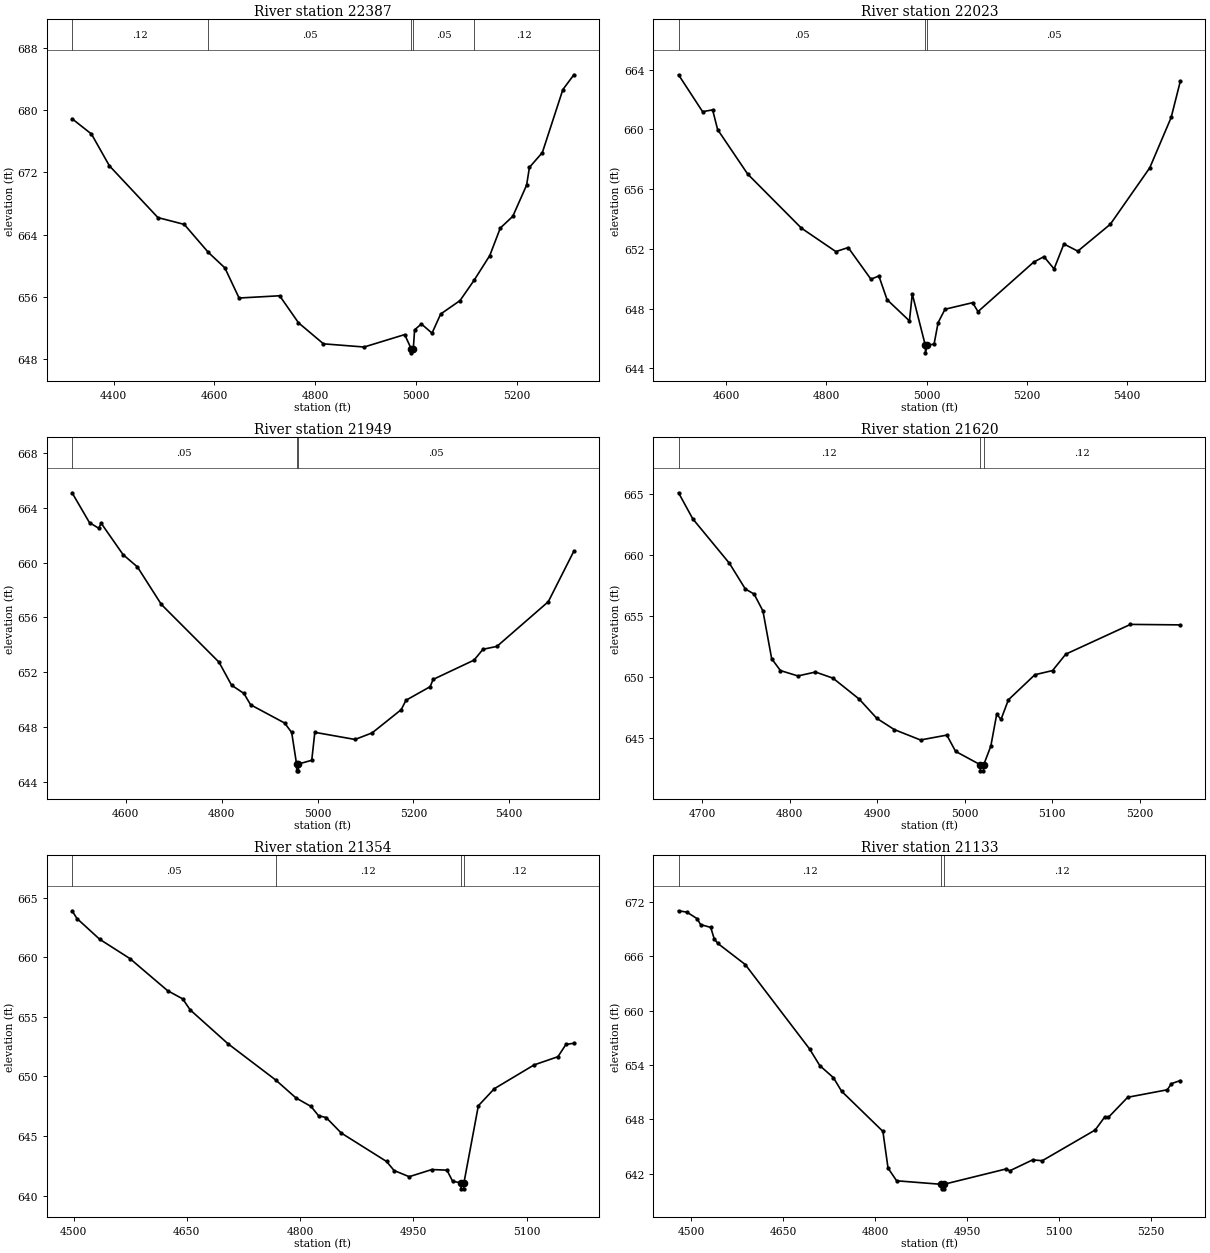
Type RM Length L Ch R = 1 ,22387   ,364,364,364
BEGIN DESCRIPTION:
Sharps Branch 55.0
END DESCRIPTION:
XS GIS Cut Line= 3
      2383072.41      7071709.45      2382479.84      7071370.43
      2382178.99        7071460.
#Sta/Elev= 30
  4317.3  678.91  4355.8  676.94  4391.4  672.85  4487.8  666.18  4540.1   665.3
  4587.9   661.7  4620.8   659.7    4649  655.82  4729.6  656.11    4767  652.63
  4816.6  649.92  4897.3  649.51  4977.9  651.11    4991  649.26  4991.3  648.76
    4995  649.26  4997.6  651.72    5011  652.48  5032.2   651.3  5049.4  653.76
  5087.8  655.49  5115.6  658.09  5146.9  661.29  5167.8  664.83  5192.6  666.34
    5220  670.35  5225.7  672.65  5251.3  674.55  5292.1  682.67  5313.9  684.57
#Mann= 5 ,-1 , 0
  4317.3     .12       0  4587.9     .05       0    4991    .033       0
    4995     .05       0  5115.6     .12       0
Bank Sta=4991,4995
XS Rating Curve= 0 ,0
Exp/Cntr=0.3,0.1

Type RM Length L Ch R = 1 ,22023   ,74,74,74
BEGIN DESCRIPTION:
Mapping XS 08994c51
END DESCRIPTION:
XS GIS Cut Line= 6
      2383206.97      7071203.81      2382847.81      7071195.13
      2382657.92      7071088.79      2382524.46      7071067.09
      2382459.36      7071075.77      2382279.61      7071206.01
#Sta/Elev= 30
  4505.1  663.66  4553.1  661.19  4573.1  661.31  4583.1  659.99  4643.1  657.01
  4750.3  653.39    4819  651.82  4843.6  652.09    4889  649.97  4904.8  650.19
  4921.2   648.6  4965.8  647.18  4971.5  648.98  4997.5  645.54  4997.8  645.04
  5001.5  645.54    5015  645.63    5023  647.06  5036.8  647.96  5091.9   648.4
  5102.6   647.8  5213.9  651.12  5234.2  651.48  5254.4  650.66    5274  652.33
  5301.7  651.85  5366.6  653.65  5445.3  657.43    5488   660.8  5506.3  663.23
#Mann= 3 ,-1 , 0
  4505.1     .05       0  4997.5    .033       0  5001.5     .05       0
Bank Sta=4997.5,5001.5
XS Rating Curve= 0 ,0
Exp/Cntr=0.3,0.1

Type RM Length L Ch R = 1 ,21949   ,329,329,329
BEGIN DESCRIPTION:
Sharps Branch 54.0
END DESCRIPTION:
XS GIS Cut Line= 6
      2383225.45      7071145.22      2382927.02      7071144.13
      2382652.57      7071020.19      2382501.67       7071000.9
      2382397.51      7071021.52      2382252.48      7071138.62
#Sta/Elev= 30
  4487.7  665.09  4524.1  662.91  4543.4   662.5  4548.4  662.87  4594.1  660.58
  4624.1  659.68  4674.1  656.94  4794.4  652.73  4820.6  651.05  4846.3  650.45
  4860.4  649.62  4931.3  648.29  4946.1   647.6  4956.3   645.3  4956.6   644.8
  4960.1   644.8  4960.3   645.3    4988  645.57  4994.4  647.61  5078.3  647.09
  5114.1  647.57  5174.6  649.26  5184.7  649.95  5235.1  650.94  5241.3  651.47
  5326.8  652.88  5345.4  653.67  5374.5  653.88  5481.7  657.14  5535.1  660.83
#Mann= 3 ,-1 , 0
  4487.7     .05       0  4956.3    .033       0  4960.3     .05       0
Bank Sta=4956.3,4960.3
XS Rating Curve= 0 ,0
Exp/Cntr=0.3,0.1

Type RM Length L Ch R = 1 ,21620   ,266,266,266
BEGIN DESCRIPTION:
Sharps Branch 53.0
END DESCRIPTION:
XS GIS Cut Line= 3
      2383055.32      7070778.03        2382729.        7070760.
      2382484.09      7070791.92
#Sta/Elev= 30
  4672.8  665.06  4689.1  662.93    4731   659.3  4749.2   657.2  4759.2  656.79
  4769.3  655.41  4779.3  651.51  4789.3  650.54  4809.3   650.1  4829.4  650.42
  4849.4  649.92  4879.4  648.21  4899.5  646.64  4919.5  645.72  4949.5  644.87
  4979.6  645.27  4989.6  643.94  5017.8  642.85    5018  642.35  5021.5  642.35
  5021.8  642.85  5029.9  644.37  5036.6  646.96  5041.6  646.56    5050  648.15
  5080.3   650.2  5100.5  650.54  5115.6  651.88  5189.6  654.31  5246.6  654.27
#Mann= 3 ,-1 , 0
  4672.8     .12       0  5017.8     .07       0  5021.8     .12       0
Bank Sta=5017.8,5021.8
XS Rating Curve= 0 ,0
Exp/Cntr=0.3,0.1

Type RM Length L Ch R = 1 ,21354   ,221,221,221
BEGIN DESCRIPTION:
Sharps Branch 52.0
END DESCRIPTION:
XS GIS Cut Line= 3
      2383185.48      7070514.14        2382679.        7070510.
      2382529.01        7070560.
#Sta/Elev= 30
  4498.1  663.92  4504.6  663.27  4534.6  661.53  4574.6  659.91  4624.6  657.21
  4644.6  656.52  4654.6  655.59  4704.6  652.75  4767.7  649.71  4794.6   648.2
  4814.6  647.48  4824.6   646.7  4834.6  646.55  4854.6  645.25  4914.6  642.86
  4924.6   642.1  4944.6  641.58  4974.6  642.18  4994.6  642.13  5002.1   641.2
  5013.1  641.06  5013.4  640.56  5016.9  640.56  5017.1  641.06  5036.2  647.54
  5057.3  648.97    5110  650.97  5141.6  651.66  5152.2  652.69  5162.7  652.79
#Mann= 4 ,-1 , 0
  4498.1     .05       0  4767.7     .12       0  5013.1     .07       0
  5017.1     .12       0
Bank Sta=5013.1,5017.1
XS Rating Curve= 0 ,0
Exp/Cntr=0.3,0.1

Type RM Length L Ch R = 1 ,21133   ,268,268,268
BEGIN DESCRIPTION:
Sharps Branch 51.0
END DESCRIPTION:
XS GIS Cut Line= 3
      2383095.99      7070068.73      2382631.48      7070305.21
      2382483.14       7070562.7
#Sta/Elev= 30
    4479  671.05  4492.6   670.9  4509.3  670.18  4514.9  669.53  4531.5  669.21
  4537.1  667.97  4542.9  667.45  4587.8  665.11  4692.8  655.77  4709.4  653.94
  4731.7   652.6  4744.9  651.11  4812.3  646.67  4820.7  642.61  4834.7  641.21
  4907.6  640.82  4907.9  640.32  4911.4  640.32  4911.6  640.82  5013.4  642.52
  5019.1  642.31  5056.5  643.52  5072.3  643.43  5158.5  646.82  5174.3  648.28
  5180.1  648.22  5211.6  650.44  5276.3  651.27  5282.7  651.94  5297.4  652.29
#Mann= 3 ,-1 , 0
    4479     .12       0  4907.6     .07       0  4911.6     .12       0
Bank Sta=4907.6,4911.6
XS Rating Curve= 0 ,0
Exp/Cntr=0.3,0.1

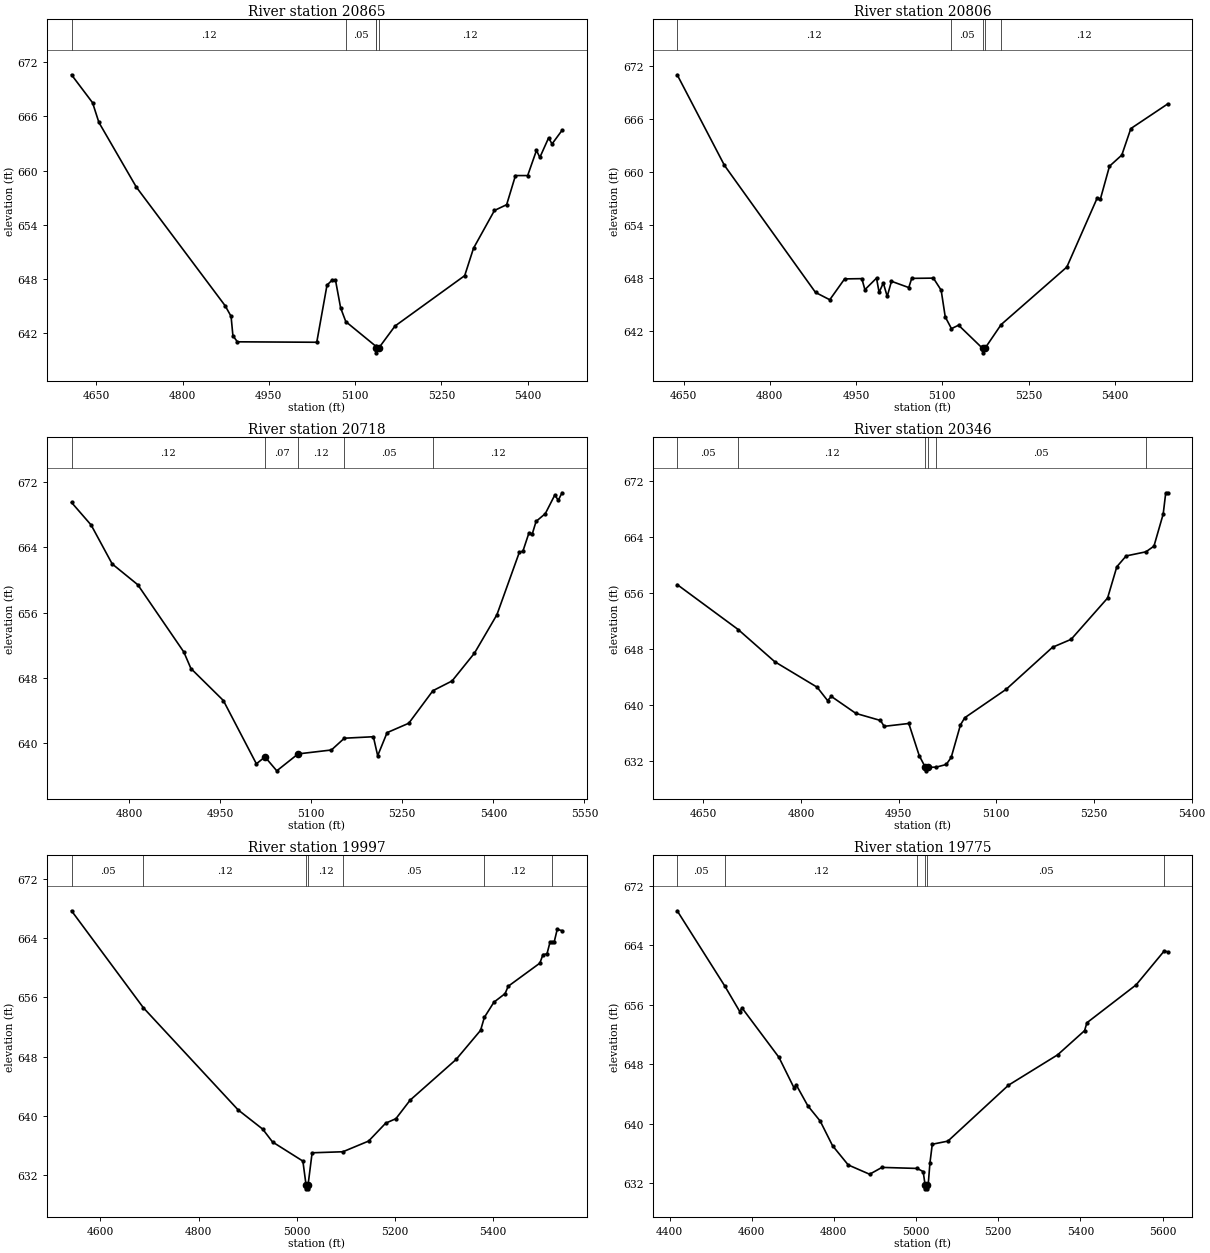
Type RM Length L Ch R = 1 ,20865   ,59,59,59
BEGIN DESCRIPTION:
Mapping XS b9623480
END DESCRIPTION:
XS GIS Cut Line= 6
       2382903.9       7069932.2      2382639.11      7070014.68
      2382558.81       7070049.4      2382537.11      7070073.27
      2382524.09      7070099.31      2382163.89      7070327.15
#Sta/Elev= 30
  4607.1   670.6  4643.7  667.51  4654.7  665.33  4719.8  658.17  4874.1  645.05
  4884.4  643.88  4887.6  641.73  4895.4  641.06  5033.3  641.01  5051.1  647.33
  5059.9  647.88  5065.8   647.9  5074.8  644.81  5083.8  643.29  5135.6  640.59
  5136.7  640.34  5136.9  639.84  5140.7  640.34  5169.2   642.8  5290.4  648.38
  5305.7  651.41  5342.1  655.59  5363.3  656.23  5378.6  659.45  5399.8  659.45
  5415.1  662.23    5421  661.46  5436.2  663.62  5442.2  662.95  5459.5  664.45
#Mann= 5 ,-1 , 0
  4607.1     .12       0  5083.8     .05       0  5135.6     .12       0
  5136.7     .07       0  5140.7     .12       0
Bank Sta=5136.7,5140.7
XS Rating Curve= 0 ,0
Exp/Cntr=0.3,0.1

Type RM Length L Ch R = 1 ,20806   ,88,88,88
BEGIN DESCRIPTION:
Mapping XS 280b3eb8
END DESCRIPTION:
XS GIS Cut Line= 6
      2382866.94      7069890.99       2382595.7      7069982.13
      2382539.28      7070003.83      2382506.73      7070034.21
      2382493.71      7070090.63      2382145.87      7070295.88
#Sta/Elev= 30
  4638.9  670.97  4721.1  660.71  4879.4  646.33  4904.2   645.5    4930  647.86
    4960  647.89  4965.3  646.64  4985.5  647.95    4990  646.33  4997.3   647.4
  5004.1  645.88  5011.5  647.59  5041.6  646.88  5046.7  647.92  5084.4  647.95
  5097.9  646.58    5105  643.56  5115.8  642.23  5128.2  642.62    5170  639.99
  5170.3  639.49    5174  639.99  5202.2  642.69  5316.4   649.2  5369.1     657
  5374.9  656.93  5390.6  660.62    5412  661.88  5427.7  664.88  5491.8  667.67
#Mann= 5 ,-1 , 0
  4638.9     .12       0  5115.8     .05       0    5170     .07       0
    5174     .05       0  5202.2     .12       0
Bank Sta=5170,5174
XS Rating Curve= 0 ,0
Exp/Cntr=0.3,0.1

Type RM Length L Ch R = 1 ,20718   ,372,372,372
BEGIN DESCRIPTION:
Mapping XS 3c3b5407
END DESCRIPTION:
XS GIS Cut Line= 6
      2382799.65       7069810.7       2382530.6      7069923.53
        2382472.      7069982.13      2382441.62      7070042.89
      2382426.43      7070086.29      2382152.39      7070250.29
#Sta/Elev= 30
  4705.2  669.46  4737.6  666.69  4772.2  661.94  4814.3   659.4  4890.2  651.17
  4901.9  649.15  4955.3  645.24  5009.7   637.5  5023.9  638.34  5043.3  636.64
  5078.4  638.71  5133.3  639.19  5154.6  640.63  5202.4  640.81  5209.5  638.49
    5225  641.31  5260.7  642.46  5300.5  646.44    5332  647.63  5368.9  651.03
  5405.9  655.73  5442.8  663.36  5448.7   663.5  5458.4  665.68  5464.2  665.63
  5470.4  667.14  5485.6  668.09  5501.2  670.36    5507  669.72  5513.1  670.64
#Mann= 5 ,-1 , 0
  4705.2     .12       0  5023.9     .07       0  5078.4     .12       0
  5154.6     .05       0  5300.5     .12       0
Bank Sta=5023.9,5078.4
XS Rating Curve= 0 ,0
Exp/Cntr=0.3,0.1

Type RM Length L Ch R = 1 ,20346   ,349,349,349
BEGIN DESCRIPTION:
Sharps Branch 48.0
END DESCRIPTION:
XS GIS Cut Line= 3
      2382603.68      7069521.52       2382262.9      7069711.18
      2381989.51      7069950.13
#Sta/Elev= 30
    4610  657.22  4703.6  650.79  4759.8  646.18  4824.9  642.53  4840.9  640.62
  4846.7  641.21  4884.4  638.78  4922.1  637.77  4927.8  636.93  4965.6  637.34
  4981.6  632.74    4991  631.06  4991.3  630.56    4995  631.06  5007.7  631.09
  5023.1  631.47  5030.7  632.48  5044.9  637.13  5051.5  638.16  5115.1  642.23
  5186.3  648.25  5214.8  649.38  5270.8  655.29    5285  659.77  5299.3  661.32
  5329.7  661.91    5342  662.72  5356.2  667.32  5360.1  670.36  5363.1  670.36
#Mann= 6 ,-1 , 0
    4610     .05       0  4703.6     .12       0    4991     .07       0
    4995     .12       0  5007.7     .05       0  5329.7     .12       0
Bank Sta=4991,4995
XS Rating Curve= 0 ,0
Exp/Cntr=0.3,0.1

Type RM Length L Ch R = 1 ,19997   ,222,222,222
BEGIN DESCRIPTION:
Mapping XS 2e910cab
END DESCRIPTION:
XS GIS Cut Line= 4
      2382688.18      7069439.81       2382220.7      7069426.79
      2382056.64      7069461.94      2381767.61      7069681.97
#Sta/Elev= 30
  4541.4  667.68  4687.8   654.6  4880.7  640.83  4930.7  638.24  4950.7  636.51
  5012.5  633.93    5019  630.69  5019.3  630.19  5022.8  630.19    5023  630.69
  5031.3  635.05    5094  635.19  5146.3  636.63    5181  639.04  5201.9  639.65
  5230.9  642.15  5324.4  647.63  5374.3  651.56    5382  653.31  5401.5  655.36
  5424.2  656.51  5430.5   657.5    5495  660.62  5501.3  661.77  5509.5  661.87
  5515.8  663.48  5520.7  663.45    5524  663.43  5530.3  665.16  5540.1  665.01
#Mann= 7 ,-1 , 0
  4541.4     .05       0  4687.8     .12       0    5019     .07       0
    5023     .12       0    5094     .05       0    5382     .12       0
  5520.7     .05       0
Bank Sta=5019,5023
XS Rating Curve= 0 ,0
Exp/Cntr=0.3,0.1

Type RM Length L Ch R = 1 ,19775   ,345,345,345
BEGIN DESCRIPTION:
Mapping XS d344317e
END DESCRIPTION:
XS GIS Cut Line= 3
      2382666.04      7069356.48      2382060.55       7069310.9
      2381544.94      7069590.84
#Sta/Elev= 30
  4418.7  668.62  4534.8  658.49  4571.4  655.05  4576.4  655.58  4666.4  648.93
  4703.2  644.82  4708.2  645.26  4736.6  642.43  4766.7  640.38  4796.8  637.07
    4835  634.48  4887.1  633.23  4917.1  634.15  5002.8  634.01  5017.4  633.59
  5022.2  631.77  5022.4  631.27  5025.9  631.27  5026.2  631.77  5029.6  631.77
  5033.9  634.74  5039.6  637.26  5077.6  637.68    5225  645.19  5344.7  649.27
  5410.3  652.52    5416  653.58  5535.8  658.67  5604.1  663.22  5612.6  663.11
#Mann= 6 ,-1 , 0
  4418.7     .05       0  4534.8     .12       0  5002.8     .05       0
  5022.2     .07       0  5026.2     .05       0  5604.1     .12       0
Bank Sta=5022.2,5026.2
XS Rating Curve= 0 ,0
Exp/Cntr=0.3,0.1

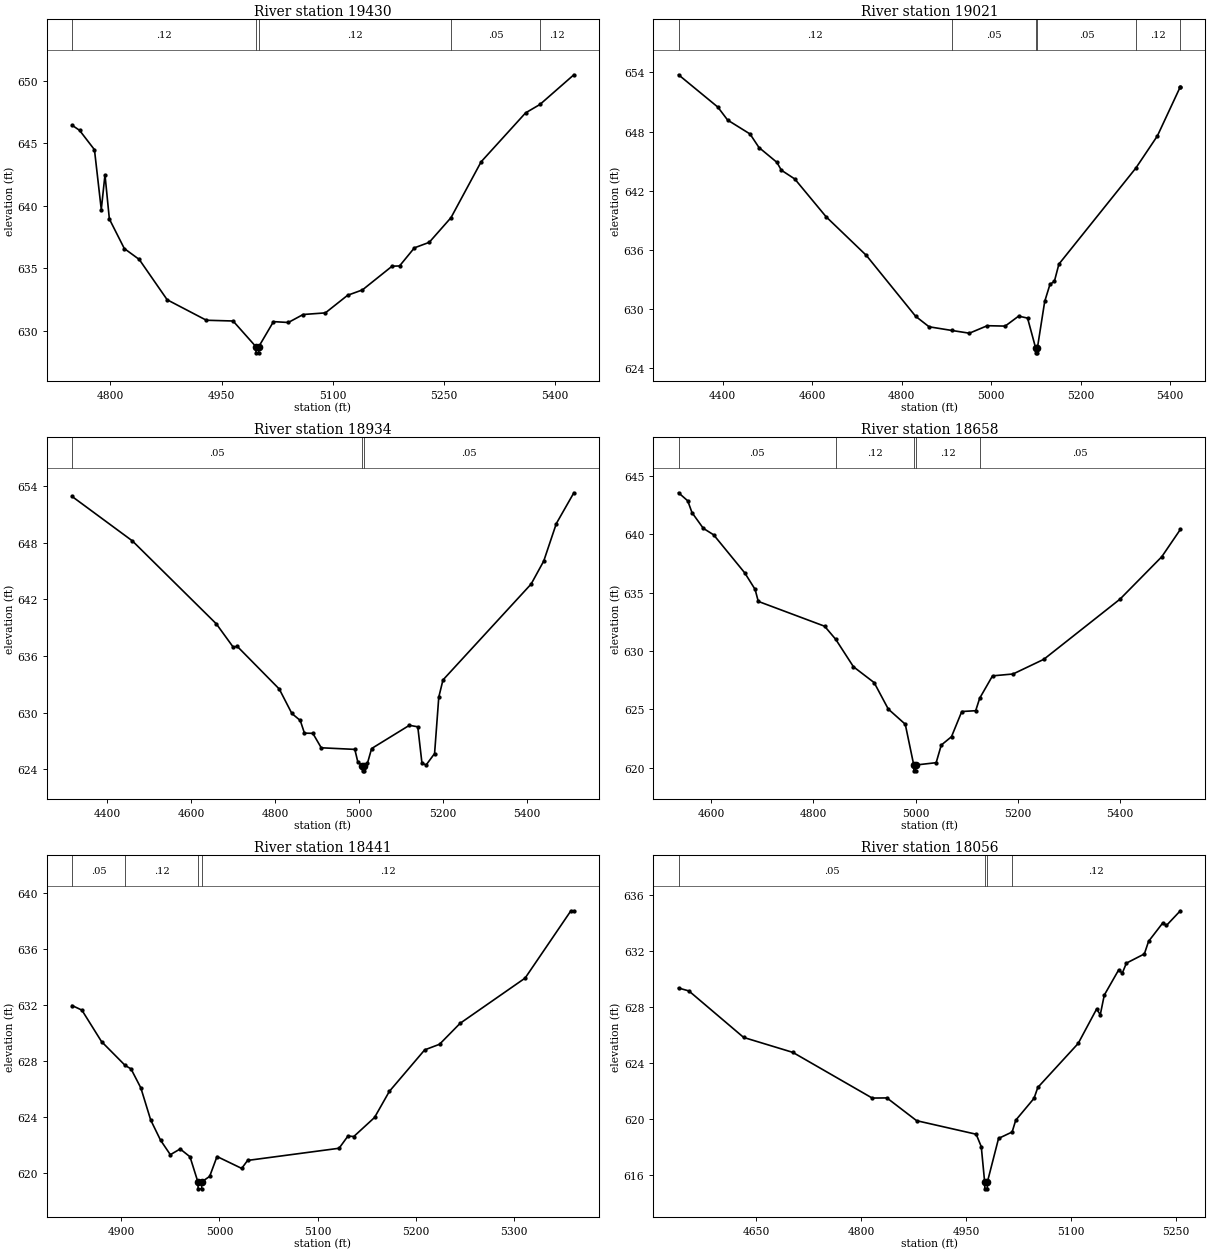
Type RM Length L Ch R = 1 ,19430   ,409,409,409
BEGIN DESCRIPTION:
Sharps Branch 45.0
END DESCRIPTION:
XS GIS Cut Line= 3
      2382328.99        7069060.      2382077.47      7069030.95
      2381653.96      7069044.07
#Sta/Elev= 30
  4748.3  646.46  4758.4  646.05  4778.5   644.5  4787.7  639.71  4792.7  642.49
  4798.6  638.95  4818.8  636.58  4838.9  635.71  4876.6  632.48  4929.5  630.84
  4965.5  630.78  4996.2  628.73  4996.5  628.23    5000  628.23  5000.2  628.73
    5020  630.73    5040  630.66    5060   631.3    5090  631.43    5120  632.84
    5140  633.27    5180  635.17  5190.1  635.19  5210.1  636.64  5230.1  637.08
  5259.5  639.06  5300.1  643.53  5360.1  647.45  5379.4  648.12  5425.2   650.5
#Mann= 5 ,-1 , 0
  4748.3     .12       0  4996.2     .07       0  5000.2     .12       0
  5259.5     .05       0  5379.4     .12       0
Bank Sta=4996.2,5000.2
XS Rating Curve= 0 ,0
Exp/Cntr=0.3,0.1

Type RM Length L Ch R = 1 ,19021   ,87,87,87
BEGIN DESCRIPTION:
Mapping XS a426d1f9
END DESCRIPTION:
XS GIS Cut Line= 3
      2382728.68      7068766.54      2382009.49       7068754.3
       2381607.7      7068757.04
#Sta/Elev= 30
  4301.3  653.75    4389  650.48    4411  649.16    4461  647.75    4481  646.38
    4521  644.88    4531  644.08    4561  643.19    4631  639.36    4721  635.44
  4831.1  629.27  4861.1  628.21  4911.5  627.84  4951.1  627.56  4991.1  628.32
  5031.1  628.28  5061.1  629.29  5081.1  629.09  5099.1  626.07  5099.3  625.57
  5102.8  625.57  5103.1  626.07  5119.4  630.78  5131.1   632.5  5141.1  632.83
  5151.1  634.56  5323.1   644.3  5371.1  647.55  5422.2  652.52  5422.4  652.52
#Mann= 6 ,-1 , 0
  4301.3     .12       0  4911.5     .05       0  5099.1    .033       0
  5103.1     .05       0  5323.1     .12       0  5422.2     .05       0
Bank Sta=5099.1,5103.1
XS Rating Curve= 0 ,0
Exp/Cntr=0.3,0.1

Type RM Length L Ch R = 1 ,18934   ,276,276,276
BEGIN DESCRIPTION:
Mapping XS 5418c456
END DESCRIPTION:
XS GIS Cut Line= 4
      2382762.57      7068696.23      2382080.29      7068687.12
      2381855.03      7068688.42      2381567.24      7068689.72
#Sta/Elev= 30
  4316.4  652.88    4460  648.18    4660   639.4    4700  636.95    4710  637.01
    4810   632.5    4840  629.91    4860  629.17    4870  627.83    4890  627.81
    4910  626.28    4990  626.11  4996.9  624.82    5008  624.34  5008.3  623.84
  5011.8  623.84    5012  624.34    5020  624.63    5030   626.2    5120  628.66
    5140   628.5    5150  624.63    5160  624.47    5180  625.67    5190  631.64
    5200  633.46    5410  643.61    5440  646.04    5470  650.01  5511.8  653.27
#Mann= 3 ,-1 , 0
  4316.4     .05       0    5008    .033       0    5012     .05       0
Bank Sta=5008,5012
XS Rating Curve= 0 ,0
Exp/Cntr=0.3,0.1

Type RM Length L Ch R = 1 ,18658   ,217,217,217
BEGIN DESCRIPTION:
Mapping XS 5f240c49
END DESCRIPTION:
XS GIS Cut Line= 3
      2382586.82      7068499.62      2382127.16       7068426.7
      2381612.75      7068463.07
#Sta/Elev= 30
  4536.5  643.58  4554.5  642.89  4562.8  641.88  4584.9  640.53  4605.2  639.97
  4665.9  636.71  4686.2  635.29  4692.4  634.26  4822.1  632.13  4843.9     631
  4878.5  628.65    4919  627.29  4946.6  625.02  4979.8  623.72  4996.4  620.22
  4996.7  619.72  5000.2  619.72  5000.4  620.22  5040.2  620.42  5050.2  621.93
  5070.2  622.65  5090.3  624.81  5117.5  624.88  5125.3  625.95  5150.4  627.87
  5190.5  628.03  5250.7  629.29  5399.6  634.45  5481.3  638.09  5517.6  640.43
#Mann= 5 ,-1 , 0
  4536.5     .05       0  4843.9     .12       0  4996.4     .07       0
  5000.4     .12       0  5125.3     .05       0
Bank Sta=4996.4,5000.4
XS Rating Curve= 0 ,0
Exp/Cntr=0.3,0.1

Type RM Length L Ch R = 1 ,18441   ,385,385,385
BEGIN DESCRIPTION:
Sharps Branch 42.0
END DESCRIPTION:
XS GIS Cut Line= 3
      2382279.02        7068210.        2382129.        7068210.
      2381828.98      7068009.99
#Sta/Elev= 30
    4850  631.96    4860  631.63    4880  629.38    4904  627.68    4910  627.43
    4920  626.07    4930  623.78    4940  622.34    4950   621.3    4960  621.71
    4970  621.15    4978  619.36  4978.3  618.86  4981.8  618.86    4982  619.36
    4990  619.75  4997.5  621.17  5022.6  620.32  5028.6  620.89  5121.7  621.76
  5130.7  622.63  5136.7   622.6  5157.8  623.96  5172.8  625.82  5208.8  628.79
  5223.9  629.19  5244.9  630.69    5311  633.92  5357.6  638.73  5360.6  638.73
#Mann= 4 ,-1 , 0
    4850     .05       0    4904     .12       0    4978     .07       0
    4982     .12       0
Bank Sta=4978,4982
XS Rating Curve= 0 ,0
Exp/Cntr=0.3,0.1

Type RM Length L Ch R = 1 ,18056   ,374,374,374
BEGIN DESCRIPTION:
Sharps Branch 41.0
END DESCRIPTION:
XS GIS Cut Line= 3
      2382441.52      7068198.64        2382129.        7067860.
      2381885.92      7067778.46
#Sta/Elev= 30
  4538.9  629.37  4553.7  629.16    4632  625.83  4702.3  624.76  4815.7  621.49
  4836.7   621.5  4879.2  619.87  4964.3   618.9  4971.6  618.01  4976.4  615.49
  4976.7  614.99  4980.2  614.99  4980.4  615.49  4996.3   618.6  5015.7  619.06
  5020.8   619.9    5047  621.47  5052.4  622.25  5110.1   625.4  5136.4  627.86
  5141.7  627.46  5147.4  628.86  5167.9  630.66  5173.2  630.44    5179  631.15
  5204.7  631.81  5210.7  632.71    5231  634.03  5236.3  633.85  5256.1   634.9
#Mann= 4 ,-1 , 0
  4538.9     .05       0  4976.4    .033       0  4980.4     .05       0
  5015.7     .12       0
Bank Sta=4976.4,4980.4
XS Rating Curve= 0 ,0
Exp/Cntr=0.3,0.1

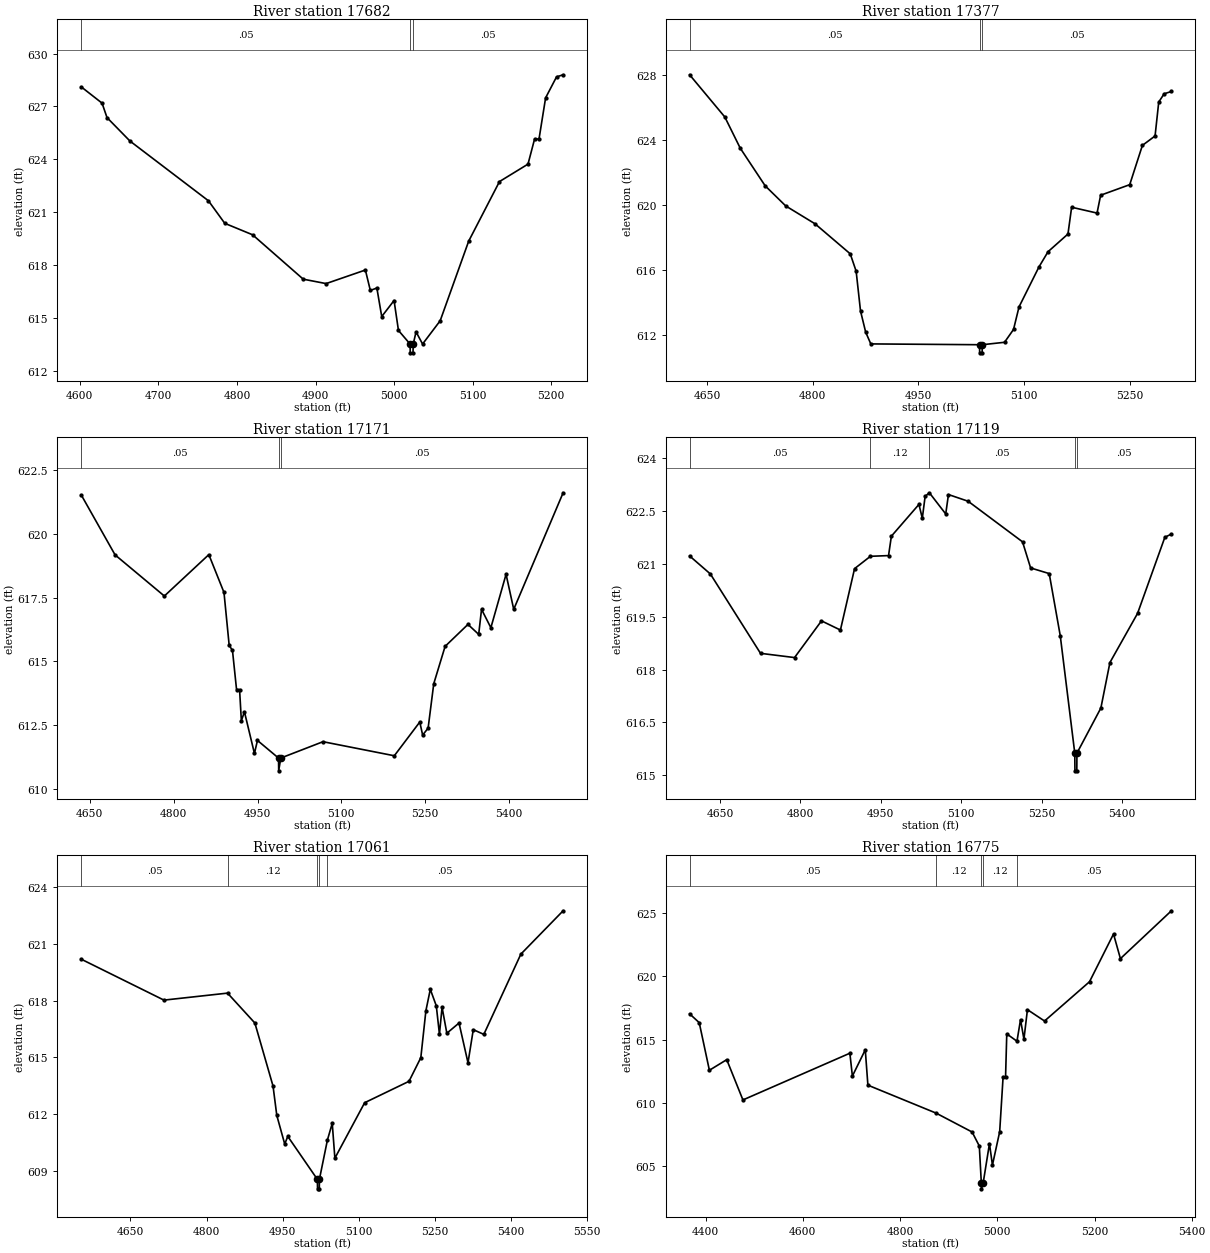
Type RM Length L Ch R = 1 ,17682   ,305,305,305
BEGIN DESCRIPTION:
Sharps Branch 40.0
END DESCRIPTION:
XS GIS Cut Line= 3
      2382740.07      7067894.76        2382429.        7067660.
      2382229.02      7067560.01
#Sta/Elev= 30
  4601.9  628.11  4628.3  627.19  4634.6  626.37  4663.8  625.04  4763.7  621.65
  4784.5  620.37  4819.9  619.72  4884.4   617.2  4913.5  616.95  4963.5  617.72
  4969.8  616.56  4978.1   616.7  4984.3  615.08    5000  615.99  5005.6  614.29
  5020.4  613.52  5020.6  613.02  5024.1  613.02  5024.4  613.52    5028  614.21
  5036.3  613.52  5058.7  614.84    5095  619.36  5134.2  622.74  5170.5  623.73
  5178.9  625.16  5184.5  625.15  5192.9  627.49  5206.8  628.68  5215.2   628.8
#Mann= 3 ,-1 , 0
  4601.9     .05       0  5020.4    .033       0  5024.4     .05       0
Bank Sta=5020.4,5024.4
XS Rating Curve= 0 ,0
Exp/Cntr=0.3,0.1

Type RM Length L Ch R = 1 ,17377   ,206,206,206
BEGIN DESCRIPTION:
Sharps Branch 39.0
END DESCRIPTION:
XS GIS Cut Line= 3
        2382829.        7067610.        2382529.        7067385.
      2382229.03      7067459.99
#Sta/Elev= 30
    4625  628.03    4675  625.43  4696.9  623.51  4732.3  621.19  4761.5  619.95
  4803.1  618.85  4853.1     617  4861.5  615.93  4867.7  613.48    4875  612.18
  4882.3  611.45  5036.7   611.4  5036.9   610.9  5040.4   610.9  5040.7   611.4
  5072.2  611.55    5085  612.34  5092.8  613.73  5121.1  616.19    5134  617.13
  5162.3  618.22  5167.5  619.87  5203.6  619.51  5208.7  620.61    5250  621.26
    5268  623.68    5286  624.26  5291.2  626.35  5298.9  626.86  5309.2     627
#Mann= 3 ,-1 , 0
    4625     .05       0  5036.7    .033       0  5040.7     .05       0
Bank Sta=5036.7,5040.7
XS Rating Curve= 0 ,0
Exp/Cntr=0.3,0.1

Type RM Length L Ch R = 1 ,17171   ,52,52,52
BEGIN DESCRIPTION:
Mapping XS 15a5e5f6
END DESCRIPTION:
XS GIS Cut Line= 6
      2382832.66      7067441.11      2382718.09      7067267.53
      2382654.82      7067227.23      2382519.31      7067175.51
      2382414.28       7067165.1      2382092.64      7067226.45
#Sta/Elev= 30
  4634.7  621.51  4695.1  619.17  4783.3  617.56  4862.9  619.18    4890   617.7
  4899.3  615.63  4905.2  615.43  4912.5   613.9  4917.9   613.9  4921.1  612.68
  4926.6  613.03  4944.5   611.4  4949.9  611.91  4987.6  611.22  4987.9  610.72
  4991.6  611.22  5067.2  611.86  5194.8  611.31  5240.4  612.63  5245.5  612.12
  5255.3  612.39  5265.4  614.13  5285.7  615.59  5326.6  616.45  5345.8  616.06
  5350.9  617.04  5367.6  616.32  5394.8  618.41  5408.5  617.04  5496.9   621.6
#Mann= 3 ,-1 , 0
  4634.7     .05       0  4987.6    .033       0  4991.6     .05       0
Bank Sta=4987.6,4991.6
XS Rating Curve= 0 ,0
Exp/Cntr=0.3,0.1

Type RM Length L Ch R = 1 ,17119   ,58,58,58
BEGIN DESCRIPTION:
Mapping XS 96148f15
END DESCRIPTION:
XS GIS Cut Line= 6
      2382875.64      7067408.14      2382728.08      7067225.86
      2382667.31      7067178.12      2382533.85      7067129.29
      2382371.09      7067120.61      2382097.61      7067186.81
#Sta/Elev= 30
  4593.2  621.22  4631.9  620.71  4725.5  618.46    4789  618.34  4839.3  619.38
  4874.6  619.12    4901  620.86  4930.6  621.21  4964.4  621.23  4969.7  621.78
  5021.1  622.68  5027.4  622.29  5032.7  622.91  5040.6  623.01  5071.1  622.41
  5076.2  622.96  5112.9  622.77  5214.4  621.62  5229.5  620.88  5264.2  620.72
  5284.8  618.96  5311.9  615.63  5312.2  615.13  5315.7  615.13  5315.9  615.63
  5360.6  616.91  5377.5   618.2    5429  619.59    5480  621.75  5492.2  621.84
#Mann= 5 ,-1 , 0
  4593.2     .05       0  4930.6     .12       0  5040.6     .05       0
  5311.9     .07       0  5315.9     .05       0
Bank Sta=5311.9,5315.9
XS Rating Curve= 0 ,0
Exp/Cntr=0.3,0.1

Type RM Length L Ch R = 1 ,17061   ,286,286,286
BEGIN DESCRIPTION:
Sharps Branch 38.0
END DESCRIPTION:
XS GIS Cut Line= 6
        2382906.      7067383.16      2382688.33      7067147.41
      2382579.05      7067085.56       2382431.9       7067068.2
      2382336.76       7067080.7      2382089.02      7067153.15
#Sta/Elev= 30
  4553.2  620.18  4716.1  618.02  4841.4  618.39  4895.3  616.81  4931.1  613.48
  4938.5  611.93  4954.1  610.42  4960.2  610.82  5018.5  608.55  5018.8  608.05
  5022.3  608.05  5022.5  608.55  5038.3  610.63  5047.8  611.51    5053  609.67
  5111.7   612.6  5199.1  613.73  5222.4  614.98  5232.4  617.46  5241.1  618.59
  5252.9  617.72  5259.1  616.22  5264.3  617.64  5273.7  616.27  5297.7  616.81
  5315.4  614.71  5325.8  616.46  5346.6  616.21  5419.6  620.45  5502.9  622.74
#Mann= 5 ,-1 , 0
  4553.2     .05       0  4841.4     .12       0  5018.5     .07       0
  5022.5     .12       0  5038.3     .05       0
Bank Sta=5018.5,5022.5
XS Rating Curve= 0 ,0
Exp/Cntr=0.3,0.1

Type RM Length L Ch R = 1 ,16775   ,262,262,262
BEGIN DESCRIPTION:
Mapping XS ebee8d5f
END DESCRIPTION:
XS GIS Cut Line= 6
        2383160.      7067046.59      2383077.56      7066988.01
      2382836.67      7066951.12      2382627.25      7066859.97
      2382497.04      7066751.47      2382337.41      7066563.83
#Sta/Elev= 30
    4367  617.04  4386.8  616.34  4407.7  612.57  4443.4  613.41  4476.7  610.22
  4696.7  613.92  4701.9  612.11  4728.4  614.19  4733.8  611.39  4873.9  609.18
  4948.2  607.68    4963  606.57  4967.1  603.68  4967.4  603.18  4971.1  603.68
  4983.9  606.76    4990  605.06  5004.9   607.7  5011.9  612.02    5017  612.02
  5019.5  615.45  5040.5  614.87  5047.8  616.58  5054.8  615.03    5062  617.37
  5097.2  616.47  5189.7  619.58  5239.1  623.36  5253.3  621.41  5358.2   625.2
#Mann= 5 ,-1 , 0
    4367     .05       0  4873.9     .12       0  4967.1     .07       0
  4971.1     .12       0  5040.5     .05       0
Bank Sta=4967.1,4971.1
XS Rating Curve= 0 ,0
Exp/Cntr=0.3,0.1