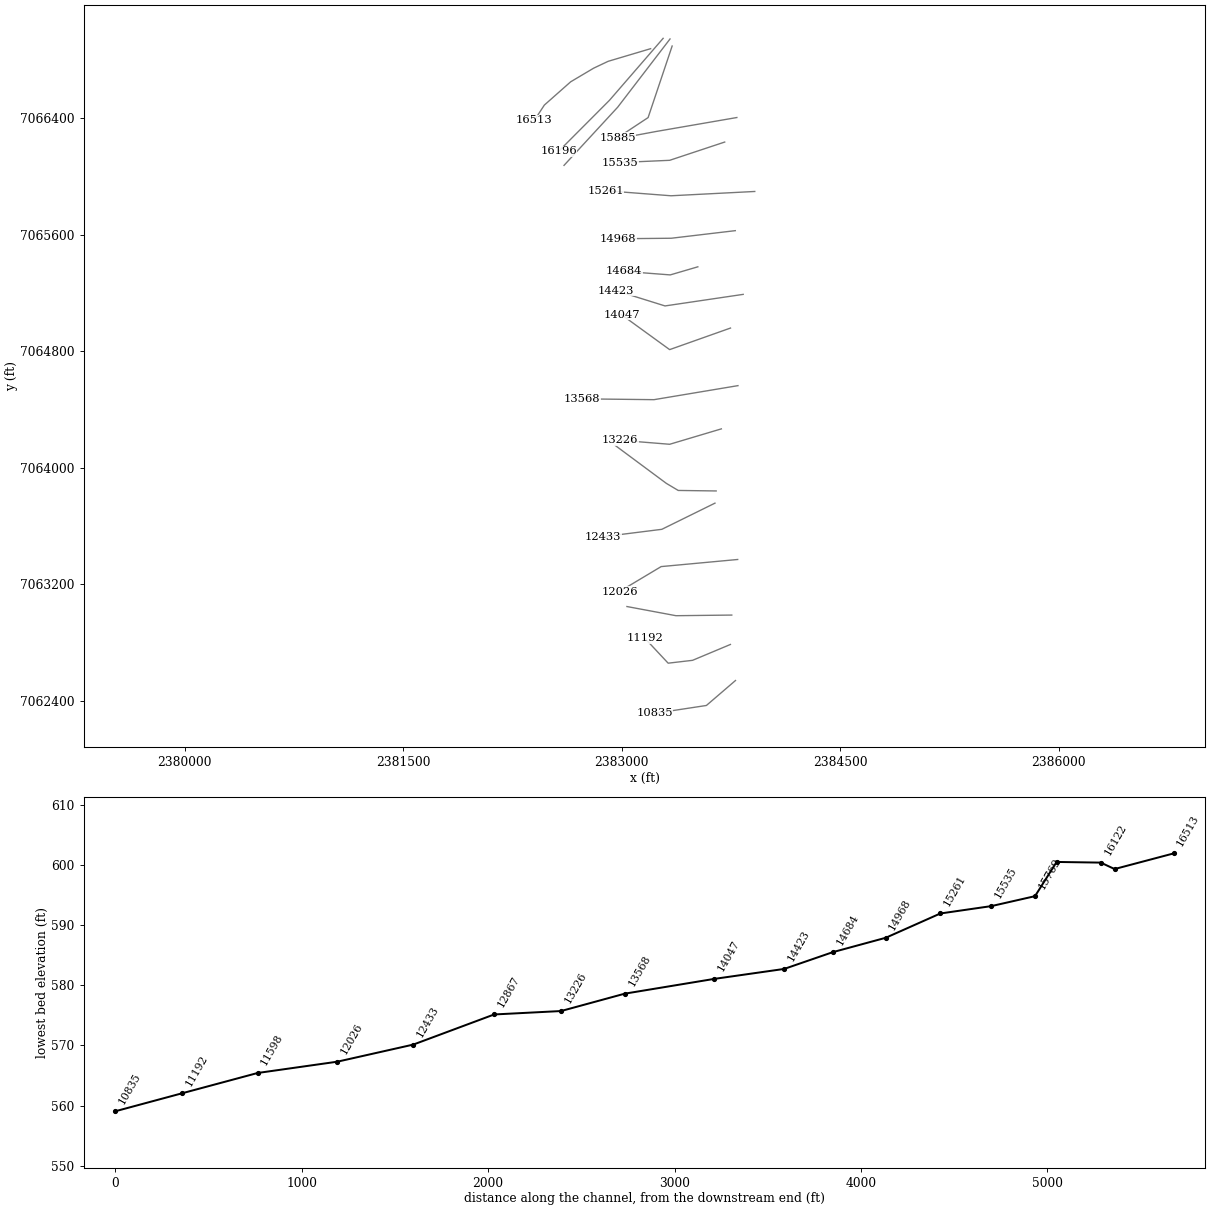
HEC-RAS study Sharps Branch.prj: Sharps Branch Base Level Engineering

--- Sharps Branch.g01 (geometry) --- (continued)

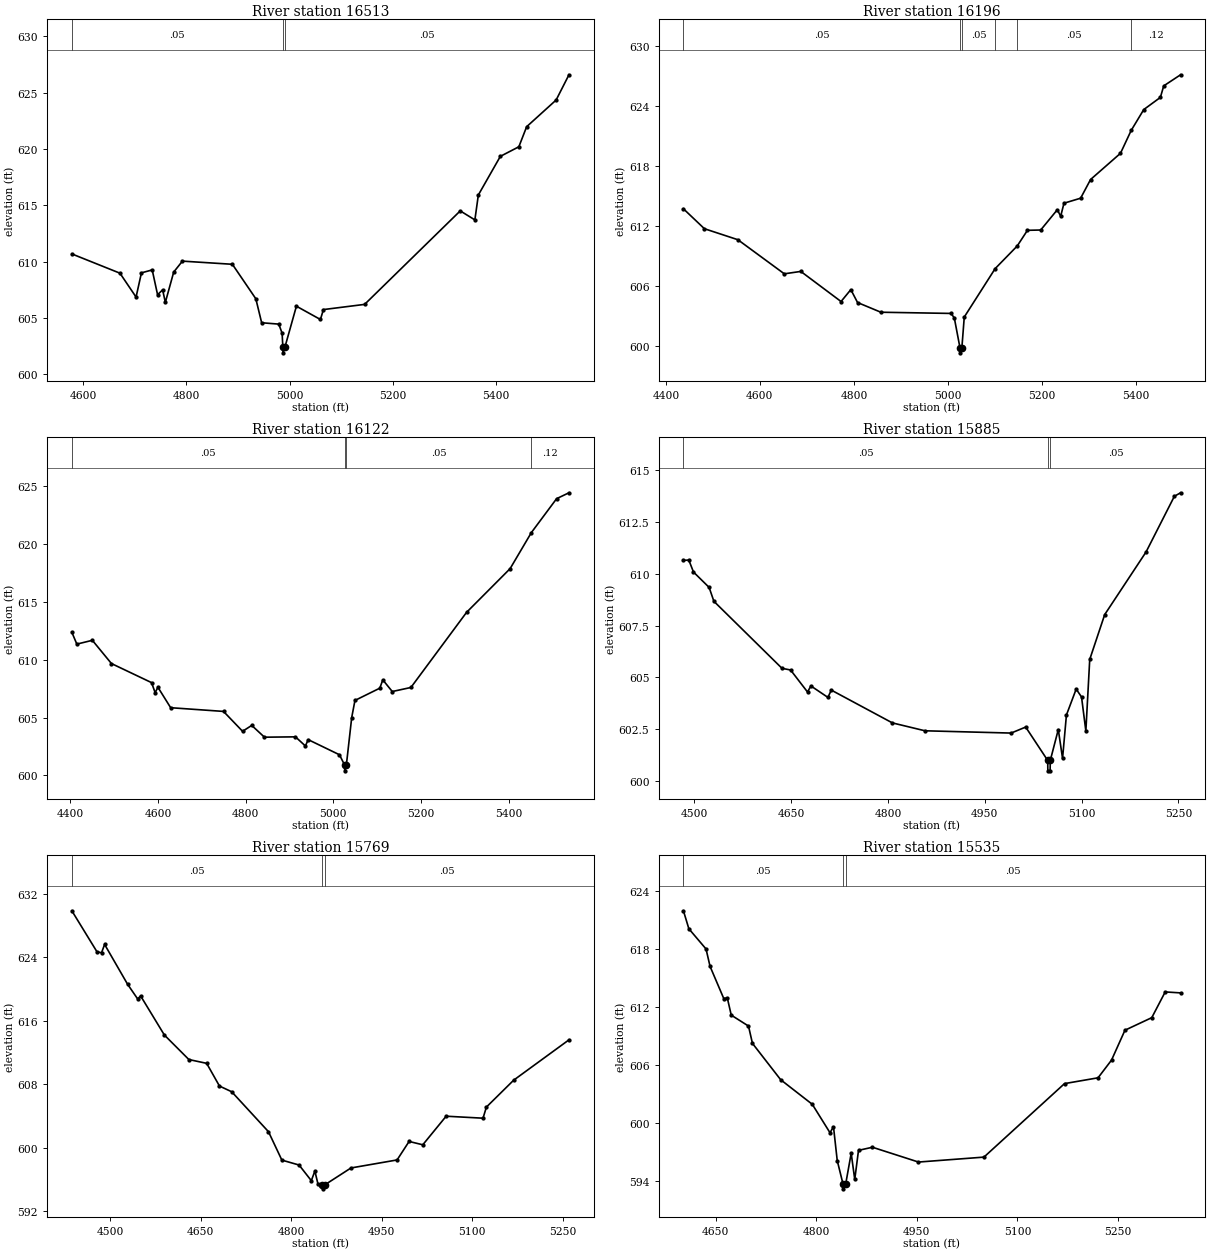
Type RM Length L Ch R = 1 ,16513   ,317,317,317
BEGIN DESCRIPTION:
Mapping XS e5ba9b05
END DESCRIPTION:
XS GIS Cut Line= 6
       2383198.4      7066876.56      2382906.72      7066789.75
      2382807.76      7066742.88      2382649.78      7066649.13
      2382469.22       7066489.4      2382400.29      7066384.28
#Sta/Elev= 30
  4577.7   610.7    4671  608.99  4702.3  606.87  4712.7  609.02  4733.6  609.28
    4744  607.08  4753.8  607.51  4759.1   606.4  4775.3  609.09  4792.2  610.06
  4889.1  609.78  4934.6  606.72  4945.9  604.59  4979.1  604.47  4985.6  603.66
    4987  602.42  4987.3  601.92    4991  602.42  5013.3  606.06  5059.9  604.88
  5065.7  605.76  5145.6  606.22  5331.1  614.52  5359.5  613.72  5366.2  615.93
  5408.9  619.36  5444.8  620.21  5459.9  621.99  5517.1  624.36    5542   626.6
#Mann= 3 ,-1 , 0
  4577.7     .05       0    4987    .033       0    4991     .05       0
Bank Sta=4987,4991
XS Rating Curve= 0 ,0
Exp/Cntr=0.3,0.1

Type RM Length L Ch R = 1 ,16196   ,74,74,74
BEGIN DESCRIPTION:
Sharps Branch 36.0
END DESCRIPTION:
XS GIS Cut Line= 3
      2383284.19       7066947.6       2382915.7      7066521.83
      2382566.75      7066171.57
#Sta/Elev= 30
  4437.4  613.72    4482  611.73  4553.2  610.63    4652  607.22  4687.1  607.46
  4772.7  604.45  4793.5  605.64  4807.8  604.35  4857.4  603.38  5006.5  603.26
  5013.6  602.82  5025.7  599.82    5026  599.32  5029.7  599.82  5034.8   602.9
  5100.5  607.74  5147.4     610  5169.2  611.57  5197.4   611.6  5232.8  613.63
  5239.9  612.97  5246.9  614.28  5282.3  614.78  5303.5  616.65  5367.1  619.27
  5389.8  621.55  5416.6  623.64    5452  624.86  5459.1  626.01  5494.9  627.12
#Mann= 6 ,-1 , 0
  4437.4     .05       0  5025.7    .033       0  5029.7     .05       0
  5100.5     .12       0  5147.4     .05       0  5389.8     .12       0
Bank Sta=5025.7,5029.7
XS Rating Curve= 0 ,0
Exp/Cntr=0.3,0.1

Type RM Length L Ch R = 1 ,16122   ,237,237,237
BEGIN DESCRIPTION:
Mapping XS 666b5eb4
END DESCRIPTION:
XS GIS Cut Line= 3
      2383331.53       7066943.3      2382972.13      7066474.52
      2382604.04      7066075.18
#Sta/Elev= 30
  4403.7  612.38  4415.1  611.35  4450.5  611.68    4494  609.67  4585.5  608.02
  4593.7  607.15    4600  607.62  4629.1  605.85  4749.6  605.53  4793.1  603.81
    4814  604.32    4843   603.3  4913.7  603.33  4936.4  602.54  4942.7  603.09
  5014.1  601.78  5025.8  600.89  5026.1  600.39  5029.8  600.89    5042     605
  5049.4  606.48  5106.1  607.54  5112.9  608.26  5134.5  607.25    5177   607.6
    5304   614.1  5403.3  617.88  5451.8     621  5509.3  623.93  5537.5  624.44
#Mann= 4 ,-1 , 0
  4403.7     .05       0  5025.8    .033       0  5029.8     .05       0
  5451.8     .12       0
Bank Sta=5025.8,5029.8
XS Rating Curve= 0 ,0
Exp/Cntr=0.3,0.1

Type RM Length L Ch R = 1 ,15885   ,116,116,116
BEGIN DESCRIPTION:
Mapping XS f2afb12e
END DESCRIPTION:
XS GIS Cut Line= 3
      2383346.02      7066894.75       2383181.1      7066403.45
        2382971.      7066264.55
#Sta/Elev= 30
  4483.1  610.64  4491.4  610.66  4498.7  610.08  4522.9  609.34  4530.3  608.67
  4635.8  605.44  4649.1  605.36  4675.3   604.3  4680.6  604.59  4706.9  604.04
  4712.2  604.39  4806.8  602.81  4857.3  602.43  4990.7  602.32  5013.3  602.61
  5047.4     601  5047.6   600.5  5051.1   600.5  5051.4     601  5063.8  602.49
  5070.4   601.1  5076.4  603.19  5091.5  604.44  5099.8  604.06  5106.5  602.42
  5112.5  605.87  5135.7  608.03  5199.8  611.05  5243.6  613.73  5253.2   613.9
#Mann= 3 ,-1 , 0
  4483.1     .05       0  5047.4    .033       0  5051.4     .05       0
Bank Sta=5047.4,5051.4
XS Rating Curve= 0 ,0
Exp/Cntr=0.3,0.1

Type RM Length L Ch R = 1 ,15769   ,234,234,234
BEGIN DESCRIPTION:
Sharps Branch 35.0
END DESCRIPTION:
XS GIS Cut Line= 3
      2383790.03      7066403.81      2383234.88      7066307.74
        2382979.        7066260.
#Sta/Elev= 30
  4436.6  629.84  4478.2  624.68  4485.8  624.55  4490.9   625.6    4529  620.58
  4545.6  618.74  4550.6  619.11  4589.9  614.19  4630.5   611.1    4660  610.62
  4681.2  607.76  4701.5  607.04  4762.4  602.01  4784.6  598.43  4813.1  597.81
  4833.4  595.84  4839.3  597.05  4844.4  595.42  4851.7  595.31    4852  594.81
  4855.7  595.31  4899.1  597.44  4975.5  598.45  4995.4  600.78  5018.1  600.36
  5056.8  603.96  5117.9  603.71  5123.5  605.11  5168.7   608.5  5260.3  613.58
#Mann= 3 ,-1 , 0
  4436.6     .05       0  4851.7    .033       0  4855.7     .05       0
Bank Sta=4851.7,4855.7
XS Rating Curve= 0 ,0
Exp/Cntr=0.3,0.1

Type RM Length L Ch R = 1 ,15535   ,274,274,274
BEGIN DESCRIPTION:
Sharps Branch 34.0
END DESCRIPTION:
XS GIS Cut Line= 3
      2383706.65       7066235.4        2383329.        7066110.
      2382986.17      7066094.78
#Sta/Elev= 30
  4602.1  621.91  4610.2  620.05  4635.8  617.96  4641.8  616.16  4662.2  612.84
  4667.5   612.9  4673.4  611.12  4699.1  609.99    4705   608.2  4747.1  604.44
  4794.2   601.9  4820.6  598.96  4825.8  599.58  4831.4  596.08    4840  593.66
  4840.2  593.16    4844  593.66  4852.2  596.84  4857.5  594.13  4863.1  597.14
  4883.9  597.46  4952.5  595.93  5050.1  596.44  5170.2  604.04  5220.2  604.64
  5240.3  606.47  5260.3  609.56  5300.3  610.86  5320.3  613.52  5343.2  613.42
#Mann= 3 ,-1 , 0
  4602.1     .05       0    4840    .033       0    4844     .05       0
Bank Sta=4840,4844
XS Rating Curve= 0 ,0
Exp/Cntr=0.3,0.1

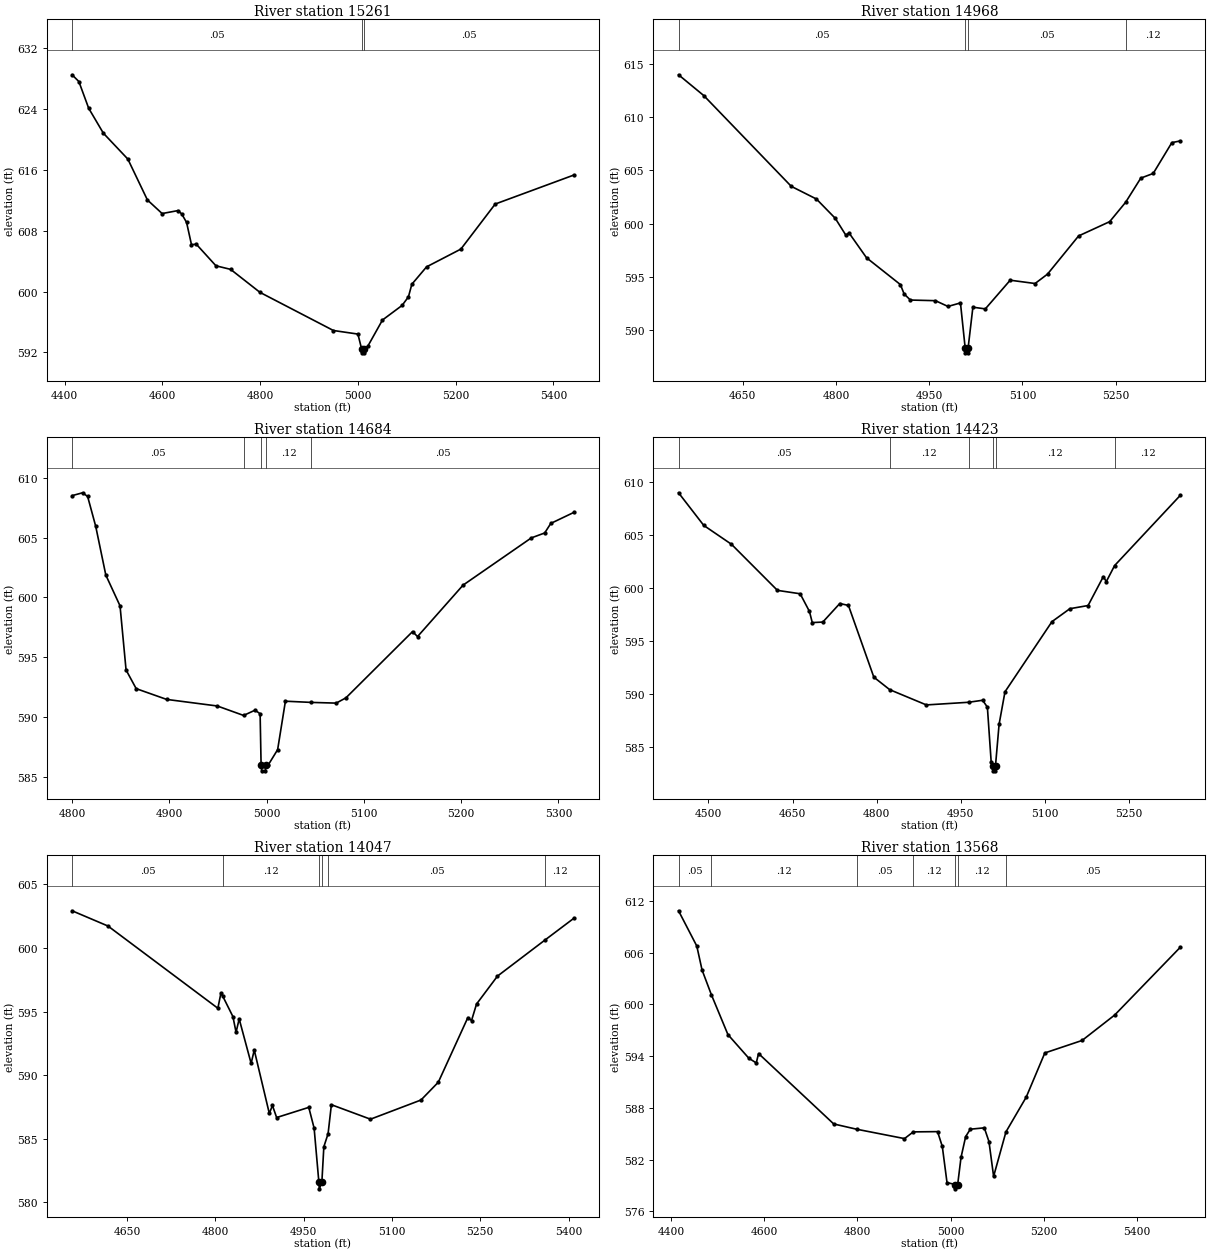
Type RM Length L Ch R = 1 ,15261   ,293,293,293
BEGIN DESCRIPTION:
Mapping XS e052274e
END DESCRIPTION:
XS GIS Cut Line= 3
      2383912.92        7065896.      2383338.29      7065866.49
      2382888.61      7065901.21
#Sta/Elev= 30
  4415.3  628.54  4429.2  627.65  4449.3  624.13  4479.3  620.85  4529.4  617.44
  4569.4  612.06  4599.5  610.27  4632.1  610.66  4639.5  610.22  4649.5  609.11
  4659.5  606.19  4669.6  606.22  4709.6  603.39  4739.6  602.92  4799.7  599.89
  4949.9  594.87    5000   594.4  5007.6  592.43  5008.2  591.93  5011.9  591.93
  5012.5  592.43  5020.1  592.79  5050.2  596.25  5090.3  598.17  5103.3   599.3
  5110.3  600.96  5140.4  603.25  5210.6  605.59  5280.8  611.52  5441.7  615.34
#Mann= 3 ,-1 , 0
  4415.3     .05       0  5007.6    .033       0  5012.5     .05       0
Bank Sta=5007.6,5012.5
XS Rating Curve= 0 ,0
Exp/Cntr=0.3,0.1

Type RM Length L Ch R = 1 ,14968   ,284,284,284
BEGIN DESCRIPTION:
Mapping XS b4464822
END DESCRIPTION:
XS GIS Cut Line= 3
       2383779.3      7065626.91      2383340.02      7065574.82
      2382975.39      7065571.35
#Sta/Elev= 30
  4546.9  613.96  4587.5  612.01  4728.2   603.5  4768.7  602.31    4799   600.5
    4816  598.92    4821  599.14  4849.3   596.8  4903.7  594.29  4909.7  593.41
  4919.8  592.84  4960.1  592.78  4980.2  592.24  5000.3  592.57  5007.8  588.39
  5008.4  587.89  5012.1  587.89  5012.7  588.39  5020.3  592.17  5040.3  592.01
  5080.3   594.7  5120.3  594.39  5140.3  595.27  5190.3  598.85  5240.3  600.19
    5266  602.01  5290.3  604.27  5310.3  604.71  5340.3   607.6  5353.9  607.76
#Mann= 4 ,-1 , 0
  4546.9     .05       0  5007.8    .033       0  5012.7     .05       0
    5266     .12       0
Bank Sta=5007.8,5012.7
XS Rating Curve= 0 ,0
Exp/Cntr=0.3,0.1

Type RM Length L Ch R = 1 ,14684   ,261,261,261
BEGIN DESCRIPTION:
Mapping XS b3eec2ce
END DESCRIPTION:
XS GIS Cut Line= 3
      2383522.28      7065378.63      2383333.08      7065323.08
      2383015.39      7065347.39
#Sta/Elev= 30
    4800   608.5  4810.8  608.74    4816  608.43  4824.3  605.94  4834.7  601.86
  4849.3  599.29  4855.5  593.93  4865.9  592.37  4897.2  591.47  4949.3  590.92
  4976.3  590.13  4988.1  590.57  4993.3  590.27  4994.3     586  4994.9   585.5
  4998.6   585.5  4999.2     586  5001.7     586  5011.3  587.27  5019.3  591.32
  5045.8  591.22  5071.5  591.16  5081.5   591.6    5150  597.14  5155.1  596.72
  5201.9  601.02  5272.1  604.97  5285.8  605.38  5292.1  606.18  5315.8   607.1
#Mann= 5 ,-1 , 0
    4800     .05       0  4976.3     .12       0  4994.3     .07       0
  4999.2     .12       0  5045.8     .05       0
Bank Sta=4994.3,4999.2
XS Rating Curve= 0 ,0
Exp/Cntr=0.3,0.1

Type RM Length L Ch R = 1 ,14423   ,376,376,376
BEGIN DESCRIPTION:
Mapping XS 5894e01b
END DESCRIPTION:
XS GIS Cut Line= 3
      2383833.54      7065189.41      2383297.06      7065109.98
      2382960.56      7065215.21
#Sta/Elev= 30
  4446.7  608.95  4491.7  605.87  4541.1  604.09  4623.1  599.74  4663.6  599.42
  4680.2  597.75  4685.2   596.7    4704  596.75  4734.3   598.5  4749.7  598.32
    4795  591.55  4823.3  590.37  4888.7  588.93  4963.9  589.18    4989  589.37
  4997.5  588.72  5004.3  583.53  5007.1  583.21  5007.7  582.71  5011.4  582.71
    5012  583.21  5018.4  587.11  5028.9  590.17  5112.7  596.79  5144.6  598.01
  5177.1  598.31  5204.3  601.04  5209.6  600.57  5224.4  602.08  5341.6  608.71
#Mann= 6 ,-1 , 0
  4446.7     .05       0  4823.3     .12       0  4963.9     .12       0
  5007.1     .07       0    5012     .12       0  5224.4     .12       0
Bank Sta=5007.1,5012
XS Rating Curve= 0 ,0
Exp/Cntr=0.3,0.1

Type RM Length L Ch R = 1 ,14047   ,479,479,479
BEGIN DESCRIPTION:
Sharps Branch 31.0
END DESCRIPTION:
XS GIS Cut Line= 3
      2383746.46      7064958.11      2383328.85        7064810.
      2382997.77      7065050.31
#Sta/Elev= 30
  4556.9  602.93  4617.9  601.73  4804.5  595.26  4809.8  596.47  4812.7  596.22
  4830.1   594.6  4835.4  593.37  4840.7  594.42    4861  590.92  4866.3  591.97
  4891.9  586.98  4897.2  587.61  4904.3  586.66  4958.9  587.46    4968  585.82
  4976.1  581.55  4976.8  581.05  4981.1  581.55  4984.5  584.36  4991.7  585.39
  4997.3  587.67  5063.7  586.53  5149.5  588.04  5178.9  589.44  5229.1  594.53
  5235.3  594.29  5243.8  595.59  5279.4  597.79  5360.4  600.64  5409.1  602.34
#Mann= 6 ,-1 , 0
  4556.9     .05       0  4812.7     .12       0  4976.1     .07       0
  4981.1     .12       0  4991.7     .05       0  5360.4     .12       0
Bank Sta=4976.1,4981.1
XS Rating Curve= 0 ,0
Exp/Cntr=0.3,0.1

Type RM Length L Ch R = 1 ,13568   ,342,342,342
BEGIN DESCRIPTION:
Sharps Branch 30.0
END DESCRIPTION:
XS GIS Cut Line= 3
       2383797.7      7064562.66       2383221.5      7064466.32
      2382728.03      7064471.95
#Sta/Elev= 30
  4415.8  610.87    4455  606.78  4466.3     604  4486.4  601.12  4521.9   596.5
  4566.6  593.77  4582.7  593.21  4587.7   594.3  4749.1  586.13  4798.2  585.52
  4901.1  584.43    4920  585.21  4972.1  585.24  4982.3  583.52  4992.4  579.33
  5009.8   579.1  5010.6   578.6  5015.3   579.1  5022.5  582.25  5032.5  584.67
  5042.5  585.52  5072.5  585.68  5082.5  584.09  5092.5  580.05    5119  585.21
  5162.5  589.24  5202.5  594.37  5282.5  595.82  5352.5  598.77  5493.5  606.64
#Mann= 7 ,-1 , 0
  4415.8     .05       0  4486.4     .12       0  4798.2     .05       0
    4920     .12       0  5009.8     .07       0  5015.3     .12       0
    5119     .05       0
Bank Sta=5009.8,5015.3
XS Rating Curve= 0 ,0
Exp/Cntr=0.3,0.1

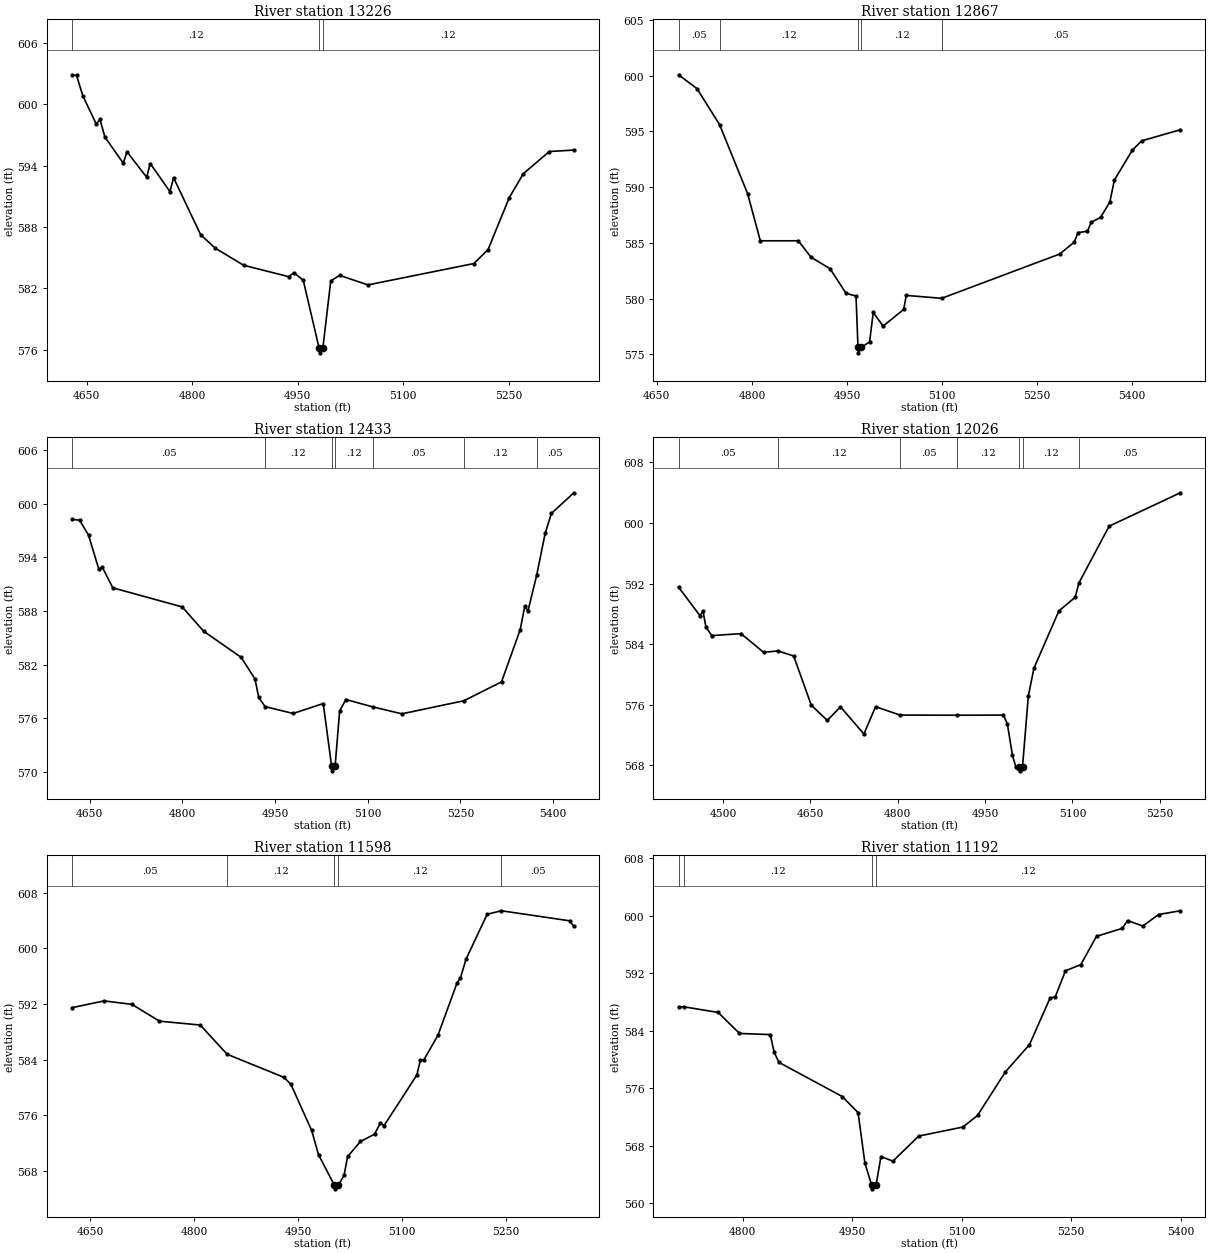
Type RM Length L Ch R = 1 ,13226   ,359,359,359
BEGIN DESCRIPTION:
Sharps Branch 29.0
END DESCRIPTION:
XS GIS Cut Line= 3
      2383683.69      7064265.79        2383329.        7064160.
      2382987.45      7064187.67
#Sta/Elev= 30
  4629.5  602.89  4635.9  602.82  4644.8  600.83  4663.9  598.07  4669.1  598.54
  4676.1  596.81  4702.2  594.25  4707.5  595.36  4735.4  592.88  4740.6  594.21
  4768.5  591.47  4773.7  592.82  4812.1  587.26  4832.7  585.95  4873.2  584.27
    4937  583.16  4944.7  583.54  4957.9   582.8  4980.3  576.21  4981.1  575.71
  4985.8  576.21    4997  582.75  5009.7  583.28  5049.8  582.35  5200.3  584.44
  5220.4   585.8  5250.4  590.86  5270.5  593.22  5307.4  595.39  5342.3  595.53
#Mann= 3 ,-1 , 0
  4629.5     .12       0  4980.3     .07       0  4985.8     .12       0
Bank Sta=4980.3,4985.8
XS Rating Curve= 0 ,0
Exp/Cntr=0.3,0.1

Type RM Length L Ch R = 1 ,12867   ,434,434,434
BEGIN DESCRIPTION:
Sharps Branch 28.0
END DESCRIPTION:
XS GIS Cut Line= 4
      2383648.12      7063839.47       2383387.7      7063842.94
       2383306.1      7063891.55      2382955.43      7064151.95
#Sta/Elev= 30
  4684.2  600.08  4713.3  598.84  4748.9  595.62  4793.3  589.41  4813.3  585.19
  4873.3  585.19  4893.3  583.72  4923.3  582.69  4948.8  580.47  4964.4  580.24
  4967.5  575.64  4968.3  575.14    4973  575.64  4985.8  576.12  4991.6  578.76
  5007.2  577.54  5039.6  579.03  5043.8  580.29  5099.6  580.03  5285.8     584
  5308.8  585.06    5315  585.93  5329.6  586.04  5335.9  586.85  5350.5  587.29
  5365.1  588.67  5372.3  590.64  5400.6  593.31  5415.2  594.15  5476.4  595.15
#Mann= 5 ,-1 , 0
  4684.2     .05       0  4748.9     .12       0  4967.5     .07       0
    4973     .12       0  5099.6     .05       0
Bank Sta=4967.5,4973
XS Rating Curve= 0 ,0
Exp/Cntr=0.3,0.1

Type RM Length L Ch R = 1 ,12433   ,407,407,407
BEGIN DESCRIPTION:
Mapping XS bfc1a31b
END DESCRIPTION:
XS GIS Cut Line= 3
       2383639.9      7063755.72      2383275.28      7063576.01
      2382872.85      7063525.39
#Sta/Elev= 30
  4621.6  598.24  4633.8  598.13  4648.2  596.47    4665  592.64  4670.6  592.88
  4687.5  590.58  4799.8  588.45  4834.4  585.74  4895.2  582.81  4917.7  580.39
  4923.6  578.34  4933.9  577.31  4979.4  576.54  5028.1  577.65  5041.7  570.63
  5042.6  570.13  5047.3  570.63  5054.6  576.82  5064.7   578.1  5108.1  577.28
  5155.4   576.5  5255.7  577.96  5316.6  580.07  5346.9  585.91  5354.3  588.54
  5359.3  587.96  5373.5  591.98  5387.2  596.65  5397.3  598.89  5433.7   601.2
#Mann= 7 ,-1 , 0
  4621.6     .05       0  4933.9     .12       0  5041.7     .07       0
  5047.3     .12       0  5108.1     .05       0  5255.7     .12       0
  5373.5     .05       0
Bank Sta=5041.7,5047.3
XS Rating Curve= 0 ,0
Exp/Cntr=0.3,0.1

Type RM Length L Ch R = 1 ,12026   ,428,428,428
BEGIN DESCRIPTION:
Mapping XS 7510a52c
END DESCRIPTION:
XS GIS Cut Line= 3
      2383795.79      7063368.87      2383270.62      7063320.05
      2382984.14      7063148.59
#Sta/Elev= 30
  4423.8  591.54  4460.7  587.76  4465.7   588.4  4470.8  586.29  4480.8  585.14
    4531   585.4  4569.9  582.93  4594.4  583.12  4621.4  582.45  4651.6  575.96
  4679.2  573.94  4701.8  575.74    4742  572.15    4762  575.76    4804  574.65
  4901.9  574.63  4981.4  574.65  4988.1  573.51    4997  569.32  5002.8   567.8
  5008.6  567.79  5009.4  567.29  5014.2  567.79  5024.2  577.17  5033.9  580.86
  5076.7   588.4  5104.6  590.19  5111.1   592.1  5162.9  599.58  5285.1  603.99
#Mann= 7 ,-1 , 0
  4423.8     .05       0  4594.4     .12       0    4804     .05       0
  4901.9     .12       0  5008.6     .07       0  5014.2     .12       0
  5111.1     .05       0
Bank Sta=5008.6,5014.2
XS Rating Curve= 0 ,0
Exp/Cntr=0.3,0.1

Type RM Length L Ch R = 1 ,11598   ,406,406,406
BEGIN DESCRIPTION:
Mapping XS 34c9e004
END DESCRIPTION:
XS GIS Cut Line= 3
      2383755.27      7062987.15      2383372.25      7062982.81
      2383035.84      7063045.75
#Sta/Elev= 30
  4623.5  591.46  4669.8  592.43  4709.8  591.94  4749.8  589.52  4808.8  588.96
  4847.6  584.76  4929.8  581.44  4939.8  580.44  4969.8   573.8  4979.8   570.3
  5002.8  565.91  5003.7  565.41  5008.5  565.91  5016.7  567.38  5021.8  570.06
  5040.4  572.22  5060.7  573.27  5069.3   574.9  5074.4  574.49  5121.8  581.77
    5127  583.93  5132.1  583.97  5152.3  587.48  5179.7  594.95  5184.7  595.68
    5193  598.45  5223.5  604.89  5244.1  605.39  5342.6  603.95  5348.8  603.14
#Mann= 5 ,-1 , 0
  4623.5     .05       0  4847.6     .12       0  5002.8     .07       0
  5008.5     .12       0  5244.1     .05       0
Bank Sta=5002.8,5008.5
XS Rating Curve= 0 ,0
Exp/Cntr=0.3,0.1

Type RM Length L Ch R = 1 ,11192   ,357,357,357
BEGIN DESCRIPTION:
Mapping XS 2ee7af86
END DESCRIPTION:
XS GIS Cut Line= 4
      2383745.78      7062785.25      2383486.11      7062676.38
      2383318.66      7062656.76      2383156.71        7062830.
#Sta/Elev= 30
  4712.3  587.33  4719.4  587.35  4766.6  586.56  4795.8  583.64  4837.9  583.48
  4843.3  581.02  4849.8  579.62  4936.5  574.87  4958.2  572.63  4967.6  565.59
  4976.9  562.53  4977.9  562.03  4982.8  562.53  4989.6  566.52  5005.9  565.88
  5041.3  569.37  5101.7  570.62  5121.8  572.23  5159.8  578.27    5193  582.09
  5221.3  588.59  5228.2  588.71  5242.3  592.36  5263.3  593.21  5284.8  597.15
    5320  598.25  5327.3  599.34  5348.3  598.58  5369.8  600.18  5399.6   600.7
#Mann= 4 ,-1 , 0
  4712.3     .05       0  4719.4     .12       0  4976.9     .07       0
  4982.8     .12       0
Bank Sta=4976.9,4982.8
XS Rating Curve= 0 ,0
Exp/Cntr=0.3,0.1

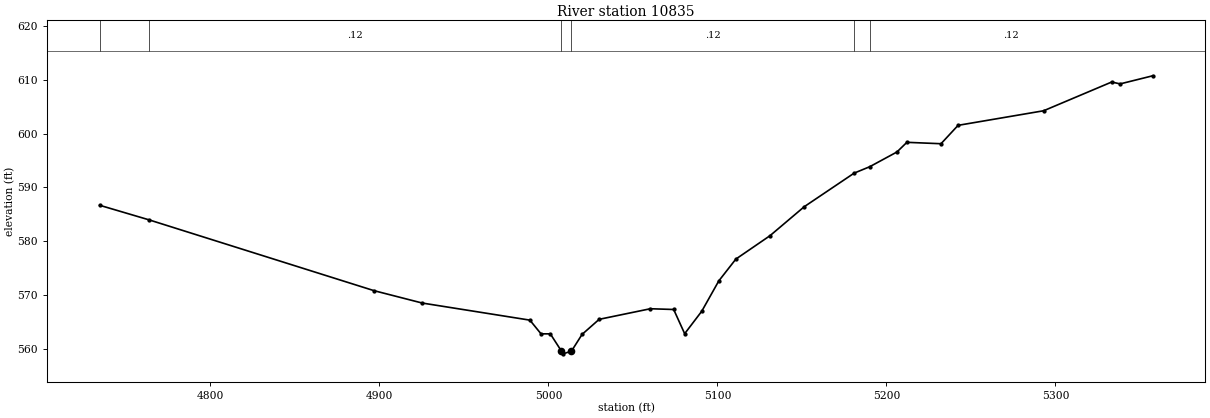
Type RM Length L Ch R = 1 ,10835   ,284,284,284
BEGIN DESCRIPTION:
Mapping XS 563cd17e
END DESCRIPTION:
XS GIS Cut Line= 3
       2383780.7      7062537.78      2383581.03      7062366.33
      2383225.13      7062312.07
#Sta/Elev= 30
  4734.4  586.69  4763.6  583.98  4896.8   570.8  4925.3   568.5    4989  565.32
  4995.6  562.77  5001.1  562.77  5007.7  559.55  5008.6  559.05  5013.6  559.55
  5019.9  562.67    5030  565.47  5060.3  567.44  5074.1   567.3  5080.6   562.8
  5090.7  566.97  5100.8  572.62  5110.9  576.68  5131.1  581.03  5151.4  586.43
  5180.9  592.67  5190.1  593.86  5206.2   596.6  5212.1   598.4  5232.3  598.14
  5242.4  601.56    5293  604.27  5333.3  609.62  5338.3  609.27  5357.6  610.78
#Mann= 6 ,-1 , 0
  4734.4     .05       0  4763.6     .12       0  5007.7     .07       0
  5013.6     .12       0  5180.9     .05       0  5190.1     .12       0
Bank Sta=5007.7,5013.6
XS Rating Curve= 0 ,0
Exp/Cntr=0.3,0.1