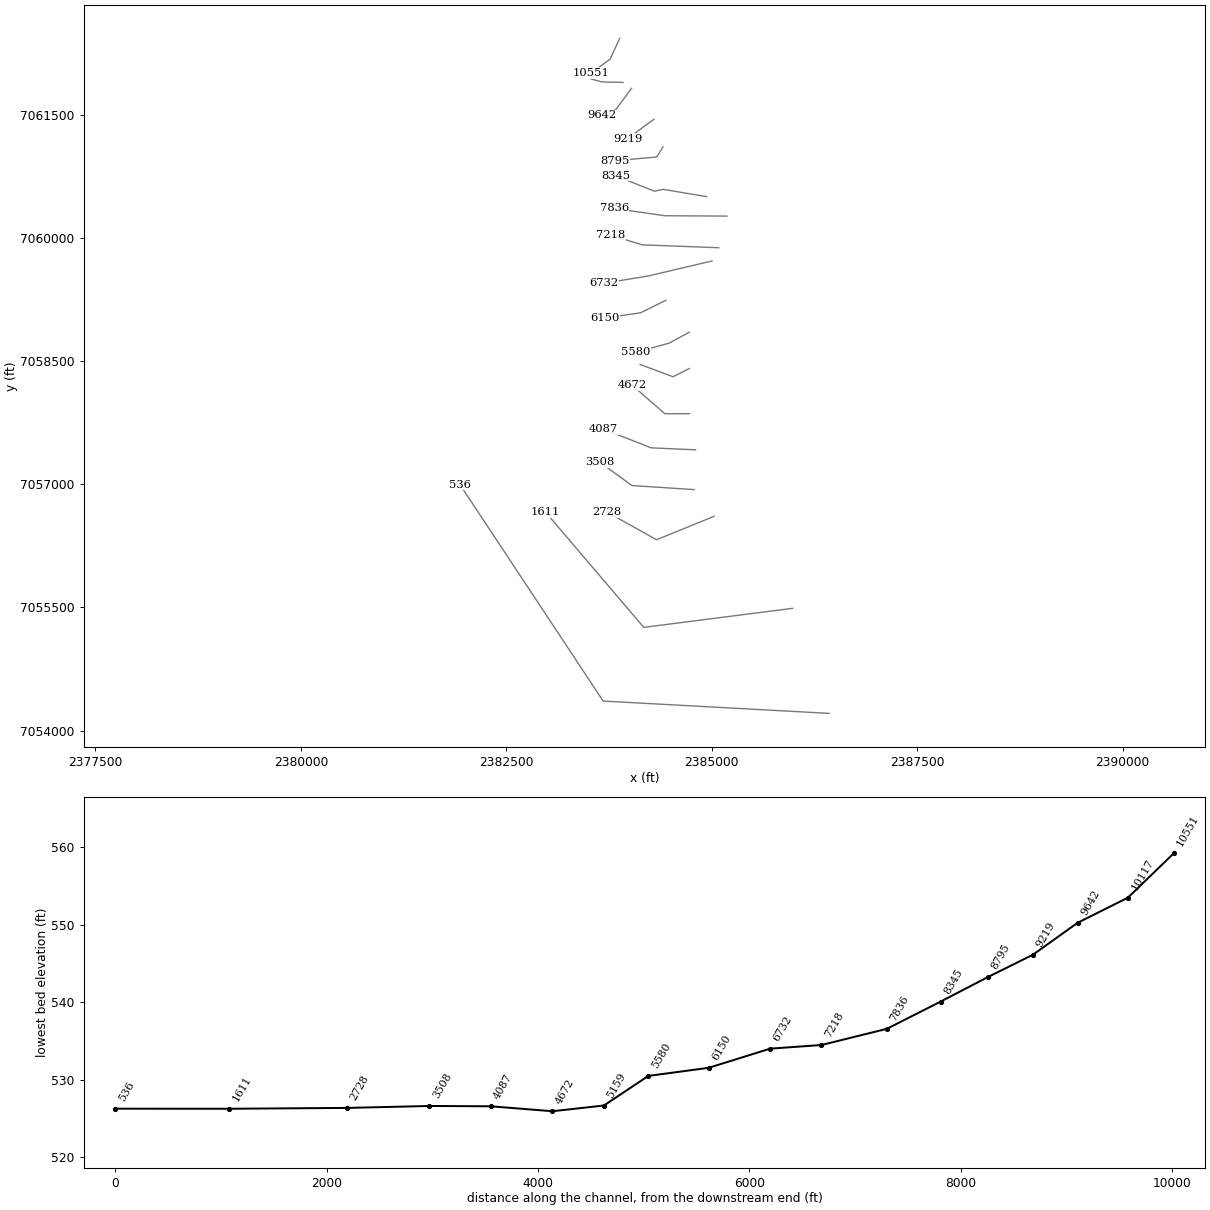
HEC-RAS study Sharps Branch.prj: Sharps Branch Base Level Engineering

--- Sharps Branch.g01 (geometry) --- (continued)

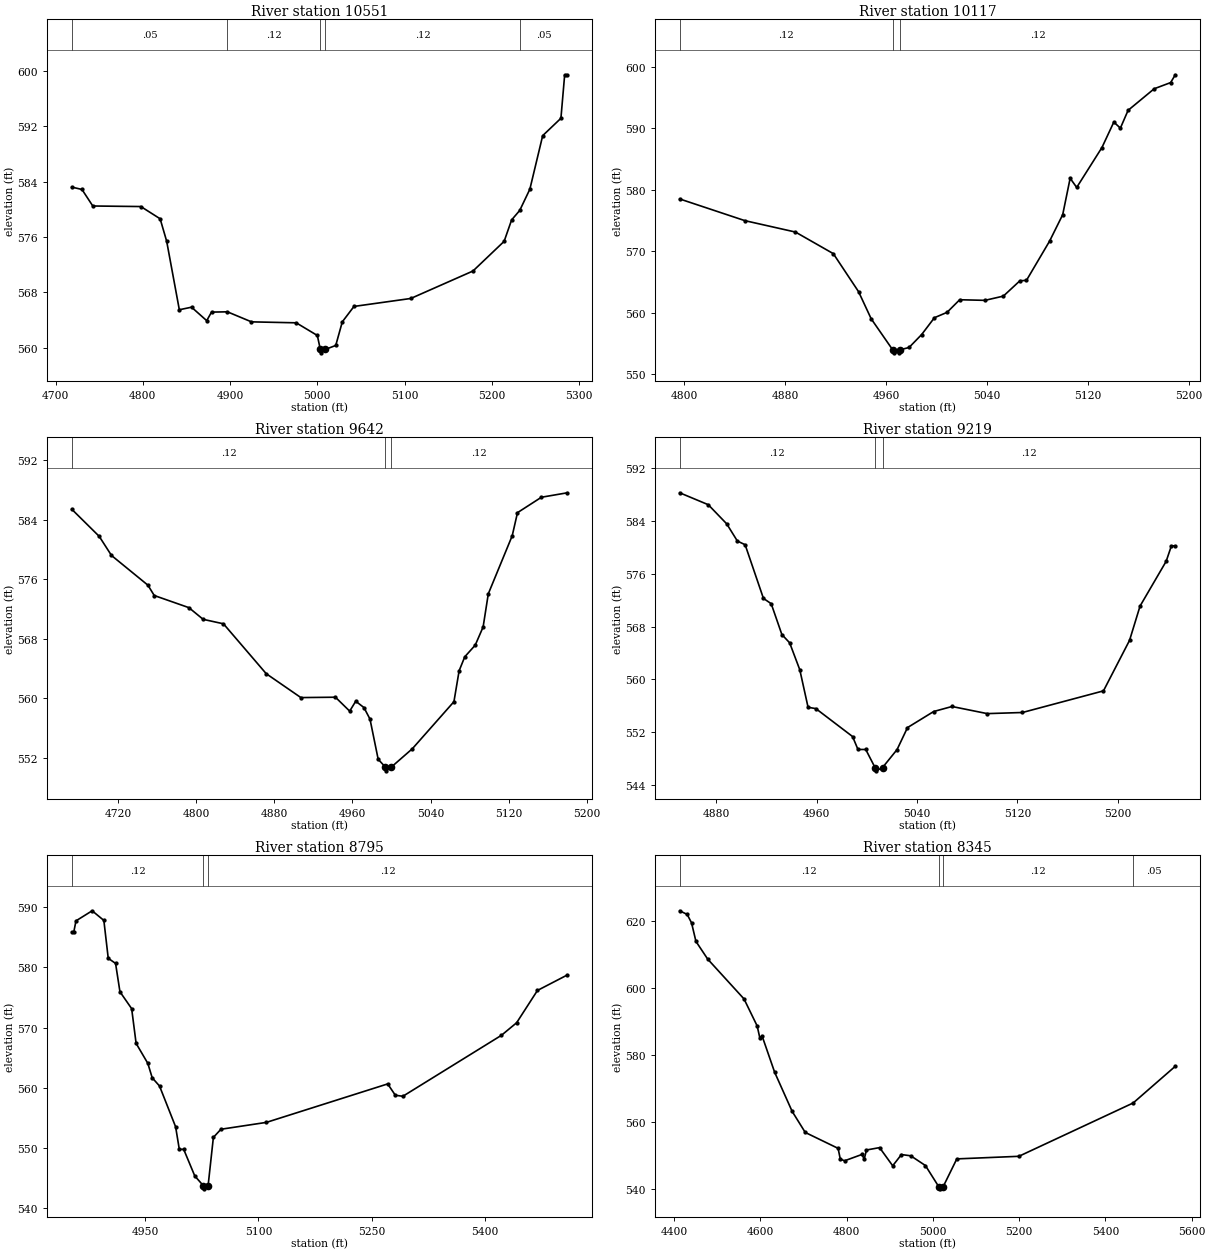
Type RM Length L Ch R = 1 ,10551   ,434,434,434
BEGIN DESCRIPTION:
Sharps Branch 23.0
END DESCRIPTION:
XS GIS Cut Line= 3
      2383880.63      7062431.88      2383762.28      7062176.47
      2383528.99      7062009.99
#Sta/Elev= 30
  4718.5  583.19  4730.2  582.85  4742.6  580.46  4797.7  580.38  4819.8  578.61
  4827.3  575.36  4841.8  565.46  4855.8  565.83  4873.2  563.88  4878.7  565.12
  4896.9  565.16  4924.5  563.71  4975.8  563.57    5000  561.74  5003.4  559.73
  5004.3  559.23  5009.3  559.73  5021.1   560.3  5028.6  563.71    5042  565.94
  5107.1  567.09  5178.4  571.06  5214.1  575.35  5222.7  578.45    5232  579.82
  5243.6  582.89  5258.3  590.63  5279.2  593.14  5283.5  599.43  5286.6  599.43
#Mann= 5 ,-1 , 0
  4718.5     .05       0  4896.9     .12       0  5003.4     .07       0
  5009.3     .12       0    5232     .05       0
Bank Sta=5003.4,5009.3
XS Rating Curve= 0 ,0
Exp/Cntr=0.3,0.1

Type RM Length L Ch R = 1 ,10117   ,475,475,475
BEGIN DESCRIPTION:
Sharps Branch 22.0
END DESCRIPTION:
XS GIS Cut Line= 3
       2383920.7      7061895.29      2383664.32      7061900.96
      2383532.93      7061936.66
#Sta/Elev= 30
  4796.6  578.51  4848.3  574.98  4888.3  573.13  4918.3  569.62  4938.3  563.44
  4948.3  559.03  4965.3     554  4966.3   553.5  4970.3   553.5  4971.3     554
  4978.3  554.37  4988.3  556.48  4998.4  559.21  5008.4  560.08  5018.4  562.13
  5038.4  562.03    5053  562.72  5066.1  565.21  5071.3  565.28  5089.6  571.65
    5100  575.95  5105.9  581.87  5111.1  580.38  5131.1  586.87  5140.5     591
  5145.7  590.02  5151.8  592.91  5172.5  596.42  5185.5  597.42  5189.2  598.69
#Mann= 3 ,-1 , 0
  4796.6     .12       0  4965.3     .07       0  4971.3     .12       0
Bank Sta=4965.3,4971.3
XS Rating Curve= 0 ,0
Exp/Cntr=0.3,0.1

Type RM Length L Ch R = 1 ,9642    ,423,423,423
BEGIN DESCRIPTION:
Sharps Branch 21.0
END DESCRIPTION:
XS GIS Cut Line= 3
      2384024.73      7061822.51        2383829.        7061560.
        2383661.       7061494.7
#Sta/Elev= 30
  4672.5   585.4  4700.6  581.76  4713.2  579.19  4750.5   575.2    4757  573.81
  4792.5  572.18  4807.1  570.61  4827.9  570.01  4871.7  563.31  4907.2   560.1
  4942.6  560.15  4957.2  558.28  4963.4  559.61  4971.8  558.76    4978  557.21
  4986.4  551.81  4993.8  550.76  4994.8  550.26  4999.8  550.76  5021.4  553.23
    5064  559.55  5069.3   563.7  5075.1  565.58  5085.8  567.14  5093.9  569.59
  5099.2  574.04  5123.7  581.84  5129.1  584.94  5153.6  587.01  5180.2  587.61
#Mann= 3 ,-1 , 0
  4672.5     .12       0  4993.8     .07       0  4999.8     .12       0
Bank Sta=4993.8,4999.8
XS Rating Curve= 0 ,0
Exp/Cntr=0.3,0.1

Type RM Length L Ch R = 1 ,9219    ,424,424,424
BEGIN DESCRIPTION:
Sharps Branch 20.0
END DESCRIPTION:
XS GIS Cut Line= 3
      2384296.49      7061445.45        2384179.        7061360.
      2383978.98      7061209.99
#Sta/Elev= 30
  4850.7  588.31  4873.5   586.5  4888.2   583.6  4896.7  580.99  4902.9  580.43
  4917.5  572.29  4923.7  571.48  4932.2  566.81  4938.4  565.55  4946.5  561.46
  4953.1  555.77  4959.3  555.57  4988.6  551.33  4992.9  549.37  4999.1  549.37
  5006.5  546.63  5007.5  546.13  5012.5  546.63  5024.1  549.36  5032.4  552.69
  5053.3  555.13  5067.9  555.89    5096  554.81  5124.1  554.98  5188.7  558.26
  5209.5  565.92  5217.9  571.13  5238.7  577.91  5242.9  580.26    5246  580.26
#Mann= 3 ,-1 , 0
  4850.7     .12       0  5006.5     .07       0  5012.5     .12       0
Bank Sta=5006.5,5012.5
XS Rating Curve= 0 ,0
Exp/Cntr=0.3,0.1

Type RM Length L Ch R = 1 ,8795    ,450,450,450
BEGIN DESCRIPTION:
Sharps Branch 19.0
END DESCRIPTION:
XS GIS Cut Line= 3
      2384406.86      7061109.92      2384332.23       7060986.7
      2383822.07      7060941.73
#Sta/Elev= 30
  4852.9  585.86  4855.6  585.86  4858.5   587.7  4879.9  589.37  4895.4  587.77
  4901.2  581.49  4910.9  580.64  4916.7  575.94  4932.2  573.14  4938.1  567.38
  4953.6  564.07  4959.4  561.68  4969.1  560.31  4990.4  553.55  4995.3  549.81
  5001.1  549.81  5015.8  545.39  5027.3  543.76  5028.3  543.26  5033.4  543.76
  5040.4  551.79  5050.4  553.14  5110.6  554.28  5271.2  560.66  5281.3  558.78
  5291.3  558.61  5421.8  568.72  5441.9   570.8  5469.5  576.16  5509.1  578.73
#Mann= 3 ,-1 , 0
  4852.9     .12       0  5027.3     .07       0  5033.4     .12       0
Bank Sta=5027.3,5033.4
XS Rating Curve= 0 ,0
Exp/Cntr=0.3,0.1

Type RM Length L Ch R = 1 ,8345    ,509,509,509
BEGIN DESCRIPTION:
Sharps Branch 18.0
END DESCRIPTION:
XS GIS Cut Line= 4
      2384936.16      7060503.84      2384411.44      7060592.38
      2384302.06      7060570.25      2383832.33      7060757.46
#Sta/Elev= 30
  4412.7   622.9  4430.1  621.81  4440.2  619.31  4450.4  613.78  4477.7   608.5
  4561.9  596.64  4592.4  588.59  4598.7  584.95  4603.8  585.61  4632.9  574.81
  4673.5  563.15  4703.9  556.87  4780.1  552.13  4785.2  548.91  4795.2  548.43
  4835.5  550.32  4840.6   548.9  4845.9  551.64  4876.3  552.35  4906.7  546.94
    4927  550.28  4948.6  549.91  4982.6  547.01  5014.2  540.57  5015.5  540.07
  5023.2  540.57  5055.4  548.99  5199.3  549.76  5464.4  565.65  5562.1  576.58
#Mann= 4 ,-1 , 0
  4412.7     .12       0  5014.2     .07       0  5023.2     .12       0
  5464.4     .05       0
Bank Sta=5014.2,5023.2
XS Rating Curve= 0 ,0
Exp/Cntr=0.3,0.1

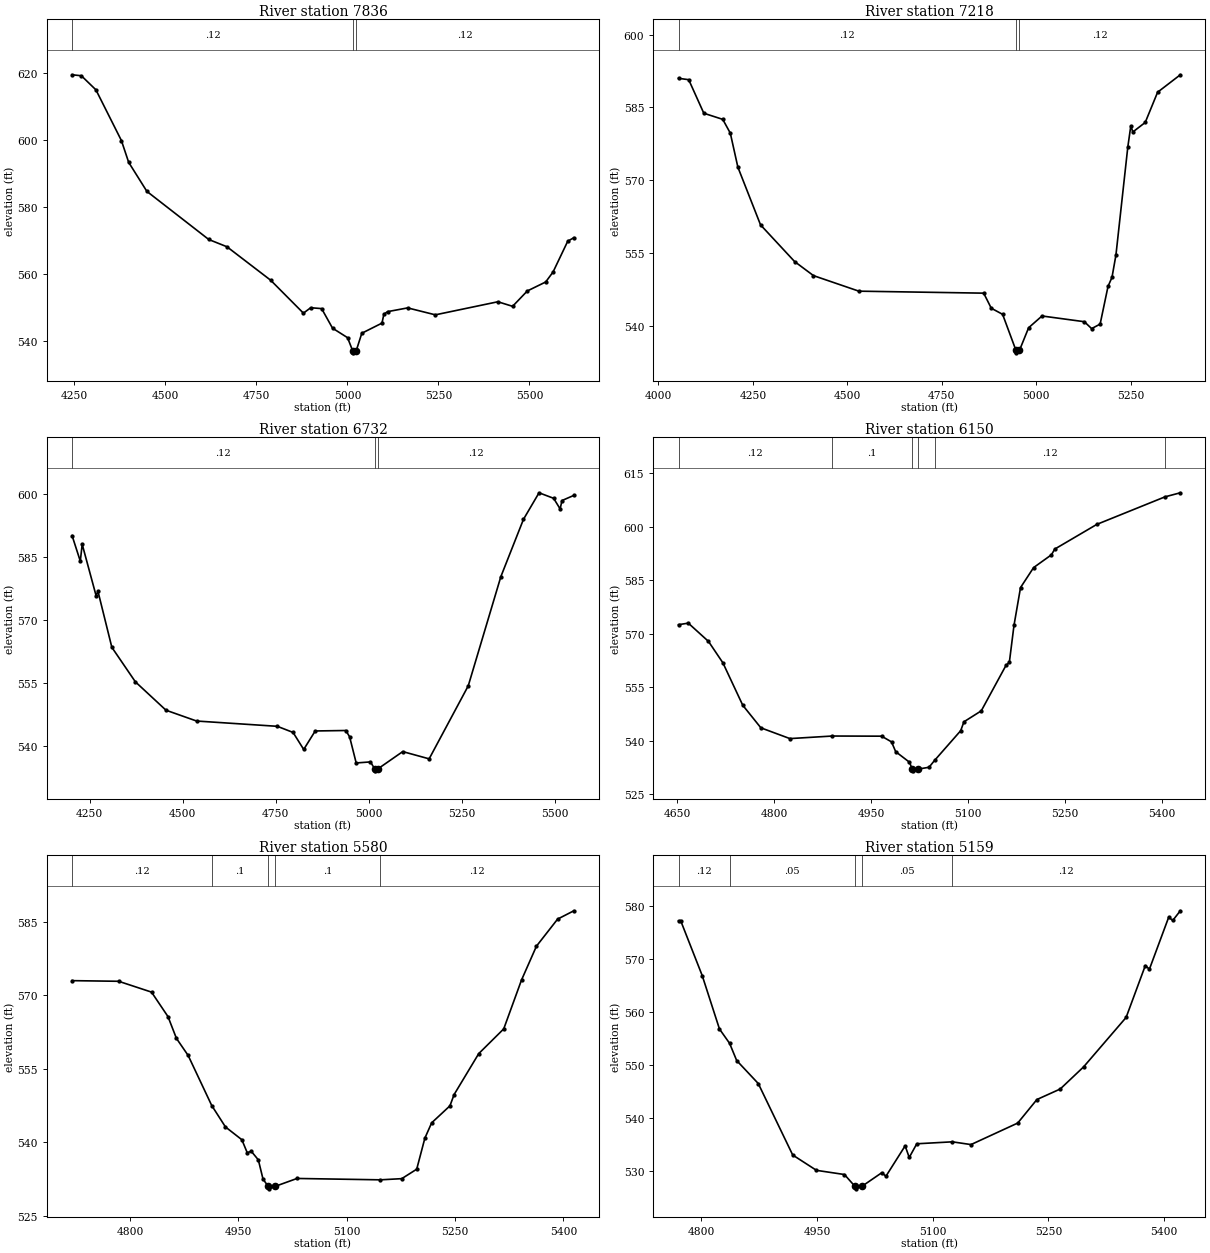
Type RM Length L Ch R = 1 ,7836    ,618,618,618
BEGIN DESCRIPTION:
Mapping XS 9426cea3
END DESCRIPTION:
XS GIS Cut Line= 3
      2385184.45      7060266.73       2384431.4      7060271.07
      2383812.39      7060359.81
#Sta/Elev= 30
  4243.7  619.52  4269.2  619.23  4309.2  615.03  4379.2   599.9  4399.2  593.39
  4449.2  584.73  4619.2  570.37  4669.2   568.2  4789.2  558.22  4879.2  548.39
  4899.2  550.01  4929.2  549.75  4959.2  543.91  5000.5  541.07  5014.9  537.05
  5016.2  536.55  5023.9  537.05  5039.6   542.4    5095  545.42  5100.2  548.06
  5110.3  548.84  5165.6  549.96  5241.6  547.89  5413.4  551.79  5453.8  550.43
  5494.2  555.01  5544.7  557.69  5564.9  560.66  5605.3  569.86  5622.1  570.91
#Mann= 3 ,-1 , 0
  4243.7     .12       0  5014.9     .07       0  5023.9     .12       0
Bank Sta=5014.9,5023.9
XS Rating Curve= 0 ,0
Exp/Cntr=0.3,0.1

Type RM Length L Ch R = 1 ,7218    ,486,486,486
BEGIN DESCRIPTION:
Sharps Branch 15.0
END DESCRIPTION:
XS GIS Cut Line= 3
      2385085.89      7059881.32      2384156.23      7059916.47
      2383776.03      7060032.36
#Sta/Elev= 30
  4053.2  590.99  4080.1  590.71  4120.1   583.8  4170.2  582.54  4190.2   579.7
  4210.2   572.7  4270.2  560.81  4360.3  553.26  4410.3  550.36  4530.4  547.16
  4860.7  546.75  4880.7  543.65  4910.7  542.39  4946.1  534.96  4947.4  534.46
  4955.3  534.96  4979.6  539.63    5015  542.05    5127  540.87  5146.3  539.45
  5168.8  540.38  5189.7  548.15  5200.2  550.01  5210.6  554.59    5242  576.83
    5250  581.21  5255.3  579.94  5288.1   581.9  5320.9  588.13    5381  591.72
#Mann= 3 ,-1 , 0
  4053.2     .12       0  4946.1     .07       0  4955.3     .12       0
Bank Sta=4946.1,4955.3
XS Rating Curve= 0 ,0
Exp/Cntr=0.3,0.1

Type RM Length L Ch R = 1 ,6732    ,582,582,582
BEGIN DESCRIPTION:
Mapping XS 9ecd9ec9
END DESCRIPTION:
XS GIS Cut Line= 3
       2385004.5       7059720.3      2384224.53       7059536.7
      2383685.43      7059449.46
#Sta/Elev= 30
  4202.9   590.1    4225     584  4230.1  588.02  4267.4  575.77  4272.5  576.79
  4309.7  563.45  4372.9  555.22  4455.1  548.45  4537.3  545.87    4754  544.61
  4796.3  543.15  4824.9  539.09  4855.8   543.5    4938  543.61  4948.2   542.1
  4965.8  535.87  5004.2  536.12  5015.3  534.49  5016.6  533.99  5024.6  534.49
  5090.8  538.58  5161.7  536.85  5266.7  554.26  5354.2  580.29    5415  593.98
  5456.8  600.31    5496  598.99  5513.4  596.46  5518.5  598.46  5550.3  599.69
#Mann= 3 ,-1 , 0
  4202.9     .12       0  5015.3     .07       0  5024.6     .12       0
Bank Sta=5015.3,5024.6
XS Rating Curve= 0 ,0
Exp/Cntr=0.3,0.1

Type RM Length L Ch R = 1 ,6150    ,570,570,570
BEGIN DESCRIPTION:
Mapping XS 6e53e5db
END DESCRIPTION:
XS GIS Cut Line= 3
      2384440.52      7059240.25      2384134.99      7059089.22
      2383704.42      7059026.72
#Sta/Elev= 30
  4652.5  572.49  4667.6  572.92  4698.8   567.8  4721.1  561.79  4751.8   549.9
  4779.8  543.57  4824.7  540.55  4890.3  541.27  4966.5  541.23  4981.8  539.63
  4988.3  536.88  5009.5  533.94  5013.9  532.01  5015.3  531.51  5023.3  532.01
  5039.8  532.51  5048.5  534.45  5088.8  542.77  5093.8  545.26  5120.6  548.33
    5159  561.13    5164  561.89  5171.2  572.29  5181.3  582.89  5201.5  588.49
  5229.1  592.08  5234.2  593.68  5299.3  600.61  5404.7  608.33  5428.4  609.47
#Mann= 6 ,-1 , 0
  4652.5     .12       0  4890.3      .1       0  5013.9     .07       0
  5023.3      .1       0  5048.5     .12       0  5404.7     .05       0
Bank Sta=5013.9,5023.3
XS Rating Curve= 0 ,0
Exp/Cntr=0.3,0.1

Type RM Length L Ch R = 1 ,5580    ,421,421,421
BEGIN DESCRIPTION:
Sharps Branch 12.0
END DESCRIPTION:
XS GIS Cut Line= 3
      2384725.71      7058851.38      2384481.56        7058719.
      2384078.98        7058610.
#Sta/Elev= 30
  4719.8  572.99  4784.3  572.86  4829.8  570.65  4852.6  565.65  4864.3   561.2
  4880.5  557.72  4913.2  547.48  4932.2  543.11  4954.9   540.5  4962.3  537.86
    4968  538.13  4977.7  536.39  4984.2  532.46  4991.4  530.97  4992.7  530.47
  5000.9  530.97  5031.3  532.59  5146.7  532.31  5176.3  532.55    5197  534.48
  5208.3  540.82  5217.7  543.95    5243  547.42  5248.8  549.73  5282.9  558.09
  5317.5  563.14  5342.1  573.11  5362.8  580.03  5392.1  585.56  5414.6  587.26
#Mann= 5 ,-1 , 0
  4719.8     .12       0  4913.2      .1       0  4991.4     .07       0
  5000.9      .1       0  5146.7     .12       0
Bank Sta=4991.4,5000.9
XS Rating Curve= 0 ,0
Exp/Cntr=0.3,0.1

Type RM Length L Ch R = 1 ,5159    ,487,487,487
BEGIN DESCRIPTION:
Sharps Branch 11.0
END DESCRIPTION:
XS GIS Cut Line= 3
      2384728.98      7058409.99        2384529.        7058310.
      2384128.98      7058460.01
#Sta/Elev= 30
  4770.4  577.22  4773.2  577.22  4801.1  566.88  4823.5  556.79  4836.6   554.1
  4845.8  550.85  4873.8  546.51  4918.5  533.02  4949.3  530.13  4985.6  529.34
    4999  527.14  5000.4  526.64  5008.5  527.14    5034  529.68  5039.4  529.02
  5064.3  534.75  5069.6  532.56  5079.4  535.14  5125.5  535.51  5149.7  534.99
  5210.3  539.05  5235.2  543.49  5265.4  545.47  5295.7  549.64  5350.9  558.98
  5375.8  568.77  5381.1  568.08  5406.1  577.88  5411.4  577.28  5421.2   579.1
#Mann= 5 ,-1 , 0
  4770.4     .12       0  4836.6     .05       0    4999    .033       0
  5008.5     .05       0  5125.5     .12       0
Bank Sta=4999,5008.5
XS Rating Curve= 0 ,0
Exp/Cntr=0.3,0.1

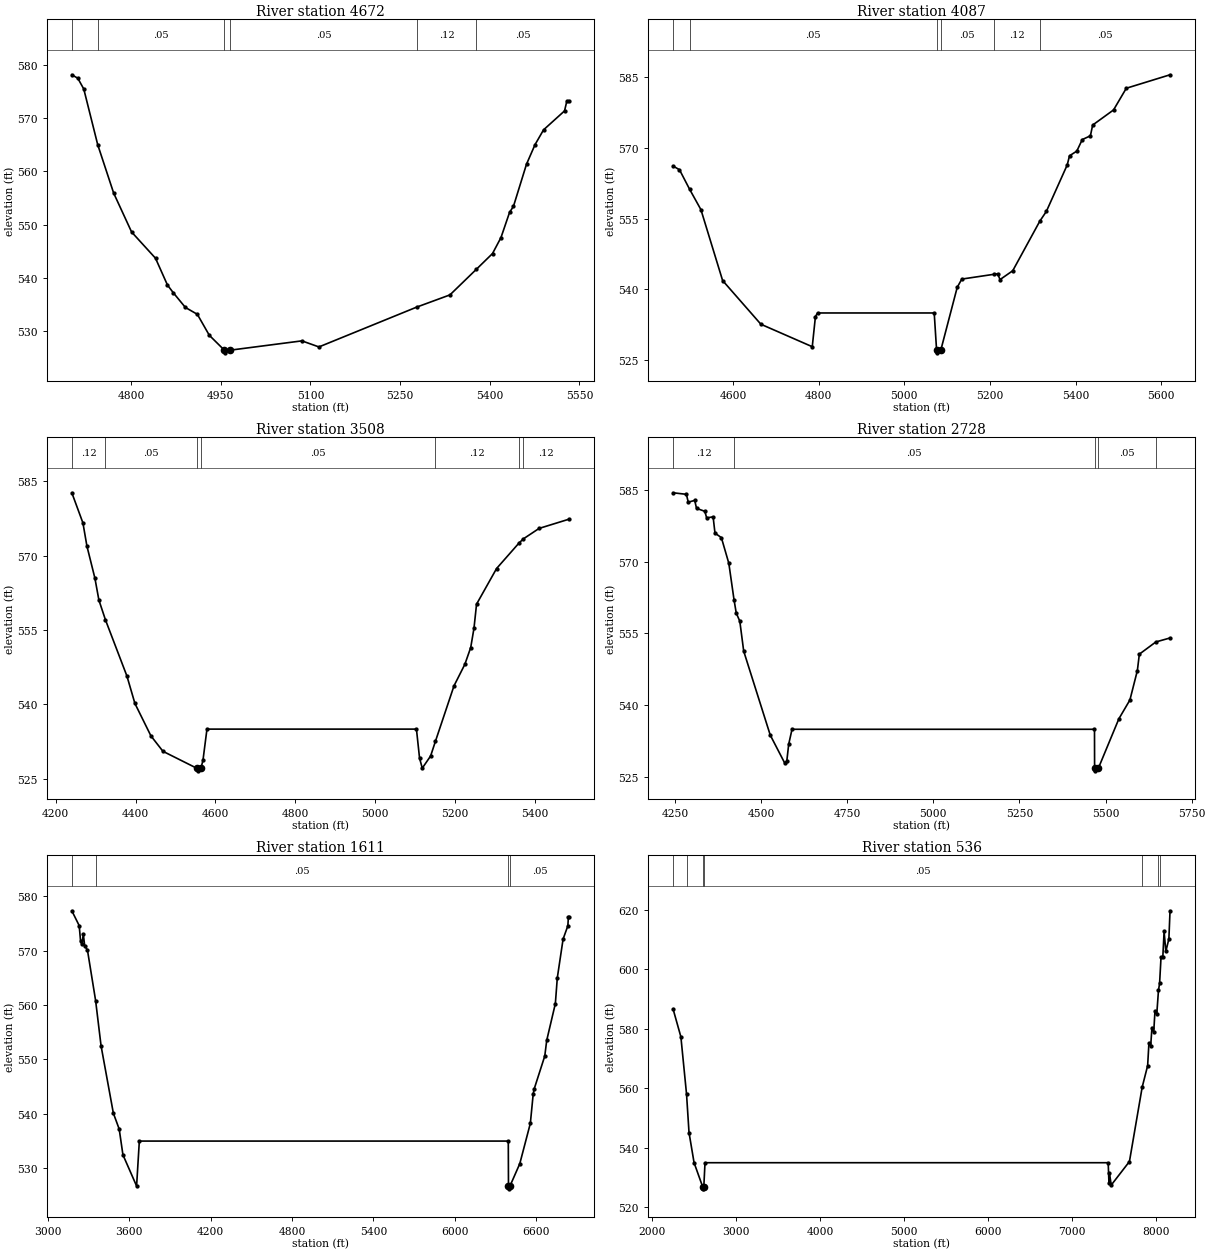
Type RM Length L Ch R = 1 ,4672    ,585,585,585
BEGIN DESCRIPTION:
Sharps Branch 10.0
END DESCRIPTION:
XS GIS Cut Line= 3
      2384728.95        7057860.        2384429.        7057860.
      2384028.97      7058210.03
#Sta/Elev= 30
  4700.7  578.16  4710.7  577.51  4720.7  575.48    4744  565.02  4770.7  555.92
  4800.7  548.61  4840.7  543.68  4860.7  538.64  4870.7  537.16  4890.7  534.43
  4910.7  533.14  4930.7   529.2  4955.9   526.4  4957.2   525.9  4965.5   526.4
  5085.6  528.15  5114.1  527.01  5277.8   534.5  5333.3  536.79  5377.4  541.59
  5404.5  544.56  5418.7  547.57    5433  552.28  5439.6  553.45  5461.4  561.36
  5475.7  565.04  5489.9  567.81    5525  571.37  5528.8  573.17  5532.2  573.17
#Mann= 6 ,-1 , 0
  4700.7     .12       0    4744     .05       0  4955.9    .033       0
  4965.5     .05       0  5277.8     .12       0  5377.4     .05       0
Bank Sta=4955.9,4965.5
XS Rating Curve= 0 ,0
Exp/Cntr=0.3,0.1

Type RM Length L Ch R = 1 ,4087    ,579,579,579
BEGIN DESCRIPTION:
Sharps Branch 9.0
END DESCRIPTION:
XS GIS Cut Line= 3
       2384804.1      7057420.01      2384262.71      7057444.25
      2383686.32      7057671.49
#Sta/Elev= 30
  4459.4  566.18  4474.5  565.39  4498.1  561.26  4524.6  556.92  4575.3  541.88
  4664.7  532.61  4784.8  527.84  4792.2  534.24  4797.2     535  5069.8     535
  5075.4  527.04  5076.7  526.54    5085  527.04  5123.6  540.45  5134.3  542.19
    5209   543.2  5218.2   543.3  5223.6  542.08  5253.3  543.96  5316.6  554.48
  5331.9  556.55  5380.6   566.4    5386  568.35    5403  569.34  5415.8  571.79
  5434.8  572.59  5440.1  574.87  5488.9  578.08  5518.7  582.68  5620.9  585.54
#Mann= 6 ,-1 , 0
  4459.4     .12       0  4498.1     .05       0  5075.4    .033       0
    5085     .05       0    5209     .12       0  5316.6     .05       0
Bank Sta=5075.4,5085
XS Rating Curve= 0 ,0
Exp/Cntr=0.3,0.1

Type RM Length L Ch R = 1 ,3508    ,780,780,780
BEGIN DESCRIPTION:
Sharps Branch 8.0
END DESCRIPTION:
XS GIS Cut Line= 3
      2384786.71      7056935.63       2384028.7      7056984.88
      2383637.39      7057271.41
#Sta/Elev= 30
  4240.4  582.69  4268.2   576.6  4278.2  571.93  4298.2  565.45  4308.2  561.03
  4324.5  557.07  4378.4   545.7  4398.4  540.17  4438.5  533.63  4468.6  530.52
  4553.9  527.08  4555.3  526.58  4563.6  527.08  4568.8   528.7  4578.8     535
  5103.4     535  5111.2  529.13    5118  527.12  5138.9  529.58  5151.1  532.58
  5197.5  543.74  5224.6  548.07  5239.3  551.46  5247.5  555.37  5253.9  560.21
  5304.1  567.41    5360  572.53  5371.1  573.39  5410.6   575.5    5485  577.35
#Mann= 7 ,-1 , 0
  4240.4     .12       0  4324.5     .05       0  4553.9    .033       0
  4563.6     .05       0  5151.1     .12       0    5360     .05       0
  5371.1     .12       0
Bank Sta=4553.9,4563.6
XS Rating Curve= 0 ,0
Exp/Cntr=0.3,0.1

Type RM Length L Ch R = 1 ,2728    ,1117,1117,1117
BEGIN DESCRIPTION:
Sharps Branch 5.0
END DESCRIPTION:
XS GIS Cut Line= 3
      2385029.03      7056610.01      2384329.04      7056324.98
      2383729.03      7056659.99
#Sta/Elev= 30
  4244.2  584.34    4283  584.02  4288.4  582.38  4307.1  582.75  4312.5  581.09
  4336.5  580.47  4341.9   579.1  4360.6  579.32    4366  575.93  4384.6  574.98
  4406.2  569.63  4421.2  562.07  4427.8  559.23  4438.1  557.55  4449.4   551.3
  4526.5  533.78  4568.2  527.99  4574.6  528.39    4580  531.86  4589.7     535
  5467.9     535  5468.2  526.83  5469.7  526.33  5478.9  526.83  5538.7  537.19
  5570.7  541.11  5592.4  547.26  5598.1  550.67  5646.1  553.22  5687.2  554.05
#Mann= 5 ,-1 , 0
  4244.2     .12       0  4421.2     .05       0  5468.2    .033       0
  5478.9     .05       0  5646.1     .12       0
Bank Sta=5468.2,5478.9
XS Rating Curve= 0 ,0
Exp/Cntr=0.3,0.1

Type RM Length L Ch R = 1 ,1611    ,1075,1075,1075
BEGIN DESCRIPTION:
Sharps Branch 3.0
END DESCRIPTION:
XS GIS Cut Line= 3
      2385982.97      7055489.02      2384173.19      7055257.69
      2382978.99      7056660.01
#Sta/Elev= 30
  3175.5  577.33  3229.9   574.6    3240  571.75  3250.1  571.22  3260.2  573.03
  3270.2  570.93  3290.8   570.1  3350.9  560.83  3391.2   552.5  3481.9  540.12
    3525   537.2  3552.5  532.47  3653.3  526.74  3673.5     535  6395.3     535
  6396.7  526.72  6398.2  526.22  6407.5  526.72  6480.1  530.84    6558  538.26
  6579.2  543.68  6586.6   544.6  6664.5  550.64  6678.8  553.51  6742.5  560.27
  6756.8  564.98  6799.6  572.13  6834.8  574.57  6838.6  576.19  6841.9  576.19
#Mann= 4 ,-1 , 0
  3175.5     .12       0  3350.9     .05       0  6396.7    .033       0
  6407.5     .05       0
Bank Sta=6396.7,6407.5
XS Rating Curve= 0 ,0
Exp/Cntr=0.3,0.1

Type RM Length L Ch R = 1 ,536     ,0,0,0
BEGIN DESCRIPTION:
Sharps Branch 1.0
END DESCRIPTION:
XS GIS Cut Line= 3
      2386429.04        7054210.        2383679.        7054360.
      2381936.48       7056996.1
#Sta/Elev= 30
  2250.5  586.66    2344  577.26  2411.3  558.03  2440.8  545.12  2500.9  535.01
  2605.6  526.73  2607.1  526.23  2616.5  526.73  2631.1     535  7428.8     535
  7437.9  528.18  7443.9  531.54  7464.9  527.49  7681.6   535.4  7833.2  560.36
  7898.3  567.59  7913.4  575.12  7934.4  574.15  7949.5  580.38  7970.5  578.85
  7985.6  585.91  8006.7  584.82    8027  592.82  8040.5  595.26  8057.8  604.14
  8078.9  604.08    8094  612.63    8115  605.96  8151.1  610.16  8164.6  619.58
#Mann= 7 ,-1 , 0
  2250.5     .12       0  2411.3     .05       0  2605.6    .033       0
  2616.5     .05       0  7833.2     .12       0    8027     .05       0
  8040.5     .12       0
Bank Sta=2605.6,2616.5
XS Rating Curve= 0 ,0
Exp/Cntr=0.3,0.1

Chan Stop Cuts=-1
Use User Specified Reach Order=0
Composite Channel Slope=5