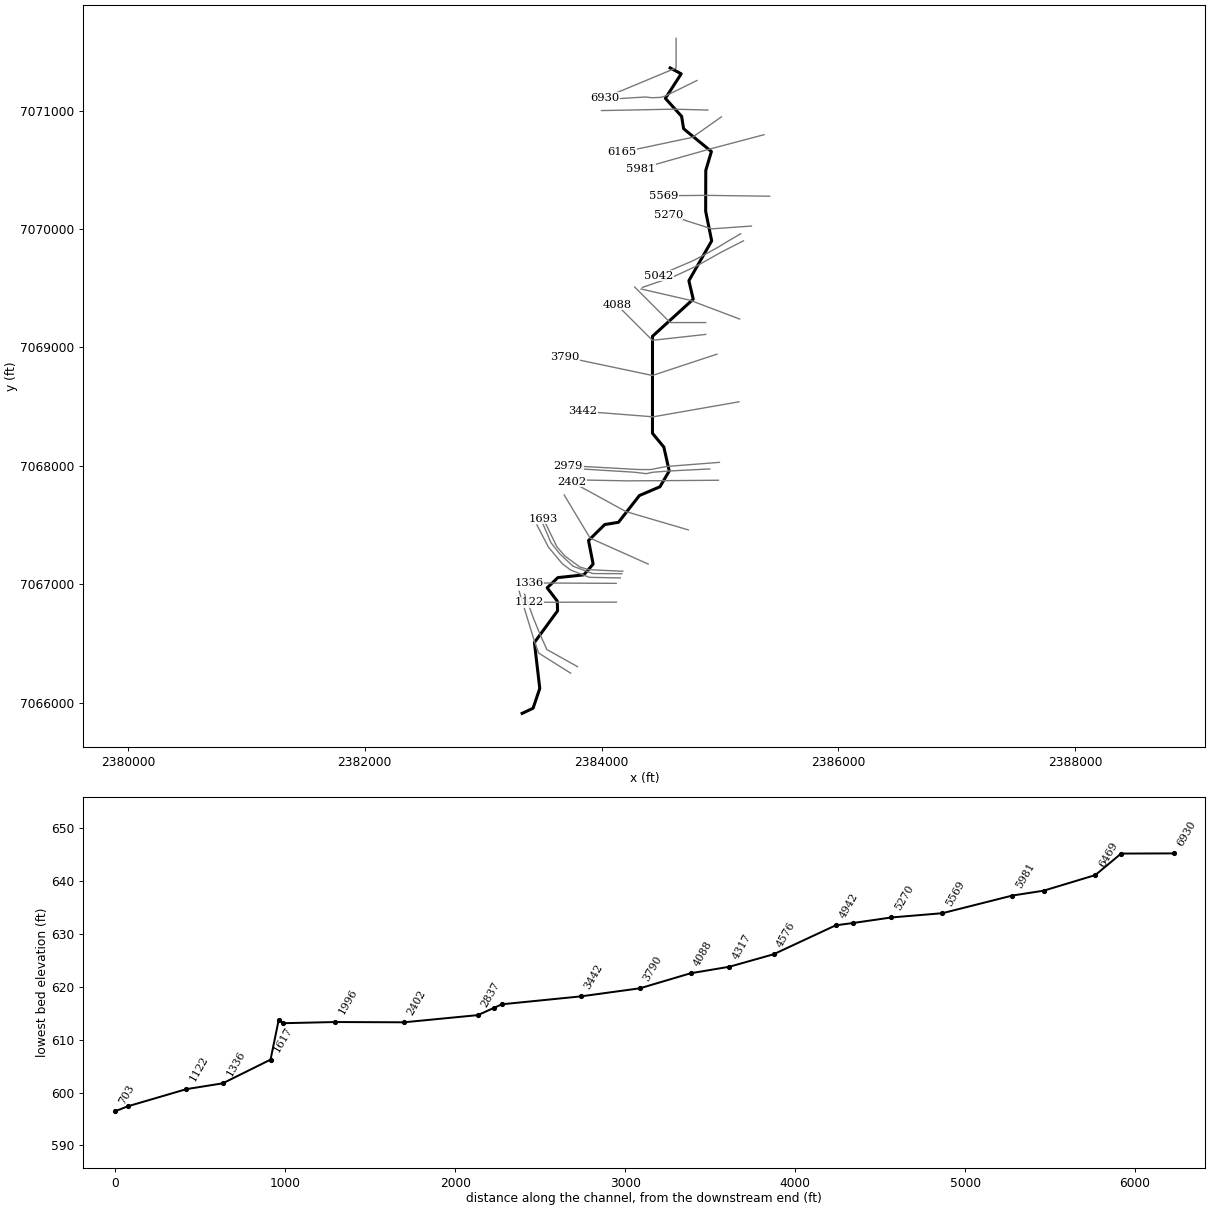
--- Sharps Branch Tr 3.prj (project) ---

Proj Title=Sharps Branch Tr 3 Base Level Engineering
Current Plan=p01
Default Exp/Contr=0.3,0.1
English Units
Geom File=g01
Flow File=f01
Plan File=p01
Y Axis Title=Elevation
X Axis Title(PF)=Main Channel Distance
X Axis Title(XS)=Station
BEGIN DESCRIPTION:
Sharps Branch Tr 3
END DESCRIPTION:
DSS Export Rating Curves= 0
DSS Export Rating Curve Sorted= 0
DSS Export Volume Flow Curves= 0
DXF OffsetX= 0
DXF OffsetY= 0
DXF ScaleX= 1
DXF ScaleY= 10

--- Sharps Branch Tr 3.p01 (plan) ---

Plan Title=Multiple Run
Short Identifier=Multiple
Geom File=g01
Flow File=f01
Subcritical Flow
K Sum by GR= 0
Std Step Tol= 0.01
Critical Tol= 0.01
Num of Std Step Trials= 20
Max Error Tol= 0.3
Flow Tol Ratio= 0.001
Split Flow NTrial= 30
Split Flow Tol= 0.02
Split Flow Ratio= 0.02
Log Output Level= 0
Friction Slope Method= 1
Unsteady Friction Slope Method= 2
Unsteady Bridges Friction Slope Method= 1
Parabolic Critical Depth
Global Vel Dist=  1 , 1 , 1
Global Log Level= 0
CheckData=True
Encroach Param= -1, 0, 0, 0
BEGIN DESCRIPTION:
Multiple Run
END DESCRIPTION:

--- Sharps Branch Tr 3.f01 (steady flow) ---

Flow Title=Multiple
Program Version=4.10
Number of Profiles= 7
Profile Names=10-year,25-year,50-year,1pct_min,100-year,1pct_plu,500-year
River Rch & RM=Sharps Branch Tr,Reach-1         ,6930
     402     537     646     387     772    1540    1102
River Rch & RM=Sharps Branch Tr,Reach-1         ,3442
     493     666     806     486     969    1933    1400
Boundary for River Rch & Prof#=Sharps Branch Tr,Reach-1         , 1
Up Type= 0
Dn Type= 3
Dn Slope=0.01
Boundary for River Rch & Prof#=Sharps Branch Tr,Reach-1         , 2
Up Type= 0
Dn Type= 3
Dn Slope=0.01
Boundary for River Rch & Prof#=Sharps Branch Tr,Reach-1         , 3
Up Type= 0
Dn Type= 3
Dn Slope=0.01
Boundary for River Rch & Prof#=Sharps Branch Tr,Reach-1         , 4
Up Type= 0
Dn Type= 3
Dn Slope=0.01
Boundary for River Rch & Prof#=Sharps Branch Tr,Reach-1         , 5
Up Type= 0
Dn Type= 3
Dn Slope=0.01
Boundary for River Rch & Prof#=Sharps Branch Tr,Reach-1         , 6
Up Type= 0
Dn Type= 3
Dn Slope=0.01
Boundary for River Rch & Prof#=Sharps Branch Tr,Reach-1         , 7
Up Type= 0
Dn Type= 3
Dn Slope=0.01
DSS Import GetInterval= 0
DSS Import GetPeak= 0
DSS Import FillOption= 0

--- Sharps Branch Tr 3.g01 (geometry) ---

Geom Title=Existing Conditions

River Reach=Sharps Branch Tr,Reach-1
Reach XY= 30
      2384579.00      7071360.00      2384671.96      7071310.23
      2384538.12      7071103.29      2384675.50      7070951.52
      2384692.40      7070846.70      2384927.04      7070654.12
      2384879.52      7070494.78      2384878.55      7070149.81
      2384929.46      7069899.81      2384736.81      7069563.41
      2384773.60      7069407.57      2384429.66      7069094.17
      2384429.39      7068275.16      2384525.44      7068158.53
      2384570.96      7067956.68      2384492.57      7067823.47
      2384319.00      7067749.37      2384142.30      7067523.40
      2384026.57      7067504.48      2383889.43      7067369.79
      2383928.41      7067170.61      2383849.21      7067079.59
      2383630.44      7067056.46      2383539.95      7066970.03
      2383625.54      7066858.44      2383628.23      7066776.00
      2383432.55      7066508.53      2383477.80      7066120.51
      2383421.36      7065953.55      2383329.00      7065910.00

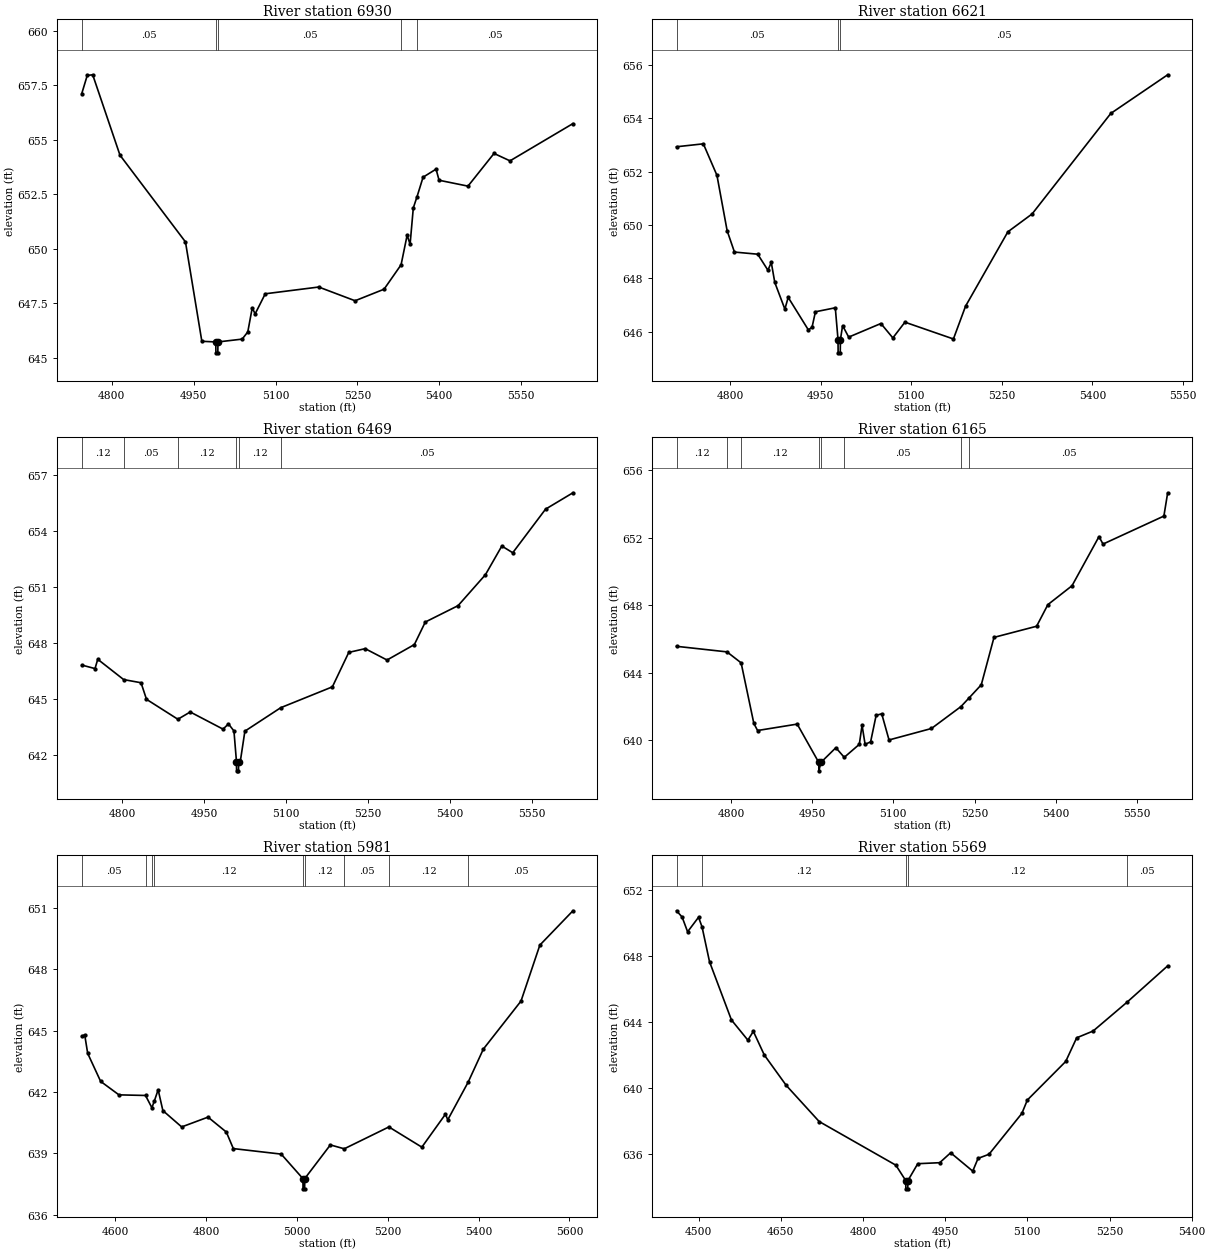
Type RM Length L Ch R = 1,6930,309,309,309
BEGIN DESCRIPTION:
Sharps Branch Tr 3 20.0
END DESCRIPTION:
XS GIS Cut Line= 3
      2384629.00      7071610.03      2384629.00      7071360.00
      2384029.03      7071110.01
#Sta/Elev= 30
  4744.9  657.13  4754.9  657.96  4764.9  657.99  4814.9  654.30  4934.9  650.32
  4964.9  645.76  4990.4  645.73  4990.7  645.23  4994.2  645.23  4994.4  645.73
  5038.8  645.86  5049.1  646.19  5057.2  647.29  5062.6  647.02  5081.1  647.94
  5179.1  648.25  5245.7  647.62  5298.8  648.15  5330.0  649.27  5341.1  650.63
  5346.5  650.21  5352.4  651.88  5359.3  652.40  5370.3  653.29  5394.1  653.66
  5399.6  653.15  5452.6  652.88  5500.3  654.38  5529.6  654.04  5644.9  655.75
#Mann=5,-1,0
  4744.9    0.05       0  4990.4   0.033       0  4994.4    0.05       0
  5330.0   0.075       0  5359.3    0.05       0
Bank Sta=4990.4,4994.4
Exp/Cntr=0.3,0.1

Type RM Length L Ch R = 1,6621,152,152,152
BEGIN DESCRIPTION:
Sharps Branch Tr 3 19.0
END DESCRIPTION:
XS GIS Cut Line= 6
      2384805.09      7071253.89      2384543.62      7071125.86
      2384503.47      7071111.75      2384425.34      7071108.50
      2384368.72      7071114.88      2384024.96      7071093.31
#Sta/Elev= 30
  4711.4  652.93  4755.8  653.04  4778.3  651.86  4795.2  649.78  4807.3  648.98
  4845.8  648.90  4862.7  648.30  4868.3  648.59  4874.1  647.84  4890.8  646.84
  4896.3  647.28  4929.7  646.06  4935.8  646.16  4941.4  646.74  4974.3  646.89
  4978.8  645.70  4979.0  645.20  4982.5  645.20  4982.8  645.70  4986.4  646.22
  4996.5  645.79  5049.8  646.30  5069.6  645.76  5089.6  646.35  5169.9  645.72
  5190.0  646.95  5260.1  649.74  5300.2  650.41  5430.5  654.18  5524.7  655.63
#Mann=3,-1,0
  4711.4    0.05       0  4978.8   0.033       0  4982.8    0.05       0
Bank Sta=4978.8,4982.8
Exp/Cntr=0.3,0.1

Type RM Length L Ch R = 1,6469,304,304,304
BEGIN DESCRIPTION:
Sharps Branch Tr 3 18.0
END DESCRIPTION:
XS GIS Cut Line= 3
      2384897.33      7071004.33      2384610.89      7071011.93
      2383998.94      7070999.99
#Sta/Elev= 30
  4725.8  646.81  4750.0  646.62  4755.0  647.12  4802.4  646.03  4834.2  645.86
  4844.2  644.97  4901.6  643.90  4924.2  644.29  4984.2  643.37  4994.2  643.65
  5004.2  643.27  5008.8  641.63  5009.0  641.13  5012.5  641.13  5012.8  641.63
  5015.8  641.63  5024.2  643.26  5089.8  644.52  5184.3  645.64  5214.3  647.49
  5244.3  647.69  5284.3  647.08  5334.3  647.91  5354.3  649.12  5414.3  650.00
  5464.3  651.66  5494.3  653.20  5514.3  652.84  5574.3  655.18  5624.4  656.06
#Mann=6,-1,0
  4725.8    0.12       0  4802.4    0.05       0  4901.6    0.12       0
  5008.8    0.07       0  5012.8    0.12       0  5089.8    0.05       0
Bank Sta=5008.8,5012.8
Exp/Cntr=0.3,0.1

Type RM Length L Ch R = 1,6165,184,184,184
BEGIN DESCRIPTION:
Sharps Branch Tr 3 17.0
END DESCRIPTION:
XS GIS Cut Line= 3
      2385011.31      7070946.84      2384765.76      7070773.62
      2384172.15      7070648.28
#Sta/Elev= 30
  4699.5  645.56  4792.7  645.23  4818.8  644.58  4842.3  640.99  4849.2  640.57
  4922.4  640.95  4962.2  638.68  4962.4  638.18  4966.2  638.68  4993.8  639.55
  5009.3  638.98  5037.1  639.75  5042.2  640.88  5047.8  639.75  5058.0  639.90
  5068.2  641.47  5078.5  641.56  5092.0  640.01  5170.4  640.69  5224.9  641.99
  5240.4  642.52  5262.4  643.28  5285.9  646.09  5364.6  646.75  5385.4  648.03
  5430.0  649.15  5479.8  652.06  5487.3  651.62  5599.7  653.28  5606.7  654.66
#Mann=8,-1,0
  4699.5    0.12       0  4792.7    0.05       0  4818.8    0.12       0
  4962.2    0.07       0  4966.2    0.12       0  5009.3    0.05       0
  5224.9    0.12       0  5240.4    0.05       0
Bank Sta=4962.2,4966.2
Exp/Cntr=0.3,0.1

Type RM Length L Ch R = 1,5981,412,412,412
BEGIN DESCRIPTION:
Sharps Branch Tr 3 16.0
END DESCRIPTION:
XS GIS Cut Line= 3
      2385371.56      7070796.28      2384911.53      7070674.76
      2384328.99      7070510.00
#Sta/Elev= 30
  4526.6  644.72  4533.0  644.80  4539.6  643.89  4568.1  642.52  4608.4  641.86
  4666.9  641.83  4680.9  641.23  4686.5  641.57  4694.7  642.11  4705.1  641.09
  4746.5  640.29  4804.5  640.77  4844.8  640.04  4860.2  639.23  4965.6  638.96
  5013.4  637.76  5013.7  637.26  5017.2  637.26  5017.4  637.76  5073.8  639.41
  5104.4  639.22  5202.7  640.29  5275.2  639.30  5327.1  640.91  5332.3  640.64
  5377.1  642.48  5410.6  644.10  5493.5  646.45  5535.0  649.19  5607.8  650.87
#Mann=9,-1,0
  4526.6    0.05       0  4666.9    0.12       0  4680.9    0.05       0
  4686.5    0.12       0  5013.4    0.07       0  5017.4    0.12       0
  5104.4    0.05       0  5202.7    0.12       0  5377.1    0.05       0
Bank Sta=5013.4,5017.4
Exp/Cntr=0.3,0.1

Type RM Length L Ch R = 1,5569,299,299,299
BEGIN DESCRIPTION:
Sharps Branch Tr 3 15.0
END DESCRIPTION:
XS GIS Cut Line= 3
      2385419.23      7070276.80      2384883.32      7070284.14
      2384522.89      7070281.15
#Sta/Elev= 30
  4459.7  650.73  4469.9  650.35  4479.9  649.46  4499.9  650.34  4506.3  649.75
  4519.9  647.65  4559.9  644.13  4589.9  642.91  4599.9  643.44  4619.9  642.01
  4660.0  640.17  4720.0  637.99  4860.0  635.35  4878.0  634.42  4878.2  633.92
  4881.7  633.92  4882.0  634.42  4900.0  635.44  4940.0  635.50  4960.0  636.10
  5000.3  634.99  5010.0  635.76  5030.0  636.01  5090.0  638.48  5100.0  639.29
  5170.0  641.62  5190.0  643.05  5220.0  643.46  5281.8  645.20  5356.1  647.40
#Mann=5,-1,0
  4459.7    0.05       0  4506.3    0.12       0  4878.0    0.07       0
  4882.0    0.12       0  5281.8    0.05       0
Bank Sta=4878,4882
Exp/Cntr=0.3,0.1

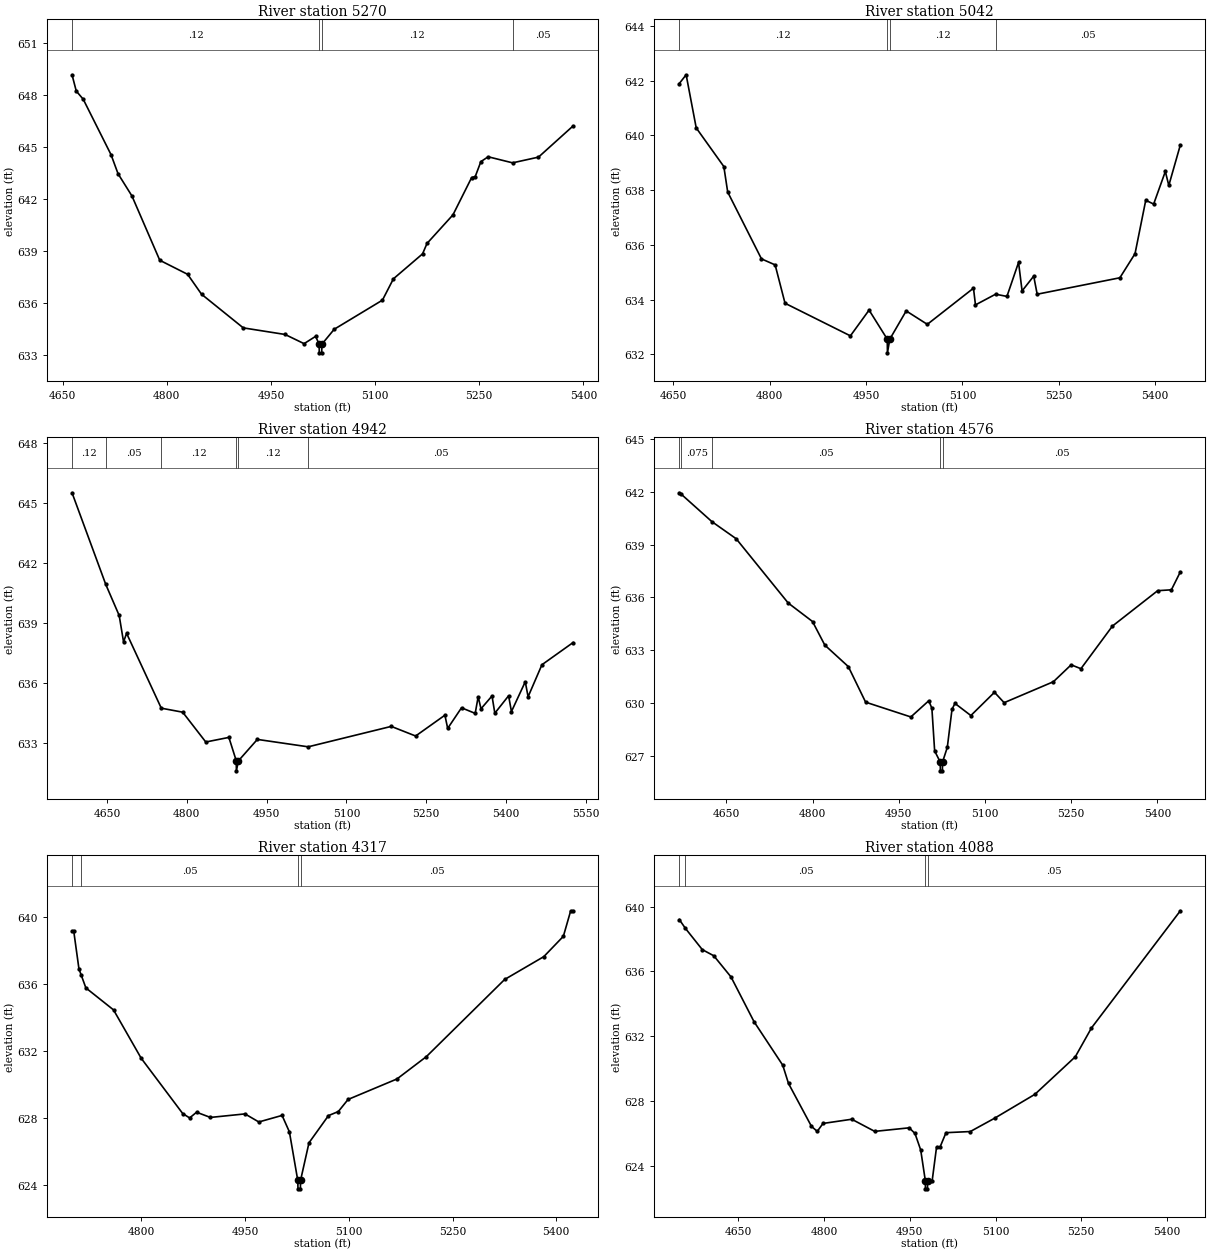
Type RM Length L Ch R = 1,5270,228,228,228
BEGIN DESCRIPTION:
Sharps Branch Tr 3 14.0
END DESCRIPTION:
XS GIS Cut Line= 3
      2385265.10      7070025.06      2384929.35      7070001.21
      2384562.48      7070118.97
#Sta/Elev= 30
  4663.4  649.16  4669.5  648.22  4679.5  647.75  4719.6  644.55  4729.7  643.45
  4749.7  642.17  4789.8  638.46  4829.9  637.65  4850.0  636.50  4910.1  634.56
  4970.3  634.18  4997.7  633.65  5014.3  634.07  5019.4  633.62  5019.6  633.12
  5023.1  633.12  5023.4  633.62  5041.1  634.48  5110.6  636.16  5126.4  637.39
  5168.4  638.83  5174.8  639.43  5212.2  641.08  5239.1  643.23  5244.3  643.29
  5252.4  644.15  5262.9  644.43  5298.1  644.08  5335.4  644.41  5385.3  646.21
#Mann=4,-1,0
  4663.4    0.12       0  5019.4    0.07       0  5023.4    0.12       0
  5298.1    0.05       0
Bank Sta=5019.4,5023.4
Exp/Cntr=0.3,0.1

Type RM Length L Ch R = 1,5042,100,100,100
BEGIN DESCRIPTION:
Mapping XS e2304d77
END DESCRIPTION:
XS GIS Cut Line= 6
      2385174.04      7069959.99      2385061.15      7069893.77
      2384990.62      7069850.37      2384879.36      7069788.50
      2384771.44      7069732.10      2384479.45      7069607.06
#Sta/Elev= 30
  4659.0  641.89  4669.7  642.21  4685.4  640.27  4728.4  638.86  4734.4  637.93
  4787.0  635.49  4808.3  635.27  4823.7  633.87  4925.5  632.68  4954.6  633.62
  4982.9  632.56  4983.2  632.06  4986.9  632.56  5012.4  633.59  5045.3  633.10
  5117.2  634.42  5120.3  633.81  5151.6  634.20  5169.3  634.12  5187.4  635.36
  5192.9  634.32  5211.0  634.86  5216.4  634.20  5345.2  634.80  5368.8  635.68
  5385.5  637.63  5397.8  637.49  5416.0  638.68  5421.4  638.17  5439.4  639.65
#Mann=4,-1,0
  4659.0    0.12       0  4982.9    0.07       0  4986.9    0.12       0
  5151.6    0.05       0
Bank Sta=4982.9,4986.9
Exp/Cntr=0.3,0.1

Type RM Length L Ch R = 1,4942,366,366,366
BEGIN DESCRIPTION:
Sharps Branch Tr 3 13.0
END DESCRIPTION:
XS GIS Cut Line= 6
      2385197.88      7069900.29      2385006.90      7069802.63
      2384831.71      7069703.87      2384779.03      7069676.76
      2384607.50      7069597.29      2384344.91      7069507.23
#Sta/Elev= 30
  4584.4  645.52  4647.8  640.94  4673.0  639.39  4681.2  638.07  4686.9  638.50
  4752.1  634.76  4792.3  634.56  4835.7  633.07  4879.1  633.30  4893.0  632.13
  4893.2  631.63  4897.0  632.13  4932.6  633.20  5028.1  632.83  5184.2  633.85
  5230.0  633.37  5285.0  634.41  5290.2  633.75  5316.2  634.78  5341.9  634.50
  5347.5  635.33  5352.8  634.73  5373.5  635.37  5378.8  634.51  5404.7  635.38
  5410.0  634.59  5436.0  636.08  5441.3  635.33  5467.3  636.93  5525.9  638.04
#Mann=6,-1,0
  4584.4    0.12       0  4647.8    0.05       0  4752.1    0.12       0
  4893.0    0.07       0  4897.0    0.12       0  5028.1    0.05       0
Bank Sta=4893,4897
Exp/Cntr=0.3,0.1

Type RM Length L Ch R = 1,4576,259,259,259
BEGIN DESCRIPTION:
Mapping XS 30d49303
END DESCRIPTION:
XS GIS Cut Line= 3
      2385165.74      7069239.58      2384746.46      7069398.44
      2384333.83      7069493.46
#Sta/Elev= 30
  4568.2  641.94  4571.9  641.85  4625.0  640.30  4667.2  639.33  4757.7  635.68
  4800.0  634.63  4821.4  633.29  4862.3  632.07  4892.4  630.05  4971.1  629.21
  5002.3  630.13  5007.7  629.70  5012.5  627.28  5022.2  626.65  5022.5  626.15
  5026.0  626.15  5026.2  626.65  5034.5  627.48  5042.7  629.64  5047.8  629.98
  5075.5  629.29  5116.6  630.61  5133.4  630.02  5219.1  631.21  5250.0  632.17
  5267.0  631.95  5321.8  634.37  5400.5  636.38  5424.4  636.43  5440.0  637.45
#Mann=5,-1,0
  4568.2    0.05       0  4571.9   0.075       0  4625.0    0.05       0
  5022.2    0.04       0  5026.2    0.05       0
Bank Sta=5022.2,5026.2
Exp/Cntr=0.3,0.1

Type RM Length L Ch R = 1,4317,229,229,229
BEGIN DESCRIPTION:
Sharps Branch Tr 3 10.0
END DESCRIPTION:
XS GIS Cut Line= 3
      2384879.03      7069210.00      2384579.00      7069210.00
      2384279.00      7069510.00
#Sta/Elev= 30
  4700.0  639.13  4702.5  639.13  4710.0  636.89  4713.2  636.53  4720.0  635.76
  4760.0  634.45  4800.0  631.57  4860.0  628.28  4870.0  628.02  4880.0  628.36
  4900.0  628.05  4950.0  628.26  4970.0  627.78  5003.6  628.17  5014.2  627.19
  5026.3  624.30  5026.6  623.80  5030.1  623.80  5030.3  624.30  5042.5  626.54
  5070.7  628.16  5084.9  628.40  5099.0  629.12  5169.7  630.34  5212.2  631.67
  5325.3  636.26  5381.9  637.62  5410.2  638.83  5420.8  640.35  5424.3  640.35
#Mann=4,-1,0
  4700.0   0.075       0  4713.2    0.05       0  5026.3    0.04       0
  5030.3    0.05       0
Bank Sta=5026.3,5030.3
Exp/Cntr=0.3,0.1

Type RM Length L Ch R = 1,4088,298,298,298
BEGIN DESCRIPTION:
Sharps Branch Tr 3 9.0
END DESCRIPTION:
XS GIS Cut Line= 3
      2384879.03      7069110.00      2384429.00      7069060.00
      2384128.98      7069360.02
#Sta/Elev= 30
  4546.4  639.20  4557.2  638.65  4586.7  637.34  4606.8  636.96  4637.0  635.65
  4677.2  632.89  4727.5  630.20  4737.6  629.07  4777.8  626.42  4787.9  626.11
  4798.0  626.60  4848.3  626.86  4888.5  626.11  4948.9  626.33  4959.0  625.98
  4969.0  624.96  4977.1  623.06  4977.3  622.56  4980.8  622.56  4981.1  623.06
  4989.1  623.07  4996.7  625.13  5002.7  625.13  5013.3  626.03  5055.8  626.10
  5098.2  626.92  5168.9  628.40  5239.6  630.72  5267.9  632.50  5423.5  639.74
#Mann=4,-1,0
  4546.4   0.075       0  4557.2    0.05       0  4977.1    0.04       0
  4981.1    0.05       0
Bank Sta=4977.1,4981.1
Exp/Cntr=0.3,0.1

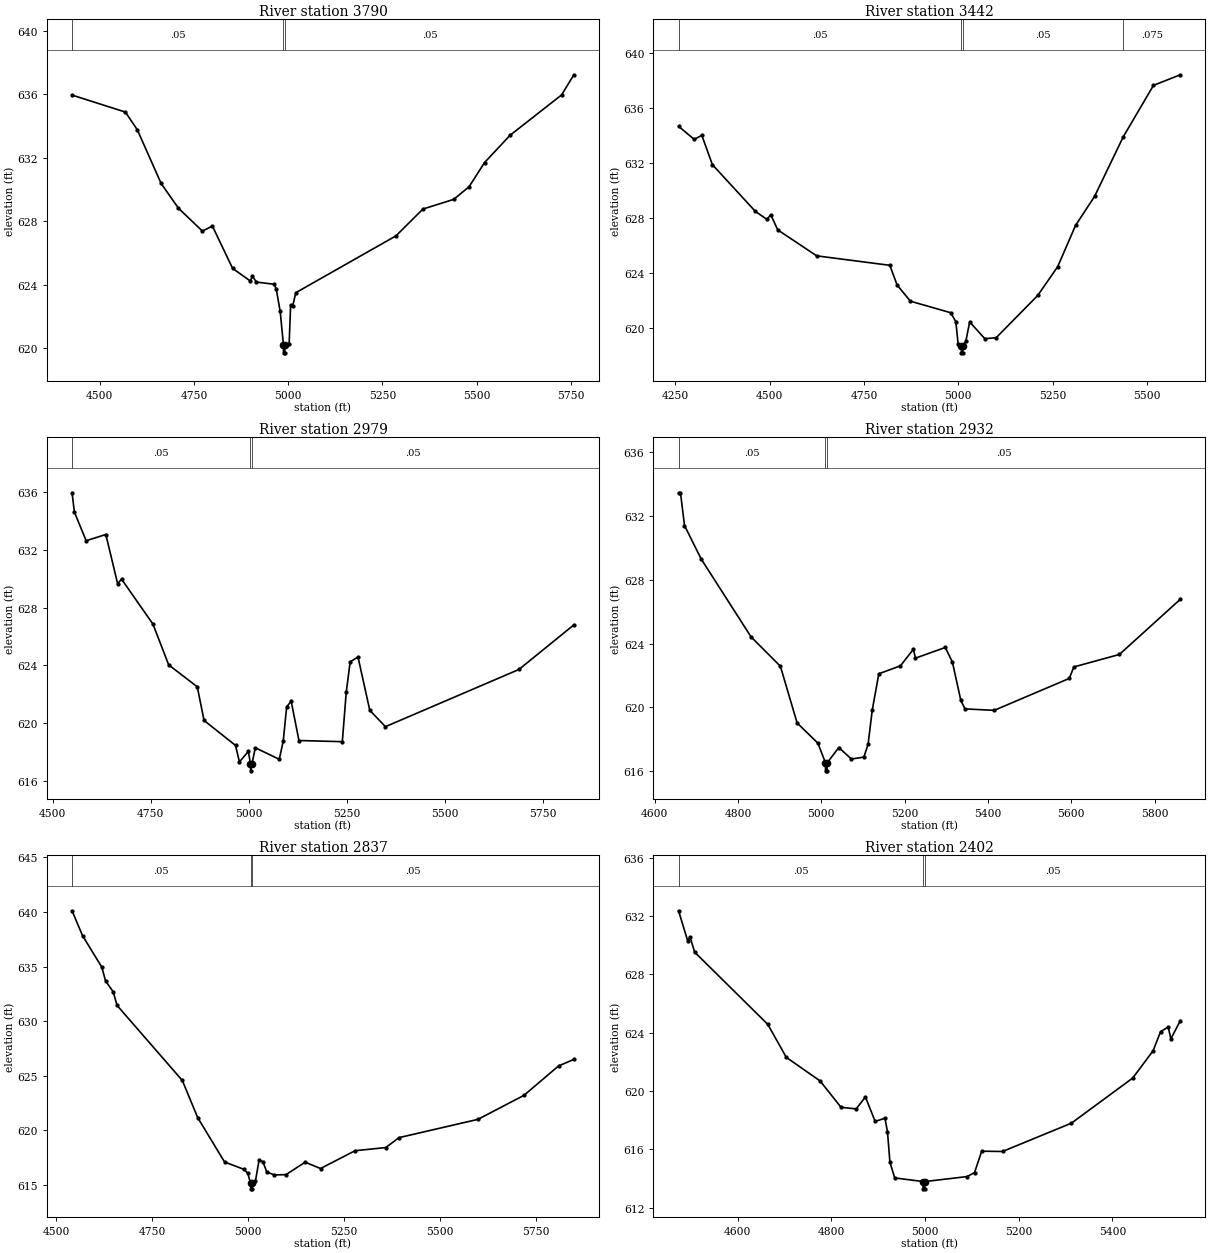
Type RM Length L Ch R = 1,3790,348,348,348
BEGIN DESCRIPTION:
Sharps Branch Tr 3 8.0
END DESCRIPTION:
XS GIS Cut Line= 3
      2384973.51      7068943.04      2384428.99      7068763.35
      2383687.06      7068919.59
#Sta/Elev= 30
  4426.6  635.96  4568.2  634.89  4599.8  633.77  4663.0  630.39  4709.0  628.83
  4772.5  627.39  4799.0  627.71  4852.6  625.04  4899.5  624.25  4905.2  624.55
  4915.7  624.18  4963.0  624.04  4968.4  623.74  4978.9  622.33  4987.5  620.22
  4987.7  619.72  4991.2  619.72  4991.5  620.22  5002.6  620.27  5006.6  622.72
  5011.7  622.64  5020.4  623.51  5286.1  627.09  5357.7  628.78  5439.4  629.39
  5480.3  630.19  5521.2  631.71  5589.0  633.43  5725.6  635.97  5758.2  637.24
#Mann=3,-1,0
  4426.6    0.05       0  4987.5    0.04       0  4991.5    0.05       0
Bank Sta=4987.5,4991.5
Exp/Cntr=0.3,0.1

Type RM Length L Ch R = 1,3442,463,463,463
BEGIN DESCRIPTION:
Sharps Branch Tr 3 7.0
END DESCRIPTION:
XS GIS Cut Line= 3
      2385159.86      7068540.90      2384435.71      7068414.18
      2383842.17      7068460.48
#Sta/Elev= 30
  4258.1  634.68  4299.6  633.73  4319.9  634.02  4347.8  631.89  4461.7  628.49
  4492.5  627.90  4502.6  628.25  4521.1  627.14  4624.4  625.25  4818.4  624.56
  4837.6  623.13  4872.8  621.95  4979.8  621.11  4993.3  620.46  4999.4  618.86
  5008.0  618.69  5008.3  618.19  5011.8  618.19  5012.0  618.69  5020.0  619.05
  5030.1  620.44  5070.2  619.22  5100.3  619.29  5210.6  622.37  5263.4  624.46
  5310.9  627.47  5361.1  629.57  5437.0  633.90  5517.4  637.66  5588.6  638.43
#Mann=4,-1,0
  4258.1    0.05       0  5008.0    0.04       0  5012.0    0.05       0
  5437.0   0.075       0
Bank Sta=5008,5012
Exp/Cntr=0.3,0.1

Type RM Length L Ch R = 1,2979,47,47,47
BEGIN DESCRIPTION:
Mapping XS 9bd9f77b
END DESCRIPTION:
XS GIS Cut Line= 5
      2384994.91      7068029.62      2384548.76      7067994.90
      2384415.08      7067968.86      2384316.12      7067968.86
      2383718.88      7068001.85
#Sta/Elev= 30
  4549.1  635.96  4555.0  634.62  4585.1  632.64  4635.3  633.07  4665.4  629.66
  4675.4  629.98  4755.6  626.86  4795.7  624.04  4868.7  622.52  4886.0  620.19
  4966.3  618.46  4976.3  617.32  4999.0  618.04  5004.5  617.20  5004.8  616.70
  5008.5  617.20  5016.7  618.30  5077.9  617.50  5088.0  618.74  5096.9  621.14
  5108.4  621.52  5128.2  618.80  5238.9  618.72  5248.9  622.14  5258.9  624.24
  5278.9  624.59  5309.0  620.89  5349.0  619.76  5689.6  623.72  5829.9  626.81
#Mann=3,-1,0
  4549.1    0.05       0  5004.5   0.033       0  5008.5    0.05       0
Bank Sta=5004.5,5008.5
Exp/Cntr=0.3,0.1

Type RM Length L Ch R = 1,2932,95,95,95
BEGIN DESCRIPTION:
Mapping XS e9b57553
END DESCRIPTION:
XS GIS Cut Line= 6
      2384913.32      7067974.07      2384571.33      7067956.71
      2384432.44      7067946.29      2384376.88      7067934.14
      2384276.19      7067946.29      2383712.94      7067980.95
#Sta/Elev= 30
  4657.2  633.45  4661.9  633.45  4671.5  631.40  4711.6  629.30  4831.4  624.42
  4901.8  622.58  4941.9  619.03  4991.9  617.76  5010.0  616.53  5010.2  616.03
  5013.7  616.03  5014.0  616.53  5042.1  617.49  5072.2  616.77  5102.2  616.89
  5112.3  617.69  5122.3  619.83  5138.1  622.11  5190.1  622.61  5221.1  623.65
  5226.1  623.09  5297.7  623.76  5314.9  622.83  5334.9  620.45  5345.0  619.91
  5415.1  619.82  5595.4  621.82  5606.4  622.54  5715.7  623.32  5862.0  626.78
#Mann=3,-1,0
  4657.2    0.05       0  5010.0   0.033       0  5014.0    0.05       0
Bank Sta=5010,5014
Exp/Cntr=0.3,0.1

Type RM Length L Ch R = 1,2837,435,435,435
BEGIN DESCRIPTION:
Mapping XS 2b6a10d8
END DESCRIPTION:
XS GIS Cut Line= 4
      2384986.27      7067878.58      2384533.13      7067875.11
      2384218.90      7067873.37      2383678.98      7067883.79
#Sta/Elev= 30
  4542.0  640.11  4569.3  637.83  4619.3  634.96  4629.3  633.69  4649.3  632.68
  4659.3  631.44  4829.3  624.57  4869.3  621.17  4939.3  617.11  4989.3  616.44
  4999.7  616.08  5007.3  615.15  5007.5  614.65  5011.0  614.65  5011.3  615.15
  5019.6  615.34  5029.3  617.28  5039.3  617.13  5049.3  616.19  5069.3  615.92
  5099.3  615.95  5149.3  617.09  5189.3  616.51  5279.3  618.14  5359.3  618.43
  5394.0  619.34  5599.3  621.01  5719.4  623.21  5809.4  625.90  5849.4  626.50
#Mann=3,-1,0
  4542.0    0.05       0  5007.3    0.04       0  5011.3    0.05       0
Bank Sta=5007.3,5011.3
Exp/Cntr=0.3,0.1

Type RM Length L Ch R = 1,2402,406,406,406
BEGIN DESCRIPTION:
Mapping XS 122e2599
END DESCRIPTION:
XS GIS Cut Line= 3
      2384731.94      7067459.30      2384206.75      7067613.39
      2383746.83      7067865.04
#Sta/Elev= 30
  4473.6  632.35  4493.1  630.30  4498.3  630.56  4507.9  629.52  4664.3  624.56
  4703.8  622.30  4775.8  620.69  4820.6  618.88  4853.0  618.77  4872.7  619.59
  4893.5  617.91  4914.4  618.13  4919.8  617.21  4925.0  615.13  4935.2  614.04
  4995.7  613.79  4996.0  613.29  4999.5  613.29  4999.7  613.79  5089.6  614.13
  5105.7  614.40  5121.0  615.87  5165.5  615.85  5312.5  617.79  5443.4  620.88
  5487.0  622.75  5503.1  624.07  5519.3  624.38  5525.0  623.57  5545.2  624.82
#Mann=3,-1,0
  4473.6    0.05       0  4995.7   0.033       0  4999.7    0.05       0
Bank Sta=4995.7,4999.7
Exp/Cntr=0.3,0.1

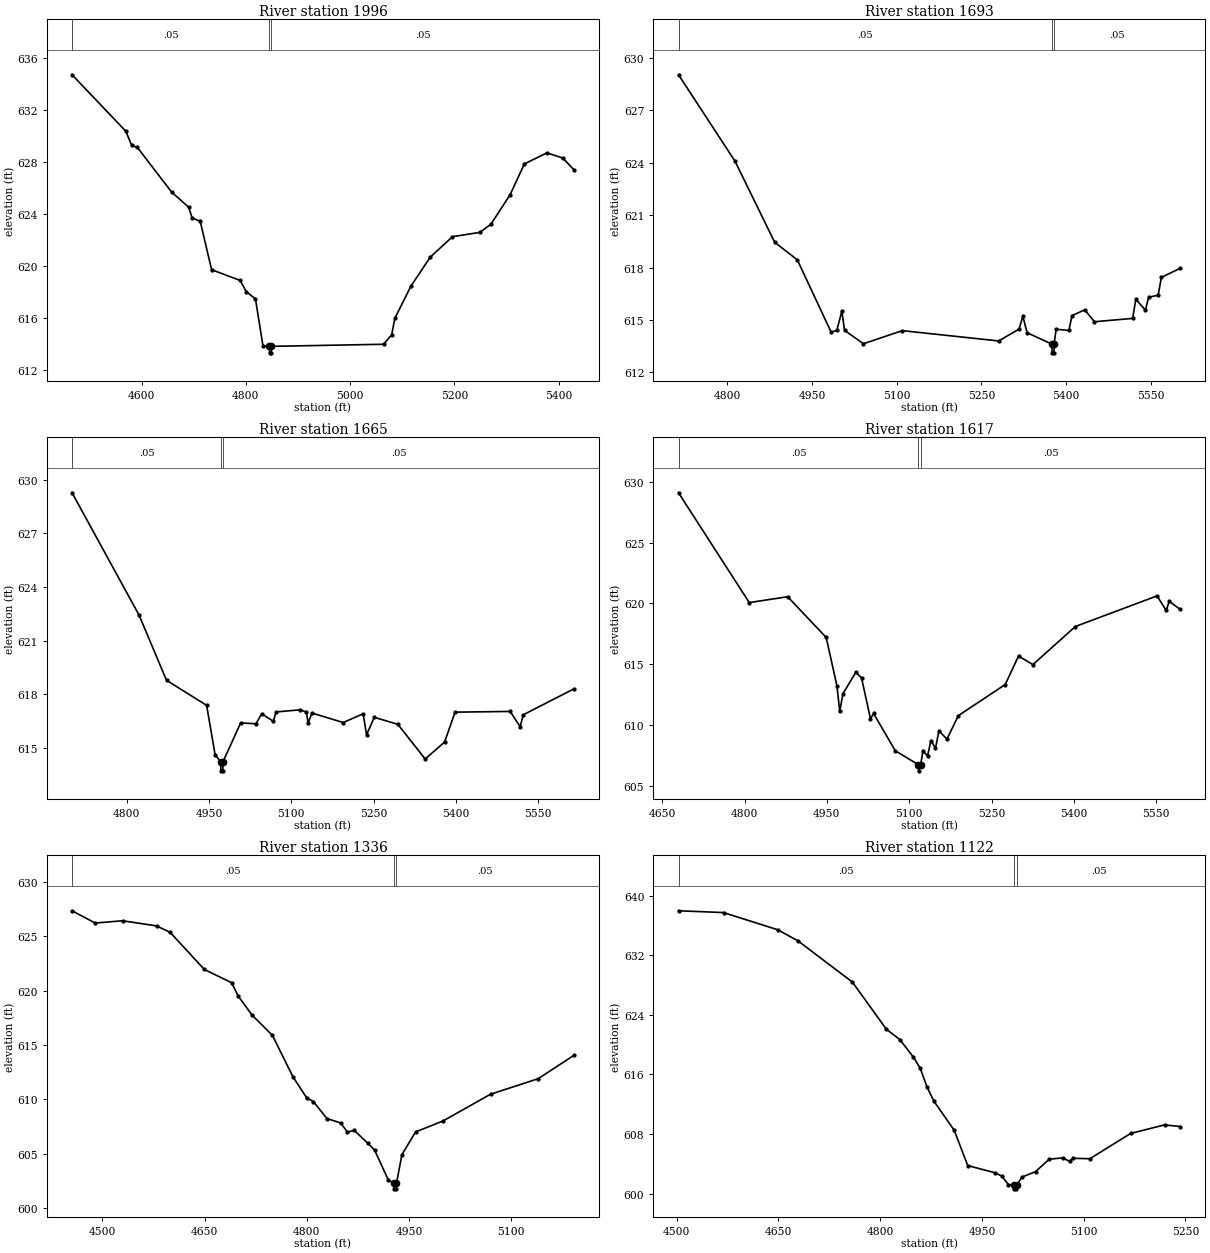
Type RM Length L Ch R = 1,1996,303,303,303
BEGIN DESCRIPTION:
Mapping XS 43ca692c
END DESCRIPTION:
XS GIS Cut Line= 3
      2384393.35      7067170.70      2383902.93      7067389.87
      2383683.88      7067754.22
#Sta/Elev= 30
  4466.8  634.74  4570.0  630.39  4581.1  629.31  4592.0  629.15  4657.8  625.71
  4690.6  624.54  4697.0  623.72  4712.5  623.47  4734.4  619.74  4789.2  618.91
  4800.8  618.05  4818.5  617.49  4833.0  613.85  4845.2  613.84  4845.5  613.34
  4849.0  613.34  4849.2  613.84  5064.2  614.00  5079.7  614.73  5085.8  616.00
  5116.6  618.47  5153.6  620.70  5196.3  622.28  5248.8  622.61  5270.1  623.24
  5307.0  625.52  5334.2  627.88  5377.5  628.73  5408.1  628.33  5429.1  627.43
#Mann=3,-1,0
  4466.8    0.05       0  4845.2   0.033       0  4849.2    0.05       0
Bank Sta=4845.2,4849.2
Exp/Cntr=0.3,0.1

Type RM Length L Ch R = 1,1693,28,28,28
BEGIN DESCRIPTION:
Sharps Branch Tr 3 3.0
END DESCRIPTION:
XS GIS Cut Line= 6
      2384179.02      7067110.00      2383893.13      7067123.33
      2383816.28      7067145.94      2383689.32      7067239.25
      2383622.05      7067317.38      2383508.14      7067552.79
#Sta/Elev= 30
  4713.8  629.03  4813.9  624.08  4884.0  619.45  4924.1  618.44  4984.1  614.30
  4994.1  614.41  5003.0  615.51  5007.7  614.41  5041.1  613.64  5110.0  614.39
  5280.7  613.80  5316.8  614.48  5323.4  615.22  5331.0  614.27  5374.8  613.62
  5375.1  613.12  5378.6  613.12  5378.8  613.62  5382.4  614.47  5405.0  614.40
  5410.5  615.25  5433.1  615.58  5450.2  614.90  5517.9  615.09  5523.5  616.19
  5540.5  615.56  5546.1  616.30  5563.1  616.42  5568.7  617.44  5602.3  617.96
#Mann=3,-1,0
  4713.8    0.05       0  5374.8   0.033       0  5378.8    0.05       0
Bank Sta=5374.8,5378.8
Exp/Cntr=0.3,0.1

Type RM Length L Ch R = 1,1665,48,48,48
BEGIN DESCRIPTION:
Mapping XS 20ffaeb1
END DESCRIPTION:
XS GIS Cut Line= 6
      2384171.09      7067089.51      2383925.87      7067090.60
      2383758.77      7067152.45      2383645.92      7067257.70
      2383572.14      7067352.10      2383487.48      7067549.62
#Sta/Elev= 30
  4700.6  629.27  4822.7  622.43  4872.7  618.79  4945.8  617.39  4961.2  614.63
  4971.5  614.23  4971.8  613.73  4975.3  613.73  4975.5  614.23  5007.8  616.41
  5035.6  616.36  5046.2  616.92  5067.2  616.50  5072.5  617.02  5115.3  617.14
  5127.6  617.02  5130.6  616.39  5137.7  616.96  5194.7  616.43  5230.9  616.92
  5237.2  615.75  5251.3  616.72  5294.2  616.33  5344.0  614.39  5379.4  615.34
  5398.5  617.01  5498.9  617.05  5517.1  616.19  5522.5  616.86  5614.9  618.31
#Mann=3,-1,0
  4700.6    0.05       0  4971.5   0.033       0  4975.5    0.05       0
Bank Sta=4971.5,4975.5
Exp/Cntr=0.3,0.1

Type RM Length L Ch R = 1,1617,281,281,281
BEGIN DESCRIPTION:
Mapping XS ab6e8be3
END DESCRIPTION:
XS GIS Cut Line= 6
      2384157.80      7067053.60      2383896.06      7067058.81
      2383738.50      7067120.00      2383666.89      7067174.69
      2383551.00      7067314.01      2383453.66      7067500.91
#Sta/Elev= 30
  4679.8  629.10  4808.6  620.07  4878.6  620.55  4948.8  617.20  4968.4  613.22
  4973.5  611.13  4979.4  612.58  5002.7  614.33  5013.2  613.88  5029.5  610.50
  5035.1  610.95  5074.7  607.88  5116.9  606.73  5117.1  606.23  5120.9  606.73
  5125.2  607.89  5133.4  607.45  5139.7  608.72  5147.9  608.08  5154.2  609.52
  5168.8  608.84  5189.6  610.77  5275.0  613.33  5299.2  615.67  5325.5  614.97
  5402.7  618.10  5551.7  620.62  5568.2  619.42  5573.8  620.17  5594.0  619.50
#Mann=3,-1,0
  4679.8    0.05       0  5116.9   0.033       0  5120.9    0.05       0
Bank Sta=5116.9,5120.9
Exp/Cntr=0.3,0.1

Type RM Length L Ch R = 1,1336,214,214,214
BEGIN DESCRIPTION:
Sharps Branch Tr 3 2.0
END DESCRIPTION:
XS GIS Cut Line= 3
      2384122.97      7067007.98      2383515.66      7067010.70
      2383386.73      7067014.34
#Sta/Elev= 30
  4455.6  627.35  4489.6  626.22  4529.6  626.43  4579.6  625.96  4599.6  625.36
  4649.6  621.95  4689.6  620.73  4699.6  619.48  4719.6  617.76  4749.6  615.88
  4779.6  612.08  4799.6  610.15  4809.6  609.79  4829.6  608.22  4849.6  607.82
  4859.6  606.98  4869.6  607.13  4889.6  605.95  4899.6  605.31  4919.6  602.57
  4927.6  602.25  4927.8  601.75  4931.3  601.75  4931.6  602.25  4939.6  604.90
  4959.6  606.99  4999.6  607.99  5069.6  610.46  5139.6  611.89  5191.9  614.04
#Mann=3,-1,0
  4455.6    0.05       0  4927.6   0.033       0  4931.6    0.05       0
Bank Sta=4927.6,4931.6
Exp/Cntr=0.3,0.1

Type RM Length L Ch R = 1,1122,346,346,346
BEGIN DESCRIPTION:
Mapping XS 3166d3c5
END DESCRIPTION:
XS GIS Cut Line= 3
      2384125.32      7066849.34      2383543.95      7066848.39
      2383385.72      7066849.34
#Sta/Elev= 30
  4502.9  637.96  4569.2  637.72  4649.2  635.41  4679.2  633.91  4759.2  628.39
  4809.2  622.07  4829.2  620.67  4849.2  618.31  4859.2  616.81  4869.2  614.29
  4879.2  612.43  4909.2  608.51  4929.2  603.77  4969.2  602.81  4979.2  602.37
  4989.2  601.22  4997.2  601.15  4997.5  600.65  5001.0  600.65  5001.2  601.15
  5009.2  602.23  5029.2  602.97  5049.2  604.62  5069.2  604.81  5079.2  604.34
  5084.2  604.75  5109.2  604.69  5169.2  608.08  5219.2  609.23  5242.5  609.01
#Mann=3,-1,0
  4502.9    0.05       0  4997.2   0.033       0  5001.2    0.05       0
Bank Sta=4997.2,5001.2
Exp/Cntr=0.3,0.1

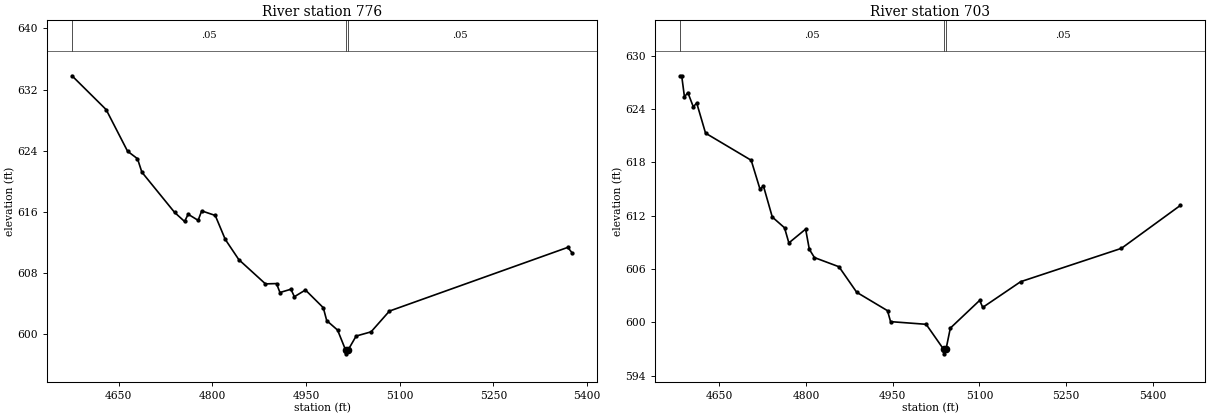
Type RM Length L Ch R = 1,776,73,73,73
BEGIN DESCRIPTION:
Mapping XS f84a9d27
END DESCRIPTION:
XS GIS Cut Line= 5
      2383796.75      7066304.56      2383537.59      7066449.12
      2383484.20      7066567.60      2383430.82      7066697.81
      2383349.30      7066916.48
#Sta/Elev= 30
  4575.2  633.80  4629.9  629.37  4664.2  623.92  4680.1  622.94  4687.1  621.18
  4739.5  615.91  4755.5  614.72  4761.2  615.67  4777.2  614.87  4782.9  616.11
  4804.6  615.51  4820.6  612.38  4842.3  609.73  4885.0  606.55  4902.7  606.59
  4908.2  605.42  4925.8  605.85  4931.3  604.87  4949.0  605.75  4977.6  603.43
  4983.1  601.74  5000.5  600.50  5013.3  597.89  5013.6  597.39  5017.3  597.89
  5030.2  599.72  5054.1  600.27  5083.5  602.99  5369.1  611.33  5376.0  610.61
#Mann=3,-1,0
  4575.2    0.05       0  5013.3   0.033       0  5017.3    0.05       0
Bank Sta=5013.3,5017.3
Exp/Cntr=0.3,0.1

Type RM Length L Ch R = 1,703,0,0,0
BEGIN DESCRIPTION:
Sharps Branch Tr 3 1.0
END DESCRIPTION:
XS GIS Cut Line= 4
      2383738.11      7066249.89      2383468.58      7066419.17
      2383434.47      7066512.45      2383303.64      7066940.81
#Sta/Elev= 30
  4582.4  627.73  4584.8  627.73  4589.6  625.36  4595.5  625.84  4604.9  624.24
  4610.8  624.67  4626.1  621.28  4705.1  618.23  4720.4  614.97  4726.3  615.34
  4741.6  611.85  4762.8  610.64  4770.3  608.94  4799.3  610.49  4805.7  608.22
  4814.6  607.29  4857.0  606.26  4887.7  603.39  4941.0  601.32  4946.3  600.09
  5007.9  599.79  5038.2  596.97  5038.4  596.47  5042.2  596.97  5049.7  599.36
  5100.5  602.48  5105.8  601.69  5171.4  604.58  5345.8  608.33  5447.9  613.16
#Mann=3,-1,0
  4582.4    0.05       0  5038.2   0.033       0  5042.2    0.05       0
Bank Sta=5038.2,5042.2
Exp/Cntr=0.3,0.1

Chan Stop Cuts=-1