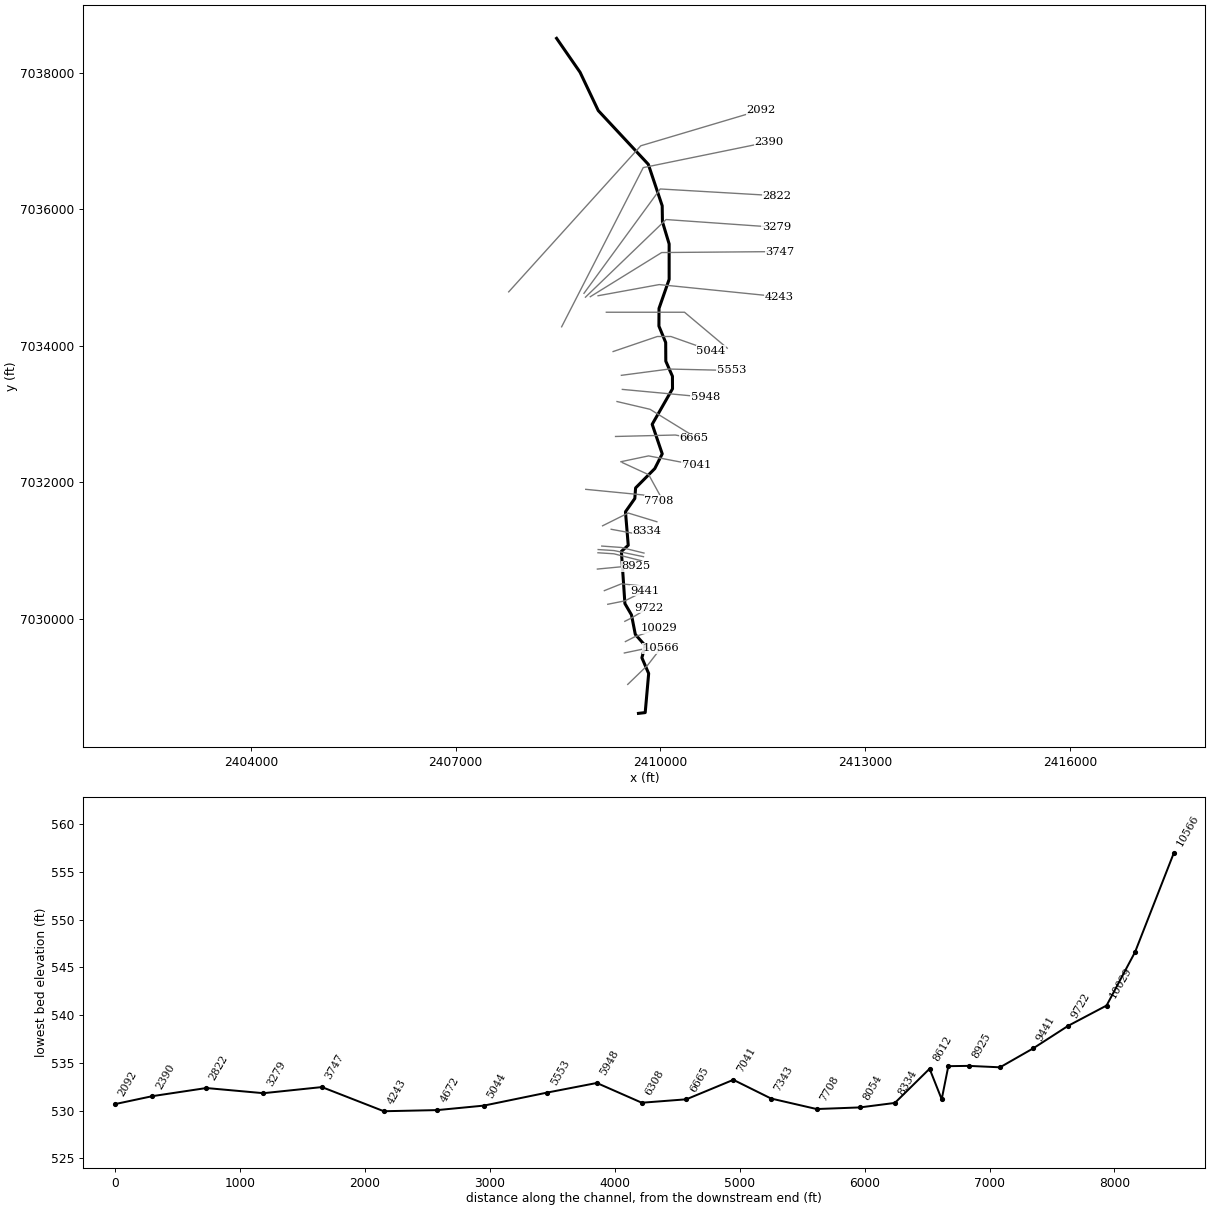
--- Silver Lake Branch.prj (project) ---

Proj Title=Silver Lake Branch Base Level Engineering
Current Plan=p01
Default Exp/Contr=0.3,0.1
English Units
Geom File=g01
Flow File=f01
Plan File=p01
Y Axis Title=Elevation
X Axis Title(PF)=Main Channel Distance
X Axis Title(XS)=Station
BEGIN DESCRIPTION:
Silver Lake Branch
END DESCRIPTION:
DSS Export Rating Curves= 0
DSS Export Rating Curve Sorted= 0
DSS Export Volume Flow Curves= 0
DXF OffsetX= 0
DXF OffsetY= 0
DXF ScaleX= 1
DXF ScaleY= 10

--- Silver Lake Branch.p01 (plan) ---

Plan Title=Multiple Run
Program Version=4.10
Short Identifier=Multiple
Geom File=g01
Flow File=f01
Subcritical Flow
K Sum by GR= 0
Std Step Tol= 0.01
Critical Tol= 0.01
Num of Std Step Trials= 20
Max Error Tol= 0.3
Flow Tol Ratio= 0.001
Split Flow NTrial= 30
Split Flow Tol= 0.02
Split Flow Ratio= 0.02
Log Output Level= 0
Friction Slope Method= 1
Unsteady Friction Slope Method= 2
Unsteady Bridges Friction Slope Method= 1
Parabolic Critical Depth
Global Vel Dist= 1 , 1 , 1
Global Log Level= 0
CheckData=True
Encroach Param=-1 ,0,0, 0
BEGIN DESCRIPTION:
Multiple Run
END DESCRIPTION:
Computation Interval=1HOUR
Output Interval=1HOUR
Run HTab= 0
Run UNet= 0
Run PostProcess= 0
Run WQNet= 0
UNET Theta= 1
UNET Theta Warmup= 1
UNET ZTol= 0.02
UNET ZSATol= 0.05
UNET MxIter= 20
UNET MaxInSteps= 0
UNET DtIC= 0
UNET DtMin= 0
UNET MaxCRTS= 20
UNET WFStab= 2
UNET SFStab= 1
UNET WFX= 1
UNET SFX= 1
UNET DSS MLevel= 4
UNET DZMax Abort= 100
UNET Convert EG Bridges= 0
UNET Use Existing IB Tables=-1
UNET Froude Reduction=False
UNET Froude Limit= 1
UNET Froude Power= 10
UNET Time Slicing=0,0, 5
UNET Junction Losses=0
Instantaneous Interval=1HOUR
Write IC File= 0
Write IC File at Sim End=0
Echo Input=False
Echo Parameters=False
Echo Output=False
Write Detailed= 0
WQ AD Non Conservative
WQ ULTIMATE=-1
WQ Max Comp Step=1HOUR
WQ Output Interval=15MIN
WQ Output Selected Increments= 0
WQ Output face flow=0
WQ Output face velocity=0
WQ Output face area=0
WQ Output face dispersion=0
WQ Output cell volume=0
WQ Output cell surface area=0
WQ Output cell continuity=0
WQ Output cumulative cell continuity=0
WQ Output face conc=0
WQ Output face dconc_dx=0
WQ Output face courant=0
WQ Output face peclet=0
WQ Output face adv mass=0
WQ Output face disp mass=0
WQ Output cell mass=0
WQ Output cell source sink temp=0
WQ Output cell source sink nsm=0
WQ Output MaxMinRange=-1
WQ Daily Max Min Mean=-1
WQ Daily Range=0
WQ Daily Time=0
WQ Create Restart=0
WQ Fixed Restart=0
WQ System Summary=0
WQ Use Fixed Temperature=0
Sorting and Armoring Iterations= 10
XS Update Threshold= 0.02
Hydraulics Update Threshold= 0.02
Energy Slope Method= 1
Volume Change Method= 0
XS Weighting Method= 0
Number of US Weighted Cross Sections= 1
Number of DS Weighted Cross Sections= 1
Upstream XS Weight=0.25
Main XS Weight=0.5
Downstream XS Weight=0.25
Number of DS XS's Weighted with US Boundary= 1
Upstream Boundary Weight= 1
Weight of XSs Associated with US Boundary= 0
Number of US XS's Weighted with DS Boundary= 1
Downstream Boundary Weight= 0.5
Weight of XSs Associated with DS Boundary= 0.5
Sediment Output Level= 4
Mass or Volume Output= 0
Output Increment Type= 1
Profile and TS Output Increment= 10
XS Output Flag= 0
XS Output Increment= 10
Disregard all LS=0
Disregard all Conn=0
Disregard all Breaches=0
Disregard all Pumps=0

--- Silver Lake Branch.f01 (steady flow) ---

Flow Title=Multiple
Number of Profiles=7
Profile Names=10-year,25-year,50-year,1pct_min,100-year,1pct_plu,500-year
River Rch & RM= Silver Lake Bran,Reach-1,10566
     695     961    1182     722    1440    2873    2135
River Rch & RM= Silver Lake Bran,Reach-1,7343
     841    1165    1434     874    1743    3479    2578
Boundary for River Rch & Prof#=Silver Lake Bran,Reach-1,1
Up Type=0
Dn Type=3
Dn Slope=0.005
Boundary for River Rch & Prof#=Silver Lake Bran,Reach-1,2
Up Type=0
Dn Type=3
Dn Slope=0.005
Boundary for River Rch & Prof#=Silver Lake Bran,Reach-1,3
Up Type=0
Dn Type=3
Dn Slope=0.005
Boundary for River Rch & Prof#=Silver Lake Bran,Reach-1,4
Up Type=0
Dn Type=3
Dn Slope=0.005
Boundary for River Rch & Prof#=Silver Lake Bran,Reach-1,5
Up Type=0
Dn Type=3
Dn Slope=0.005
Boundary for River Rch & Prof#=Silver Lake Bran,Reach-1,6
Up Type=0
Dn Type=3
Dn Slope=0.005
Boundary for River Rch & Prof#=Silver Lake Bran,Reach-1,7
Up Type=0
Dn Type=3
Dn Slope=0.005

--- Silver Lake Branch.g01 (geometry) ---

Geom Title=Existing Conditions
Program Version=4.10

River Reach=Silver Lake Bran,Reach-1
Reach XY= 30
        2409679.        7028610.       2409777.6      7028621.39
      2409828.48      7029194.78      2409729.09      7029425.39
      2409777.03      7029604.11      2409632.49      7029768.48
      2409576.75      7030054.07       2409480.2       7030220.5
      2409428.68       7030985.2      2409529.03      7031075.24
      2409488.41      7031566.62      2409625.45      7031761.47
      2409636.82      7031916.19      2409918.24      7032200.32
      2410027.21      7032416.11      2409880.09      7032849.46
      2410177.78       7033370.5      2410176.74      7033554.06
      2410079.52      7033775.22      2410077.78       7034049.5
      2409978.64      7034289.85      2409980.22       7034549.5
      2410128.48      7034975.22      2410128.48      7035494.78
      2410030.22       7035820.5      2410026.74      7036054.06
      2409823.17       7036662.3      2409089.76      7037450.32
      2408823.17       7038012.3        2408479.        7038510.

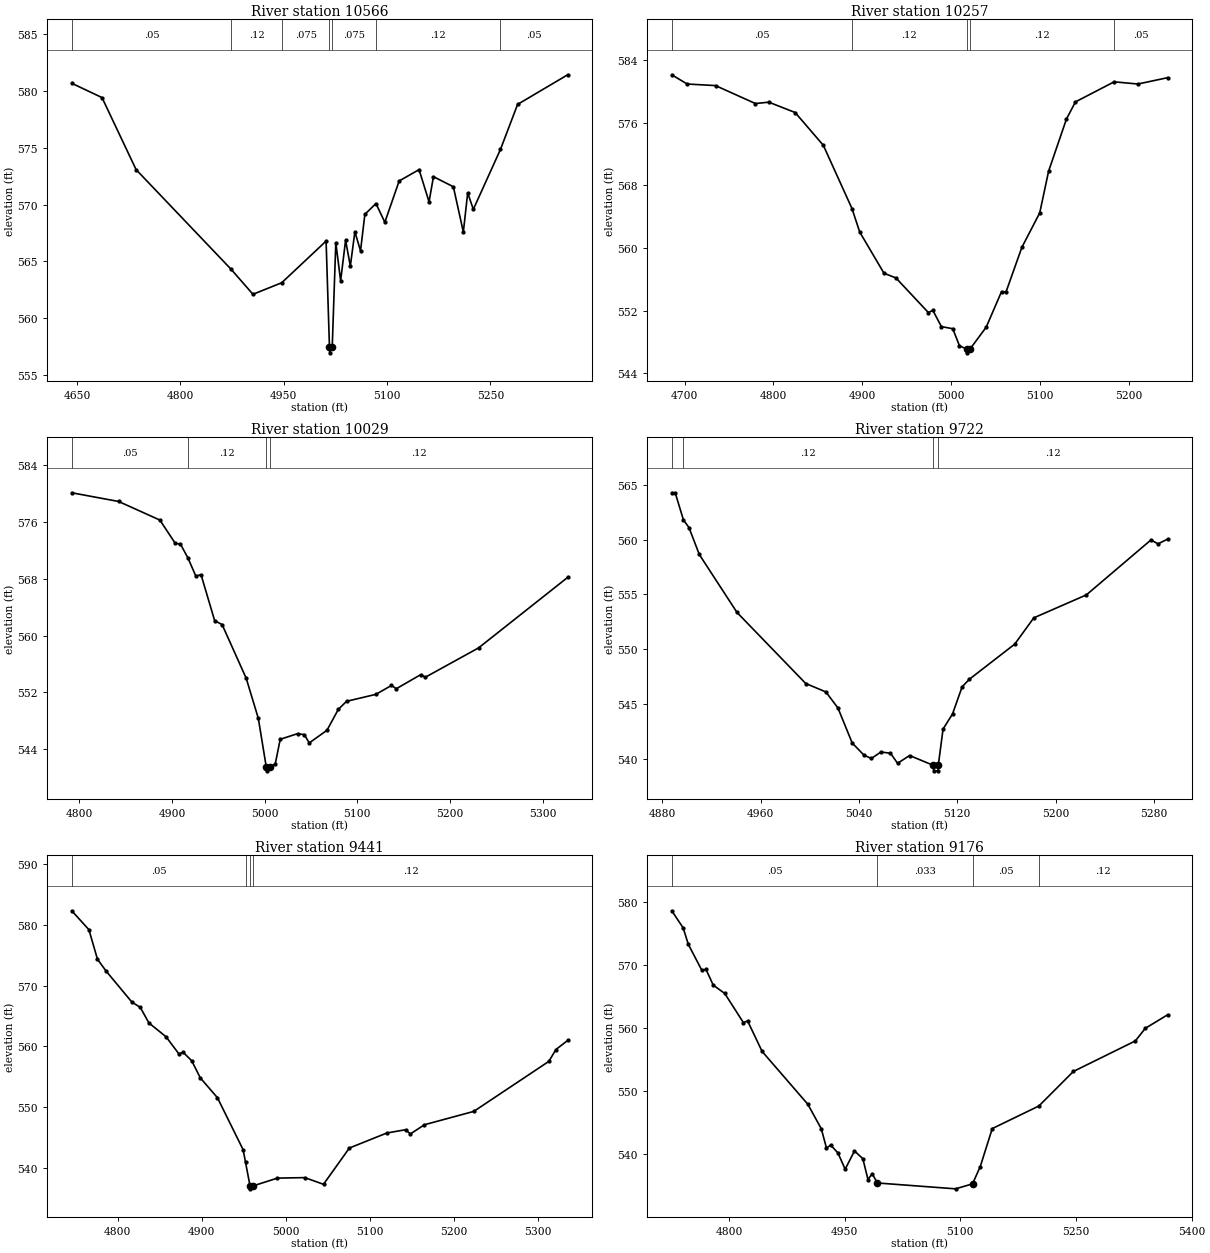
Type RM Length L Ch R = 1 ,10566   ,309,309,309
BEGIN DESCRIPTION:
Silver Lake Branch 27.0
END DESCRIPTION:
XS GIS Cut Line= 3
      2409521.82      7029035.11      2409813.95      7029317.54
      2410006.25      7029565.47
#Sta/Elev= 30
  4642.2  580.69  4686.1  579.43  4735.6  573.08  4873.8  564.28  4905.3  562.09
  4947.1  563.11  5011.5  566.78  5016.4  557.43  5016.7  556.93  5020.4  557.43
  5025.6  566.64  5032.6  563.28  5039.8  566.85  5046.7  564.58  5053.3   567.6
  5061.5  565.92  5067.8  569.14  5083.9  570.09  5096.8  568.44  5117.6  572.08
  5146.5  573.08    5161  570.24  5167.4  572.46  5196.3  571.57  5210.8  567.58
  5217.1  571.03  5225.3  569.58  5264.7  574.86  5289.6  578.83  5362.3  581.44
#Mann= 7 ,-1 , 0
  4642.2     .05       0  4873.8     .12       0  4947.1    .075       0
  5016.4     .07       0  5020.4    .075       0  5083.9     .12       0
  5264.7     .05       0
Bank Sta=5016.4,5020.4
XS Rating Curve= 0 ,0
Exp/Cntr=0.3,0.1

Type RM Length L Ch R = 1 ,10257   ,228,228,228
BEGIN DESCRIPTION:
Silver Lake Branch 26.0
END DESCRIPTION:
XS GIS Cut Line= 3
      2409472.11       7029495.7        2409779.        7029560.
      2410022.38      7029580.54
#Sta/Elev= 30
  4685.6  582.11  4702.9  580.93  4734.8  580.73  4779.6  578.44  4794.8  578.61
  4824.4  577.29  4856.1   573.1  4888.3  565.03    4897  562.03  4924.3  556.77
  4937.8  556.16  4974.2  551.75  4979.3  552.02  4988.9  549.95  5001.7  549.68
  5009.2   547.5  5017.2   547.1  5017.5   546.6  5021.2   547.1  5039.3  549.88
  5056.5  554.41  5061.5  554.35  5079.4  560.07  5099.5  564.47  5109.5  569.81
  5129.6  576.47  5139.7  578.65  5183.2  581.21  5209.9  580.93  5243.4  581.74
#Mann= 5 ,-1 , 0
  4685.6     .05       0  4888.3     .12       0  5017.2     .07       0
  5021.2     .12       0  5183.2     .05       0
Bank Sta=5017.2,5021.2
XS Rating Curve= 0 ,0
Exp/Cntr=0.3,0.1

Type RM Length L Ch R = 1 ,10029   ,307,307,307
BEGIN DESCRIPTION:
Silver Lake Branch 25.0
END DESCRIPTION:
XS GIS Cut Line= 3
      2409487.19      7029662.96      2409624.89      7029733.27
      2409984.68      7029856.13
#Sta/Elev= 30
    4792  580.04  4842.5  578.82    4887  576.21  4903.6  572.94  4909.2  572.83
  4917.2  570.91  4925.8  568.34  4931.4  568.54  4946.1  562.08  4954.1  561.54
  4980.1     554  4993.2  548.36  5001.8   541.5    5002     541  5005.8   541.5
  5011.5  542.01  5016.8  545.43  5035.5  546.22  5042.8  546.08  5048.1  544.92
  5067.2  546.69  5079.4  549.62  5088.3  550.76    5120  551.74  5136.8  552.99
    5142  552.53  5168.1  554.49  5173.4  554.15  5230.7  558.26  5326.8  568.16
#Mann= 4 ,-1 , 0
    4792     .05       0  4917.2     .12       0  5001.8     .07       0
  5005.8     .12       0
Bank Sta=5001.8,5005.8
XS Rating Curve= 0 ,0
Exp/Cntr=0.3,0.1

Type RM Length L Ch R = 1 ,9722    ,281,281,281
BEGIN DESCRIPTION:
Silver Lake Branch 24.0
END DESCRIPTION:
XS GIS Cut Line= 3
      2409478.98      7029959.99        2409579.        7030010.
      2409829.02      7030160.01
#Sta/Elev= 30
  4887.8  564.29  4890.6  564.29  4897.3  561.81  4901.8  561.11  4910.2  558.65
  4940.9  553.35  4996.8  546.86  5013.2  546.09    5023  544.62  5034.6  541.42
  5044.3   540.3  5050.2  540.01  5057.9   540.6  5065.7  540.49  5071.5  539.57
  5081.3  540.28  5100.6  539.38  5100.9  538.88  5104.4  538.88  5104.6  539.38
  5108.5   542.7  5116.2  544.08    5124  546.56  5129.9  547.25  5166.8  550.46
  5182.3  552.86  5225.1  554.96  5277.6  559.98  5283.4  559.62  5291.2  560.06
#Mann= 4 ,-1 , 0
  4887.8     .05       0  4897.3     .12       0  5100.6     .07       0
  5104.6     .12       0
Bank Sta=5100.6,5104.6
XS Rating Curve= 0 ,0
Exp/Cntr=0.3,0.1

Type RM Length L Ch R = 1 ,9441    ,265,265,265
BEGIN DESCRIPTION:
Silver Lake Branch 23.0
END DESCRIPTION:
XS GIS Cut Line= 3
      2409228.96      7030209.99        2409479.        7030260.
        2409779.        7030410.
#Sta/Elev= 30
  4745.4  582.36  4765.8  579.24    4776  574.37  4786.2  572.43  4816.8  567.33
    4827  566.42  4837.2  563.87  4857.6  561.59  4872.9  558.77    4878  559.02
  4888.2  557.63  4898.4  554.81  4918.8  551.54  4949.4  542.96  4952.3  540.86
  4957.6  537.01  4957.9  536.51  4961.6  537.01  4990.2  538.28  5022.8  538.36
  5045.1  537.26  5075.9  543.24  5120.6  545.72  5142.9  546.26  5148.5  545.56
  5165.3  547.08    5224  549.28  5313.4  557.53  5321.8  559.48  5335.8  560.98
#Mann= 4 ,-1 , 0
  4745.4     .05       0  4952.3     .12       0  4957.6     .07       0
  4961.6     .12       0
Bank Sta=4957.6,4961.6
XS Rating Curve= 0 ,0
Exp/Cntr=0.3,0.1

Type RM Length L Ch R = 1 ,9176    ,251,251,251
BEGIN DESCRIPTION:
Silver Lake Branch 22.0
END DESCRIPTION:
XS GIS Cut Line= 3
        2409179.        7030410.        2409429.        7030510.
      2409800.69      7030471.81
#Sta/Elev= 30
  4725.9  578.65  4740.7  575.93  4747.4  573.31  4764.9  569.21  4770.3  569.34
  4779.7  566.85  4794.6  565.53  4818.8   560.9  4824.2  561.18    4843  556.34
  4902.3  547.95  4919.8  544.05  4926.5  540.99  4931.9  541.48  4941.3  540.23
  4950.7  537.64  4962.8  540.54  4973.6  539.32  4980.3     536  4985.7  536.94
  4992.5  535.46  5093.9  534.53  5115.8  535.32  5125.8  538.05  5141.4  544.09
  5201.9  547.68  5246.5  553.15  5326.9     558  5339.8     560  5368.8  562.15
#Mann= 4 ,-1 , 0
  4725.9     .05       0  4992.5    .033       0  5115.8     .05       0
  5201.9     .12       0
Bank Sta=4992.5,5115.8
XS Rating Curve= 0 ,0
Exp/Cntr=0.3,0.1

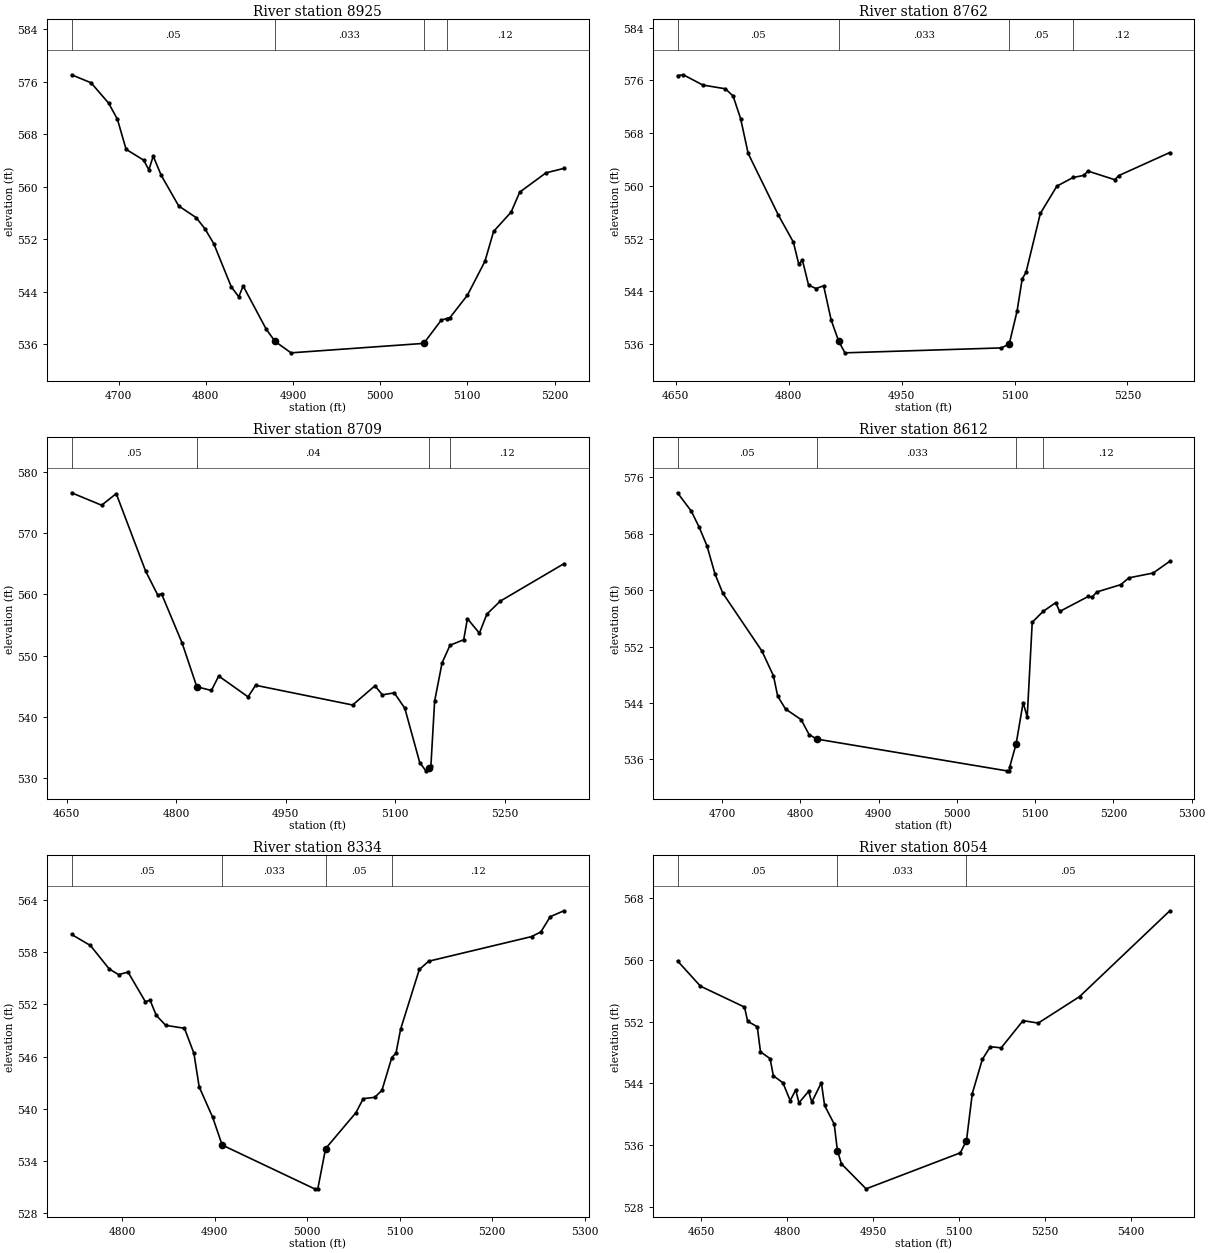
Type RM Length L Ch R = 1 ,8925    ,163,163,163
BEGIN DESCRIPTION:
Silver Lake Branch 21.0
END DESCRIPTION:
XS GIS Cut Line= 3
      2409076.76      7030726.54        2409429.        7030760.
      2409639.59      7030766.07
#Sta/Elev= 30
  4646.2  577.04  4668.5  575.82  4688.6  572.73  4698.7  570.28  4708.7  565.68
  4728.8  564.04  4734.8  562.56  4739.8  564.65  4748.9  561.74    4769  557.06
  4789.1  555.27  4799.1  553.58  4809.2  551.32  4829.3  544.73  4837.9  543.21
  4842.9  544.87  4869.4  538.27  4879.5  536.42  4897.8  534.68    5050  536.12
  5070.1  539.67  5076.1   539.9  5080.1  540.05  5100.1  543.47  5120.1  548.61
  5130.1  553.18  5150.1  556.11  5160.1  559.17  5190.1   562.1  5210.7  562.78
#Mann= 4 ,-1 , 0
  4646.2     .05       0  4879.5    .033       0    5050     .05       0
  5076.1     .12       0
Bank Sta=4879.5,5050
XS Rating Curve= 0 ,0
Exp/Cntr=0.3,0.1

Type RM Length L Ch R = 1 ,8762    ,53,53,53
BEGIN DESCRIPTION:
Silver Lake Branch 20.2
END DESCRIPTION:
XS GIS Cut Line= 3
      2409085.39      7030965.43      2409318.19      7030950.48
      2409725.64      7030847.26
#Sta/Elev= 30
  4652.6  576.74  4660.3  576.86  4686.3   575.3  4716.3  574.73  4726.4  573.63
  4736.4   570.2  4746.4  564.92  4786.5  555.56  4806.5  551.44  4813.5  548.14
  4818.5  548.69  4826.6  544.93  4836.6  544.41  4846.6  544.83  4856.6  539.63
  4866.7  536.38  4874.9  534.65  5082.7   535.4    5093     536  5103.4  540.98
  5110.2  545.87  5115.3  546.87  5134.3  555.81  5156.3  559.96  5177.8  561.27
  5192.1  561.59  5197.3  562.25  5233.1  560.93  5238.3  561.55  5306.2  565.06
#Mann= 4 ,-1 , 0
  4652.6     .05       0  4866.7    .033       0    5093     .05       0
  5177.8     .12       0
Bank Sta=4866.7,5093
XS Rating Curve= 0 ,0
Exp/Cntr=0.3,0.1

Type RM Length L Ch R = 1 ,8709    ,97,97,97
BEGIN DESCRIPTION:
Silver Lake Branch 20.1
END DESCRIPTION:
XS GIS Cut Line= 3
        2409088.      7031012.69      2409320.76      7030997.74
      2409752.25      7030907.85
#Sta/Elev= 30
  4656.8  576.58  4697.9  574.55  4717.9  576.44    4758  563.83  4774.9  559.85
  4779.9   560.1  4808.1  552.05  4828.2  544.91  4848.2   544.3  4858.2  546.66
  4898.4  543.26  4908.7  545.15  5041.5  541.93  5072.1  545.06  5082.3  543.59
  5098.6  543.91    5113  541.39  5133.4  532.54  5141.8  531.18  5145.6  531.68
  5148.7  531.98  5153.8  542.56    5164  548.81  5174.9  551.69  5193.6  552.58
  5198.7  556.03  5215.1  553.65  5225.3  556.77  5243.7  558.89  5330.8     565
#Mann= 4 ,-1 , 0
  4656.8     .05       0  4828.2     .04       0  5145.6    .033       0
  5174.9     .12       0
Bank Sta=4828.2,5145.6
XS Rating Curve= 0 ,0
Exp/Cntr=0.3,0.1

Type RM Length L Ch R = 1 ,8612    ,278,278,278
BEGIN DESCRIPTION:
Silver Lake Branch 20.0
END DESCRIPTION:
XS GIS Cut Line= 3
      2409141.37       7031063.8       2409425.6      7031043.29
       2409759.7      7030961.23
#Sta/Elev= 30
  4643.1  573.81  4660.8  571.19  4670.8  568.92  4680.8  566.27  4690.9  562.33
  4700.9  559.59    4751  551.36  4765.7  547.85  4771.1  544.97  4781.1  543.15
  4801.1  541.64  4811.2  539.52  4821.2  538.88  5063.7  534.38  5067.2  534.38
  5067.4  534.88  5075.7  538.18  5084.7  544.07  5089.9     542  5096.3  555.45
  5110.1  556.98  5126.3  558.23  5131.4  556.98  5167.9  559.11    5173  559.03
  5178.7  559.74  5209.4  560.78  5219.9  561.75  5250.8  562.43  5272.1   564.1
#Mann= 4 ,-1 , 0
  4643.1     .05       0  4821.2    .033       0  5075.7     .05       0
  5110.1     .12       0
Bank Sta=4821.2,5075.7
XS Rating Curve= 0 ,0
Exp/Cntr=0.3,0.1

Type RM Length L Ch R = 1 ,8334    ,280,280,280
BEGIN DESCRIPTION:
Silver Lake Branch 19.0
END DESCRIPTION:
XS GIS Cut Line= 3
        2409279.        7031310.      2409598.51      7031251.37
      2409803.68      7031280.68
#Sta/Elev= 30
  4745.5  560.05  4765.8  558.78  4786.2  556.08  4796.3  555.43  4806.5  555.72
  4825.2  552.32  4830.3  552.49    4837  550.75  4847.2   549.6  4867.5  549.26
  4877.7  546.38  4883.4  542.52    4898  539.02  4908.2  535.84  5008.1   530.8
  5011.6   530.8    5020  535.42  5052.9  539.57  5060.7  541.17  5073.1  541.32
  5080.9  542.12  5091.6   545.9  5096.1   546.4  5101.1  549.15  5121.3  556.02
  5131.4  556.97  5242.6   559.8  5252.7  560.34  5262.8  562.09  5277.6  562.77
#Mann= 4 ,-1 , 0
  4745.5     .05       0  4908.2    .033       0    5020     .05       0
  5091.6     .12       0
Bank Sta=4908.2,5020
XS Rating Curve= 0 ,0
Exp/Cntr=0.3,0.1

Type RM Length L Ch R = 1 ,8054    ,346,346,346
BEGIN DESCRIPTION:
Silver Lake Branch 18.0
END DESCRIPTION:
XS GIS Cut Line= 3
      2409153.26      7031360.93      2409528.05      7031548.33
      2409948.58      7031420.34
#Sta/Elev= 30
    4609   559.9    4649  556.62  4725.8  553.91  4731.4  552.06  4748.1  551.36
  4753.7  548.11  4770.5  547.22  4776.1     545  4792.8  544.09  4805.5  541.78
  4815.2  543.16  4820.8  541.49  4837.6  542.98  4843.2  541.58  4859.9   544.1
  4865.5  541.15  4882.3  538.73  4887.9  535.27  4894.9  533.57  4937.9  530.33
  5102.2     535    5113   536.6  5123.1  542.69  5140.6  547.12  5154.5  548.77
  5173.5  548.62  5211.6  552.15  5238.1  551.83  5310.1  555.26  5467.6   566.4
#Mann= 3 ,-1 , 0
    4609     .05       0  4887.9    .033       0    5113     .05       0
Bank Sta=4887.9,5113
XS Rating Curve= 0 ,0
Exp/Cntr=0.3,0.1

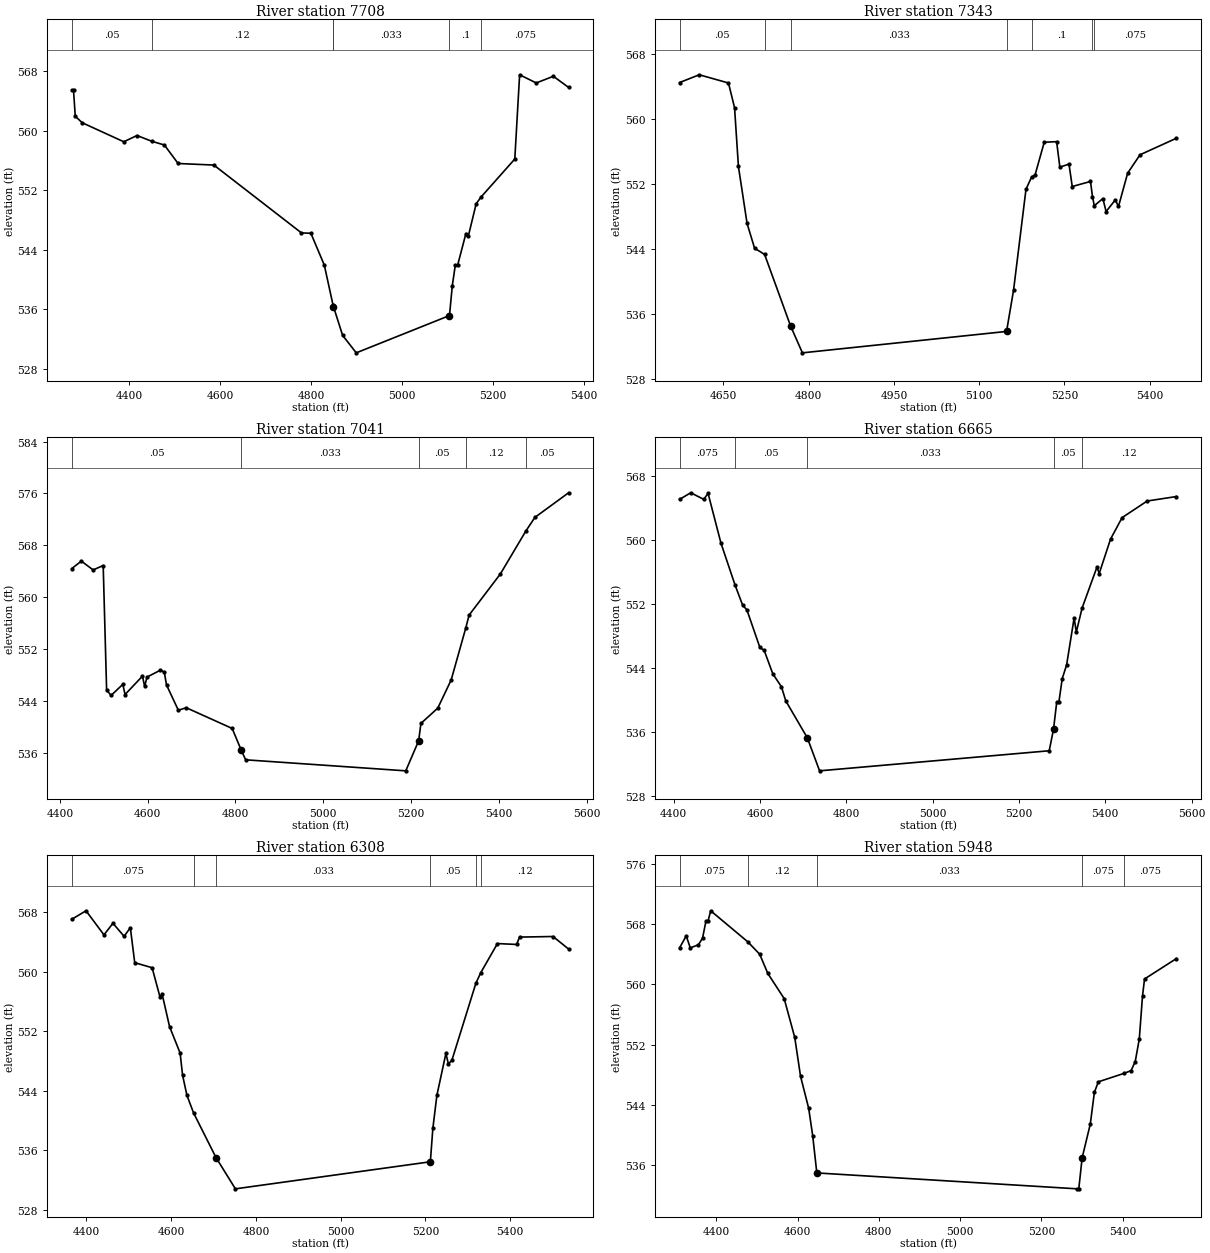
Type RM Length L Ch R = 1 ,7708    ,365,365,365
BEGIN DESCRIPTION:
Silver Lake Branch 17.0
END DESCRIPTION:
XS GIS Cut Line= 3
       2408906.4      7031895.73      2409747.46      7031813.45
      2409980.59      7031731.17
#Sta/Elev= 30
  4273.8  565.43  4277.5  565.43  4281.4  561.95  4296.5  561.08    4388  558.52
  4417.1  559.36  4449.1   558.6  4477.4  558.08  4507.5   555.6  4586.1  555.39
  4778.8  546.27  4799.4  546.23    4829  541.94  4848.2  536.56  4849.1  536.37
  4869.2  532.51  4899.2  530.16  5104.2  535.17  5110.4  539.19  5117.1  541.98
  5122.3  541.98  5140.3  546.19  5145.6  545.83  5162.9   550.2  5173.8  551.11
  5247.8   556.2  5258.4  567.52    5295  566.42  5332.6  567.32  5366.1  565.82
#Mann= 6 ,-1 , 0
  4273.8     .05       0  4449.1     .12       0  4848.2      .1       0
  4849.1    .033       0  5104.2      .1       0  5173.8    .075       0
Bank Sta=4849.1,5104.2
XS Rating Curve= 0 ,0
Exp/Cntr=0.3,0.1

Type RM Length L Ch R = 1 ,7343    ,302,302,302
BEGIN DESCRIPTION:
Silver Lake Branch 16.0
END DESCRIPTION:
XS GIS Cut Line= 3
      2409441.18      7032288.85        2409829.        7032110.
      2410044.29        7031718.
#Sta/Elev= 30
  4572.9  564.48  4607.5  565.43  4658.9  564.42  4669.6  561.38  4676.4  554.17
  4691.6  547.17  4704.8  544.12  4722.5  543.35  4768.2  534.56    4789  531.26
  5148.3  533.89  5160.6  538.95  5182.5  551.36  5192.5  552.89  5198.5  553.13
  5214.6  557.14  5236.4  557.21  5242.1  554.08  5258.2  554.45  5263.9   551.7
    5296  552.32  5299.5  550.47  5302.7  549.34  5317.8  550.22  5323.5  548.62
  5339.6  550.05  5345.3  549.25  5361.4  553.34  5383.2   555.6  5447.2  557.63
#Mann= 7 ,-1 , 0
  4572.9     .05       0  4722.5      .1       0  4768.2    .033       0
  5148.3      .1       0  5192.5      .1       0  5299.5     .05       0
  5302.7    .075       0
Bank Sta=4768.2,5148.3
XS Rating Curve= 0 ,0
Exp/Cntr=0.3,0.1

Type RM Length L Ch R = 1 ,7041    ,376,376,376
BEGIN DESCRIPTION:
Silver Lake Branch 15.0
END DESCRIPTION:
XS GIS Cut Line= 3
      2409421.42      7032300.82      2409827.13      7032386.24
      2410531.76        7032251.
#Sta/Elev= 30
  4427.1  564.42  4448.8  565.57  4475.7  564.21  4498.6  564.89  4506.4  545.67
  4516.6  544.85  4543.3  546.56  4548.4  544.99    4588  547.82  4593.1  546.25
  4598.4  547.68    4629  548.75  4637.8  548.46  4642.9  546.47  4669.9  542.56
  4687.7  542.96  4792.5  539.76    4813  536.44  4823.2  534.92  5188.1  533.22
  5217.5  537.85  5222.6  540.53  5261.1   542.9  5291.6  547.24  5324.9  555.26
  5332.4  557.24  5403.6  563.58  5461.7   570.2  5482.5  572.32  5559.2  576.11
#Mann= 5 ,-1 , 0
  4427.1     .05       0    4813    .033       0  5217.5     .05       0
  5324.9     .12       0  5461.7     .05       0
Bank Sta=4813,5217.5
XS Rating Curve= 0 ,0
Exp/Cntr=0.3,0.1

Type RM Length L Ch R = 1 ,6665    ,357,357,357
BEGIN DESCRIPTION:
Silver Lake Branch 14.0
END DESCRIPTION:
XS GIS Cut Line= 3
      2409343.16      7032670.94      2410218.59      7032692.29
      2410489.05      7032642.47
#Sta/Elev= 30
    4414  565.13  4439.8  565.95  4469.9  565.13  4479.9  565.88  4509.9  559.63
  4542.7  554.37  4559.9  551.91  4569.9   551.3  4599.9  546.61  4609.9  546.24
  4629.9  543.31  4649.9  541.69  4659.9  539.93  4709.9   535.3  4738.2  531.18
  5270.1  533.69  5280.1  536.38  5287.4  539.73  5292.4  539.73  5300.3  542.72
  5310.4  544.42  5327.8  550.29  5332.9  548.54  5346.2  551.52  5380.8  556.67
  5385.9  555.85  5412.1  560.15  5438.9  562.84    5497  564.92  5564.7  565.48
#Mann= 5 ,-1 , 0
    4414    .075       0  4542.7     .05       0  4709.9    .033       0
  5280.1     .05       0  5346.2     .12       0
Bank Sta=4709.9,5280.1
XS Rating Curve= 0 ,0
Exp/Cntr=0.3,0.1

Type RM Length L Ch R = 1 ,6308    ,360,360,360
BEGIN DESCRIPTION:
Silver Lake Branch 13.0
END DESCRIPTION:
XS GIS Cut Line= 3
      2409364.46       7033183.4      2409848.49      7033069.52
      2410423.43      7032714.61
#Sta/Elev= 30
  4365.4  567.08  4398.9  568.22  4441.3  564.98  4462.5  566.54  4488.8  564.79
  4503.6  565.94  4513.9  561.24    4555  560.56  4573.6  556.62  4578.7     557
  4596.1  552.65  4621.1  549.08  4626.9   546.1  4637.2  543.39  4652.8  541.04
  4705.8  535.03  4751.6  530.82  5211.9  534.46  5217.8  538.95  5227.3  543.39
  5248.6  549.03  5254.5  547.62  5262.8  548.12  5319.5  558.49    5331   559.9
  5370.3  563.81  5415.6  563.69  5422.4  564.68  5501.6  564.76  5538.3  563.07
#Mann= 6 ,-1 , 0
  4365.4    .075       0  4652.8     .05       0  4705.8    .033       0
  5211.9     .05       0  5319.5     .05       0    5331     .12       0
Bank Sta=4705.8,5211.9
XS Rating Curve= 0 ,0
Exp/Cntr=0.3,0.1

Type RM Length L Ch R = 1 ,5948    ,395,395,395
BEGIN DESCRIPTION:
Silver Lake Branch 12.0
END DESCRIPTION:
XS GIS Cut Line= 3
      2409442.81      7033361.33      2410054.89      7033304.39
      2410659.89      7033247.45
#Sta/Elev= 30
  4309.8  564.87  4326.1  566.45  4336.1  564.85  4356.2  565.28  4366.2  566.14
  4374.7  568.43  4379.7  568.41  4386.3  569.78  4477.6  565.66  4506.8  564.02
  4526.9  561.46  4567.1  558.13  4593.1  552.98  4607.3  547.84  4627.4  543.57
  4637.4  539.89  4647.4     535  5288.5  532.89    5292  532.89  5300.3  537.01
  5320.4   541.5  5330.4   545.7  5340.2  547.09    5404  548.22  5420.8  548.58
  5430.9  549.78  5440.9  552.76  5448.8  558.47  5453.8  560.73  5532.2  563.44
#Mann= 5 ,-1 , 0
  4309.8    .075       0  4477.6     .12       0  4647.4    .033       0
  5300.3    .075       0    5404    .075       0
Bank Sta=4647.4,5300.3
XS Rating Curve= 0 ,0
Exp/Cntr=0.3,0.1

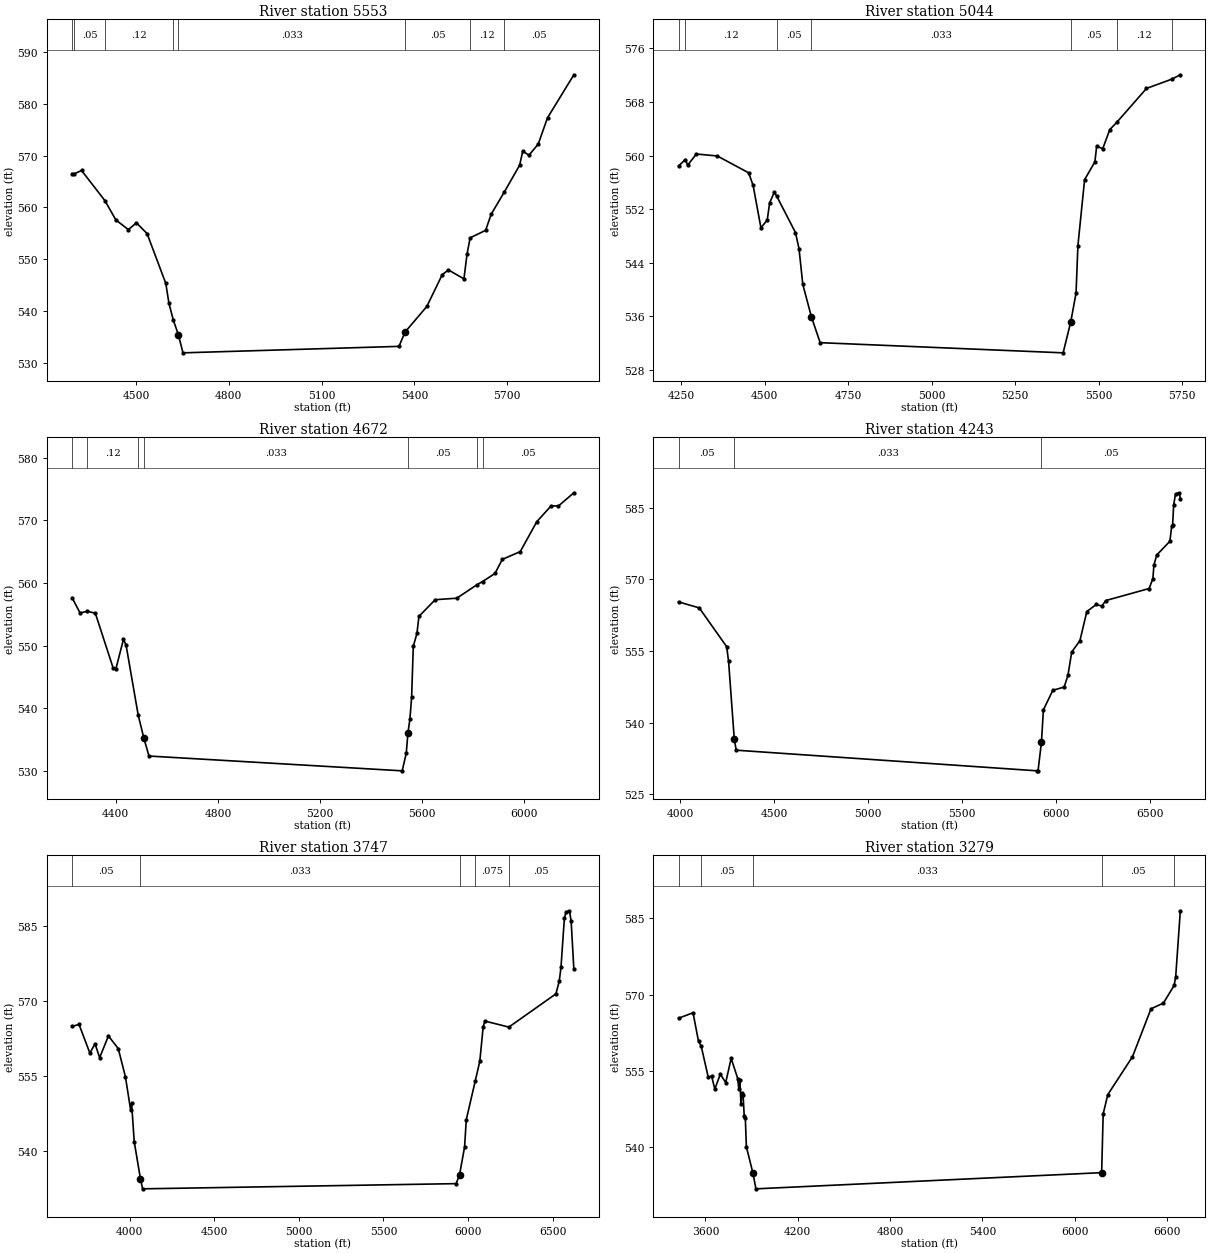
Type RM Length L Ch R = 1 ,5553    ,509,509,509
BEGIN DESCRIPTION:
Silver Lake Branch 11.0
END DESCRIPTION:
XS GIS Cut Line= 3
      2409428.55      7033567.74        2410129.        7033660.
      2411044.16      7033638.92
#Sta/Elev= 30
  4293.5  566.54  4299.9  566.48  4324.2  567.14  4399.5  561.32  4435.2  557.57
  4475.5  555.71  4501.5  557.02    4536  554.94  4596.5   545.3  4606.6  541.46
  4621.1  538.15  4636.9  535.43    4652  531.89  5350.1  533.14  5370.1  535.93
  5440.1  540.85  5490.1  547.02  5510.1  547.91  5560.1  546.19  5570.2     551
  5580.1  554.12  5630.2  555.57  5648.2  558.69    5691  563.01  5740.2  568.17
  5750.2  570.88  5770.2  570.09  5800.2  572.24  5830.2  577.32  5915.4  585.64
#Mann= 8 ,-1 , 0
  4293.5    .075       0  4299.9     .05       0  4399.5     .12       0
  4621.1     .05       0  4636.9    .033       0  5370.1     .05       0
  5580.1     .12       0    5691     .05       0
Bank Sta=4636.9,5370.1
XS Rating Curve= 0 ,0
Exp/Cntr=0.3,0.1

Type RM Length L Ch R = 1 ,5044    ,372,372,372
BEGIN DESCRIPTION:
Silver Lake Branch 10.0
END DESCRIPTION:
XS GIS Cut Line= 4
      2409307.52      7033916.48      2409955.25      7034137.14
      2410154.54      7034137.14      2410738.15      7033930.74
#Sta/Elev= 30
    4242  558.44  4262.5  559.41  4269.2  558.55  4295.3  560.23    4358  559.94
    4452  557.42  4465.4  555.53  4488.7   549.2  4507.7  550.37  4514.7  552.92
  4528.8  554.52  4535.9  553.94  4592.2  548.49  4602.8  546.08  4614.1  540.75
  4640.1  535.86  4666.1  532.04  5393.7  530.52  5416.7   535.2  5432.3  539.43
  5437.9  546.53  5457.9  556.39  5488.8  559.06  5494.1  561.41  5512.2  561.02
  5533.4  563.88  5554.6  564.98  5643.3  570.03  5718.3   571.4  5744.6  572.07
#Mann= 7 ,-1 , 0
    4242     .05       0  4262.5     .12       0  4535.9     .05       0
  4640.1    .033       0  5416.7     .05       0  5554.6     .12       0
  5718.3     .05       0
Bank Sta=4640.1,5416.7
XS Rating Curve= 0 ,0
Exp/Cntr=0.3,0.1

Type RM Length L Ch R = 1 ,4672    ,429,429,429
BEGIN DESCRIPTION:
Silver Lake Branch 9.0
END DESCRIPTION:
XS GIS Cut Line= 3
      2409207.91      7034493.01      2410353.83      7034493.01
      2410980.19       7033966.3
#Sta/Elev= 30
  4229.2  557.67  4260.3  555.23  4289.5  555.49  4320.3  555.18  4390.3  546.41
  4400.3  546.24  4430.3     551  4440.3  550.17    4488  538.95  4510.3  535.25
  4530.3  532.41  5521.5  530.05  5537.5  532.89  5544.1  536.14  5551.7  538.27
  5558.4  541.81  5564.9   549.9  5579.2  551.96    5587  554.68  5650.7  557.34
  5735.3  557.58  5814.3  559.73  5836.5  560.24  5884.8  561.53  5913.4  563.77
  5983.7  565.01  6048.2  569.77  6104.7  572.31  6133.3  572.29  6193.5  574.39
#Mann= 7 ,-1 , 0
  4229.2     .05       0  4289.5     .12       0    4488     .05       0
  4510.3    .033       0  5544.1     .05       0  5814.3     .12       0
  5836.5     .05       0
Bank Sta=4510.3,5544.1
XS Rating Curve= 0 ,0
Exp/Cntr=0.3,0.1

Type RM Length L Ch R = 1 ,4243    ,496,496,496
BEGIN DESCRIPTION:
Silver Lake Branch 8.0
END DESCRIPTION:
XS GIS Cut Line= 3
      2409086.91      7034735.01      2409983.72      7034898.71
      2411734.27      7034720.81
#Sta/Elev= 30
  3992.4  565.29  4102.5  564.04  4248.7  555.91  4258.8  552.85  4289.3  536.49
  4299.5  534.25  5902.7  529.93  5906.2  529.93  5924.5  536.02  5934.7   542.7
  5984.8  546.78  6045.2  547.47  6065.3   549.9  6085.4   554.8  6129.1  557.17
  6165.8  563.27    6216  564.75  6246.2  564.42  6266.3  565.57  6497.5  568.09
  6517.6  570.17  6522.9  572.96  6537.7  575.09    6608  577.98  6617.6  581.11
  6622.6  581.42  6628.1  585.58  6638.2  587.91  6658.3  588.13  6663.6  586.93
#Mann= 3 ,-1 , 0
  3992.4     .05       0  4289.3    .033       0  5924.5     .05       0
Bank Sta=4289.3,5924.5
XS Rating Curve= 0 ,0
Exp/Cntr=0.3,0.1

Type RM Length L Ch R = 1 ,3747    ,468,468,468
BEGIN DESCRIPTION:
Silver Lake Branch 7.0
END DESCRIPTION:
XS GIS Cut Line= 3
        2408973.      7034720.75       2410019.3      7035368.46
      2411754.98      7035382.69
#Sta/Elev= 30
  3659.7  564.94    3701  565.33  3764.8  559.61  3795.5  561.46  3822.7  558.69
  3874.7  563.03  3932.6  560.51  3975.1  554.87  4005.9  548.23  4011.7  549.59
  4027.1  541.89  4063.8   534.5  4076.6  532.46    5930   533.5    5950  535.24
    5980  540.81    5990   546.3  6043.7  554.11    6070  557.97    6090  564.87
    6100  566.01  6241.7   564.8    6520  571.45    6540  574.04    6550  576.82
    6570  586.58    6580  587.81    6600  588.06    6610  585.97    6626  576.34
#Mann= 5 ,-1 , 0
  3659.7     .05       0  4063.8    .033       0    5950     .05       0
  6043.7    .075       0  6241.7     .05       0
Bank Sta=4063.8,5950
XS Rating Curve= 0 ,0
Exp/Cntr=0.3,0.1

Type RM Length L Ch R = 1 ,3279    ,457,457,457
BEGIN DESCRIPTION:
Silver Lake Branch 6.0
END DESCRIPTION:
XS GIS Cut Line= 3
      2408901.86      7034713.65      2410083.36      7035852.45
      2411699.08      7035738.57
#Sta/Elev= 30
  3425.4  565.36  3519.7  566.43  3555.2  560.81  3572.1  559.95  3618.7  553.73
  3640.1  553.99  3661.2  551.43  3696.7  554.36  3731.9  552.71  3767.4  557.47
  3809.9  553.51  3816.8  551.52    3824  553.25    3831  548.43  3838.1  550.69
  3845.1   550.2  3852.1   546.2  3859.3  545.84  3866.2   540.1  3908.7  534.92
  3928.2  531.82  6174.8     535  6184.8  546.56  6214.9  550.35  6375.3   557.8
  6495.6  567.22  6575.8  568.32  6645.8   571.8    6656   573.5  6686.1  586.48
#Mann= 5 ,-1 , 0
  3425.4    .075       0  3572.1     .05       0  3908.7    .033       0
  6174.8     .05       0  6645.8    .075       0
Bank Sta=3908.7,6174.8
XS Rating Curve= 0 ,0
Exp/Cntr=0.3,0.1

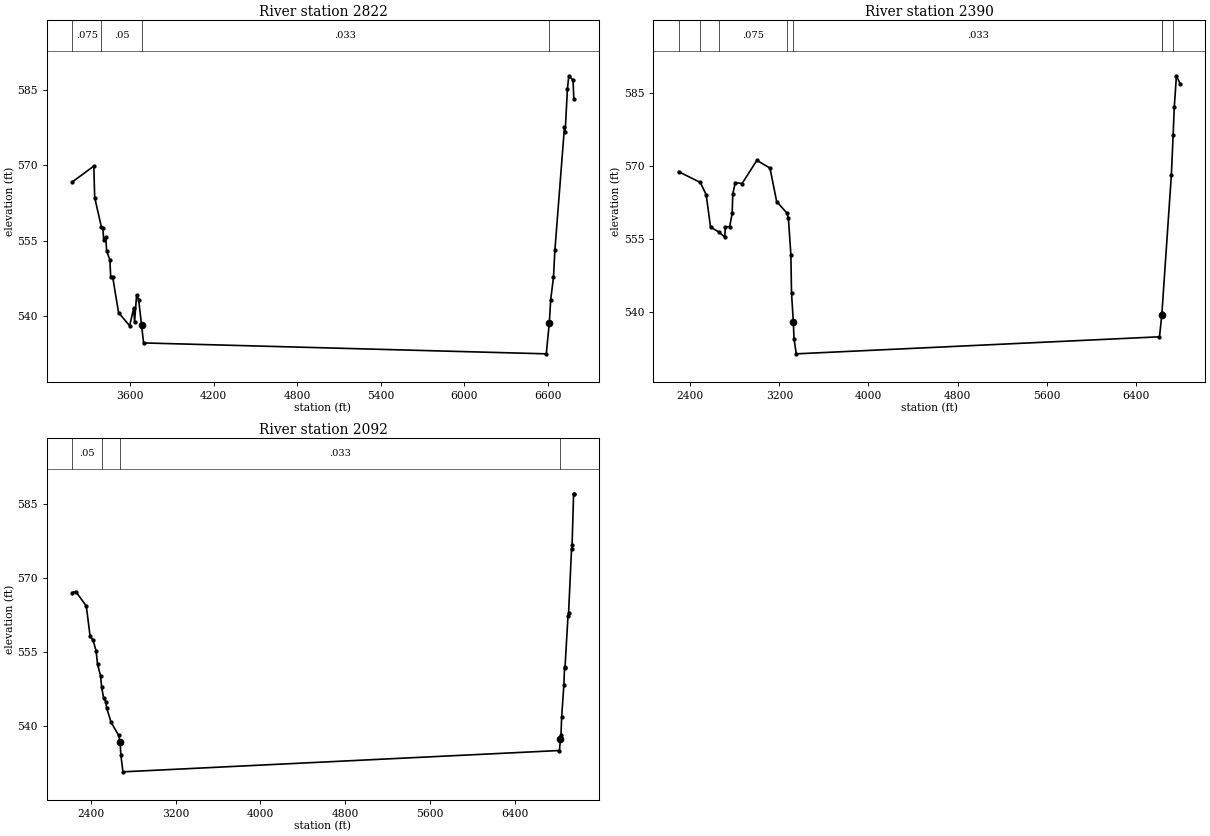
Type RM Length L Ch R = 1 ,2822    ,432,432,432
BEGIN DESCRIPTION:
Silver Lake Branch 5.0
END DESCRIPTION:
XS GIS Cut Line= 3
       2408880.5      7034770.58      2409997.95      7036300.85
       2411705.1      7036201.27
#Sta/Elev= 30
  3183.7  566.67    3340  569.88  3346.2  563.58  3393.7  557.79  3404.9  557.57
  3411.1  555.05  3425.7  555.74  3431.9  552.93  3455.1  551.17  3461.3  547.75
  3475.9  547.66  3517.7   540.6  3597.2  537.97  3626.5  541.48  3632.7  538.72
  3647.4  544.18  3662.1  543.15  3682.9  538.09  3697.6  534.54  6590.4  532.36
  6612.2  538.54  6622.2   543.2  6642.2  547.64  6652.3  553.06    6721  577.62
    6726  576.61  6742.4  585.28  6752.4  587.92  6782.5  587.06  6788.6  583.28
#Mann= 4 ,-1 , 0
  3183.7    .075       0  3393.7     .05       0  3682.9    .033       0
  6612.2     .05       0
Bank Sta=3682.9,6612.2
XS Rating Curve= 0 ,0
Exp/Cntr=0.3,0.1

Type RM Length L Ch R = 1 ,2390    ,298,298,298
BEGIN DESCRIPTION:
Silver Lake Branch 4.0
END DESCRIPTION:
XS GIS Cut Line= 3
      2408553.08      7034279.45      2409748.84      7036614.02
      2411592.25      7036991.25
#Sta/Elev= 30
  2294.7  568.81    2490   566.6  2543.1  564.07  2581.9  557.45  2658.5  556.42
  2709.5  555.41  2715.1  557.48  2753.9  557.56  2776.1  560.26  2781.7  564.23
  2803.9  566.58  2864.9  566.37  2998.1  571.12  3115.5  569.53  3175.7  562.68
  3269.3  560.29  3281.1  559.22  3303.3   551.8  3308.9  543.96  3325.5     538
  3331.1  534.64  3351.6  531.51  6612.3     535  6632.7   539.4    6634  539.83
  6718.8  568.11  6734.6  576.21  6744.9  581.94  6764.2  588.43  6799.3  586.73
#Mann= 8 ,-1 , 0
  2294.7      .1       0    2490     .05       0  2658.5    .075       0
  3269.3     .05       0  3325.5    .033       0  6632.7     .05       0
    6634    .075       0  6734.6     .05       0
Bank Sta=3325.5,6632.7
XS Rating Curve= 0 ,0
Exp/Cntr=0.3,0.1

Type RM Length L Ch R = 1 ,2092    ,0,0,0
BEGIN DESCRIPTION:
Silver Lake Branch 3.0
END DESCRIPTION:
XS GIS Cut Line= 3
      2407777.27      7034791.92      2409713.25      7036934.31
      2411479.03      7037460.01
#Sta/Elev= 30
  2224.9  566.97  2260.4  567.18    2359  564.25  2394.9  558.12  2423.3  557.31
  2451.4  555.16  2465.2  552.47  2493.5  550.09  2503.5  547.84  2521.9  545.66
  2543.6  544.85  2550.3  543.66  2592.9   540.7  2663.9  538.08  2678.1  536.65
  2684.8  534.05  2704.7  530.68  6819.1     535  6828.2   537.4  6833.4   538.2
    6840  541.84  6860.9  548.36  6866.6  551.66  6871.8  551.96  6899.8  562.32
    6905  562.85    6933  575.79  6938.2  576.68  6952.2  586.98  6954.8  586.98
#Mann= 4 ,-1 , 0
  2224.9     .05       0  2503.5      .1       0  2678.1    .033       0
  6828.2     .05       0
Bank Sta=2678.1,6828.2
XS Rating Curve= 0 ,0
Exp/Cntr=0.3,0.1

Chan Stop Cuts=-1
Use User Specified Reach Order=0
Composite Channel Slope=5