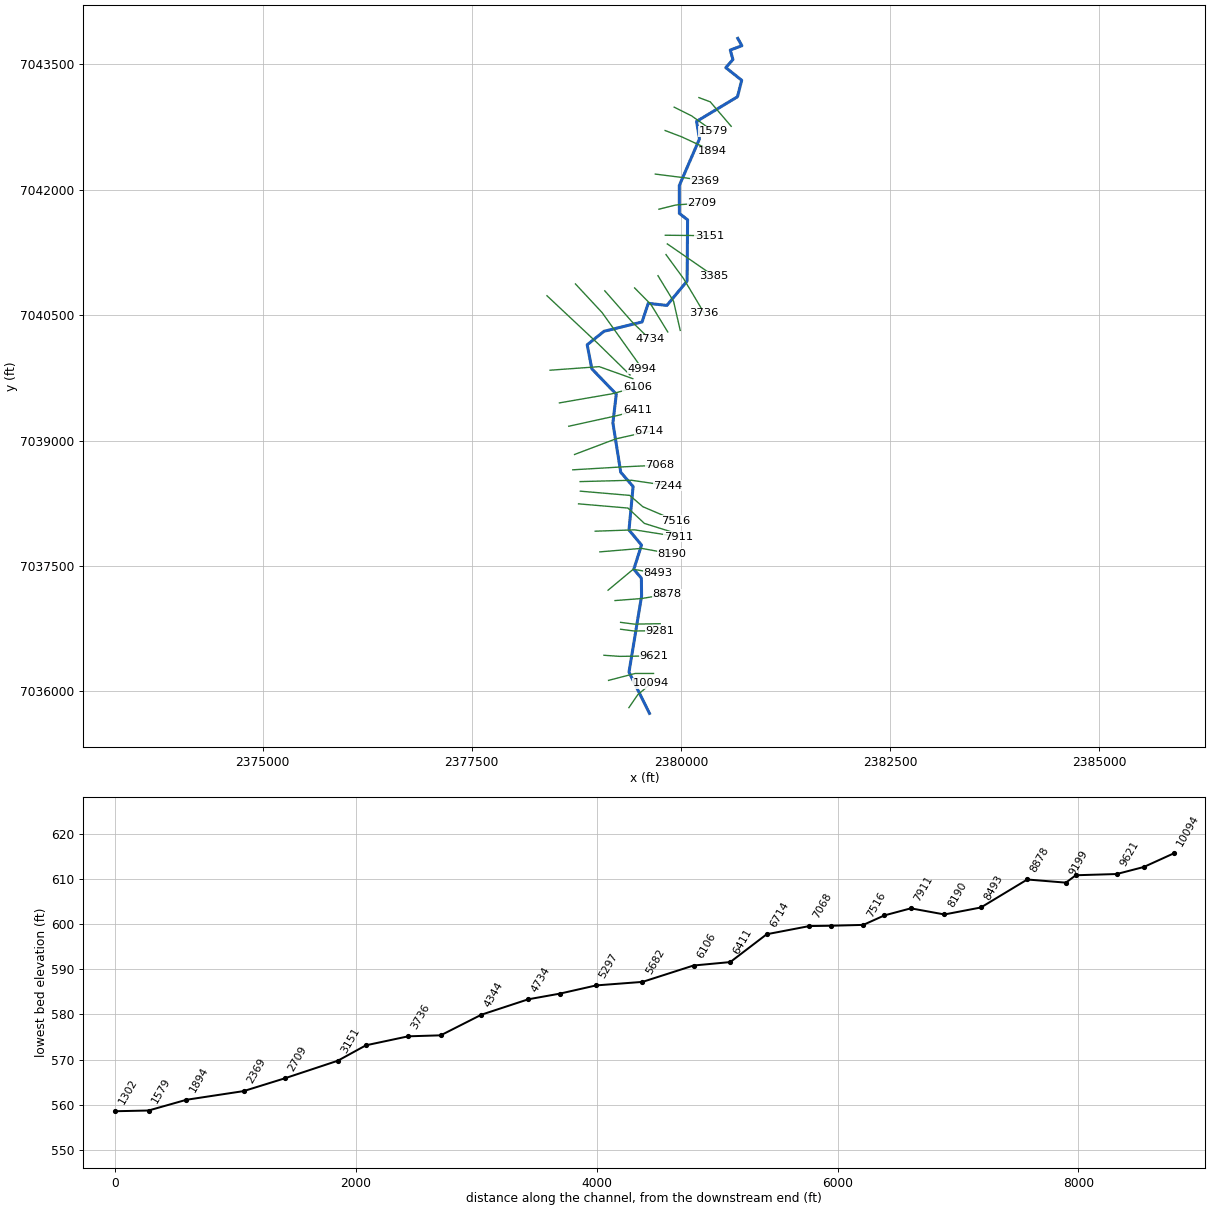
--- South Fork Kirkwood Br.prj (project) ---

Proj Title=South Fork Kirkwood Br Base Level Engineering
Current Plan=p01
Default Exp/Contr=0.3,0.1
English Units
Geom File=g01
Flow File=f01
Plan File=p01
Y Axis Title=Elevation
X Axis Title(PF)=Main Channel Distance
X Axis Title(XS)=Station
BEGIN DESCRIPTION:
South Fork Kirkwood Br
END DESCRIPTION:
DSS Export Rating Curves= 0
DSS Export Rating Curve Sorted= 0
DSS Export Volume Flow Curves= 0
DXF OffsetX= 0
DXF OffsetY= 0
DXF ScaleX= 1
DXF ScaleY= 10

--- South Fork Kirkwood Br.p01 (plan) ---

Plan Title=Multiple Run
Program Version=4.10
Short Identifier=Multiple
Geom File=g01
Flow File=f01
Subcritical Flow
K Sum by GR= 0
Std Step Tol= 0.01
Critical Tol= 0.01
Num of Std Step Trials= 20
Max Error Tol= 0.3
Flow Tol Ratio= 0.001
Split Flow NTrial= 30
Split Flow Tol= 0.02
Split Flow Ratio= 0.02
Log Output Level= 0
Friction Slope Method= 1
Unsteady Friction Slope Method= 2
Unsteady Bridges Friction Slope Method= 1
Parabolic Critical Depth
Global Vel Dist= 1 , 1 , 1
Global Log Level= 0
CheckData=True
Encroach Param=-1 ,0,0, 0
BEGIN DESCRIPTION:
Multiple Run
END DESCRIPTION:
Computation Interval=1HOUR
Output Interval=1HOUR
Run HTab= 0
Run UNet= 0
Run PostProcess= 0
Run WQNet= 0
UNET Theta= 1
UNET Theta Warmup= 1
UNET ZTol= 0.02
UNET ZSATol= 0.05
UNET MxIter= 20
UNET MaxInSteps= 0
UNET DtIC= 0
UNET DtMin= 0
UNET MaxCRTS= 20
UNET WFStab= 2
UNET SFStab= 1
UNET WFX= 1
UNET SFX= 1
UNET DSS MLevel= 4
UNET DZMax Abort= 100
UNET Convert EG Bridges= 0
UNET Use Existing IB Tables=-1
UNET Froude Reduction=False
UNET Froude Limit= 1
UNET Froude Power= 10
UNET Time Slicing=0,0, 5
UNET Junction Losses=0
Instantaneous Interval=1HOUR
Write IC File= 0
Write IC File at Sim End=0
Echo Input=False
Echo Parameters=False
Echo Output=False
Write Detailed= 0
WQ AD Non Conservative
WQ ULTIMATE=-1
WQ Max Comp Step=1HOUR
WQ Output Interval=15MIN
WQ Output Selected Increments= 0
WQ Output face flow=0
WQ Output face velocity=0
WQ Output face area=0
WQ Output face dispersion=0
WQ Output cell volume=0
WQ Output cell surface area=0
WQ Output cell continuity=0
WQ Output cumulative cell continuity=0
WQ Output face conc=0
WQ Output face dconc_dx=0
WQ Output face courant=0
WQ Output face peclet=0
WQ Output face adv mass=0
WQ Output face disp mass=0
WQ Output cell mass=0
WQ Output cell source sink temp=0
WQ Output cell source sink nsm=0
WQ Output MaxMinRange=-1
WQ Daily Max Min Mean=-1
WQ Daily Range=0
WQ Daily Time=0
WQ Create Restart=0
WQ Fixed Restart=0
WQ System Summary=0
WQ Use Fixed Temperature=0
Sorting and Armoring Iterations= 10
XS Update Threshold= 0.02
Hydraulics Update Threshold= 0.02
Energy Slope Method= 1
Volume Change Method= 0
XS Weighting Method= 0
Number of US Weighted Cross Sections= 1
Number of DS Weighted Cross Sections= 1
Upstream XS Weight=0.25
Main XS Weight=0.5
Downstream XS Weight=0.25
Number of DS XS's Weighted with US Boundary= 1
Upstream Boundary Weight= 1
Weight of XSs Associated with US Boundary= 0
Number of US XS's Weighted with DS Boundary= 1
Downstream Boundary Weight= 0.5
Weight of XSs Associated with DS Boundary= 0.5
Sediment Output Level= 4
Mass or Volume Output= 0
Output Increment Type= 1
Profile and TS Output Increment= 10
XS Output Flag= 0
XS Output Increment= 10
Disregard all LS=0
Disregard all Conn=0
Disregard all Breaches=0
Disregard all Pumps=0

--- South Fork Kirkwood Br.f01 (steady flow) ---

Flow Title=Multiple
Number of Profiles=7
Profile Names=10-year,25-year,50-year,1pct_min,100-year,1pct_plu,500-year
River Rch & RM= South Fork Kirkw,Reach-1,10094
     633     865    1054     637    1272    2537    1850
River Rch & RM= South Fork Kirkw,Reach-1,7244
     816    1125    1382     841    1677    3347    2470
River Rch & RM= South Fork Kirkw,Reach-1,4006
    1020    1424    1763    1080    2156    4302    3223
Boundary for River Rch & Prof#=South Fork Kirkw,Reach-1,1
Up Type=0
Dn Type=3
Dn Slope=0.005
Boundary for River Rch & Prof#=South Fork Kirkw,Reach-1,2
Up Type=0
Dn Type=3
Dn Slope=0.005
Boundary for River Rch & Prof#=South Fork Kirkw,Reach-1,3
Up Type=0
Dn Type=3
Dn Slope=0.005
Boundary for River Rch & Prof#=South Fork Kirkw,Reach-1,4
Up Type=0
Dn Type=3
Dn Slope=0.005
Boundary for River Rch & Prof#=South Fork Kirkw,Reach-1,5
Up Type=0
Dn Type=3
Dn Slope=0.005
Boundary for River Rch & Prof#=South Fork Kirkw,Reach-1,6
Up Type=0
Dn Type=3
Dn Slope=0.005
Boundary for River Rch & Prof#=South Fork Kirkw,Reach-1,7
Up Type=0
Dn Type=3
Dn Slope=0.005

--- South Fork Kirkwood Br.g01 (geometry) ---

Geom Title=Existing Conditions
Program Version=4.10

River Reach=South Fork Kirkw,Reach-1
Reach XY= 30
      2379623.75      7035736.66      2379378.96      7036229.98
      2379529.36      7037139.85      2379526.93      7037354.15
      2379436.55        7037460.      2379528.41      7037749.38
      2379378.94      7037929.99        2379428.      7038449.71
      2379280.19      7038620.48      2379186.59      7039210.01
      2379226.95      7039554.14      2378934.83       7039857.7
      2378879.38      7040144.85      2379080.55      7040306.25
      2379535.43      7040418.02      2379608.88      7040640.71
      2379831.68      7040615.39      2380073.53      7040907.55
       2380079.3      7041639.66      2379981.01      7041715.68
      2379980.19      7042049.52      2380221.19      7042606.59
       2380186.8      7042816.21      2380675.49      7043111.25
      2380725.88      7043308.38      2380536.01      7043459.79
      2380621.15      7043556.59      2380589.06      7043670.05
      2380728.11      7043721.51        2380679.        7043810.

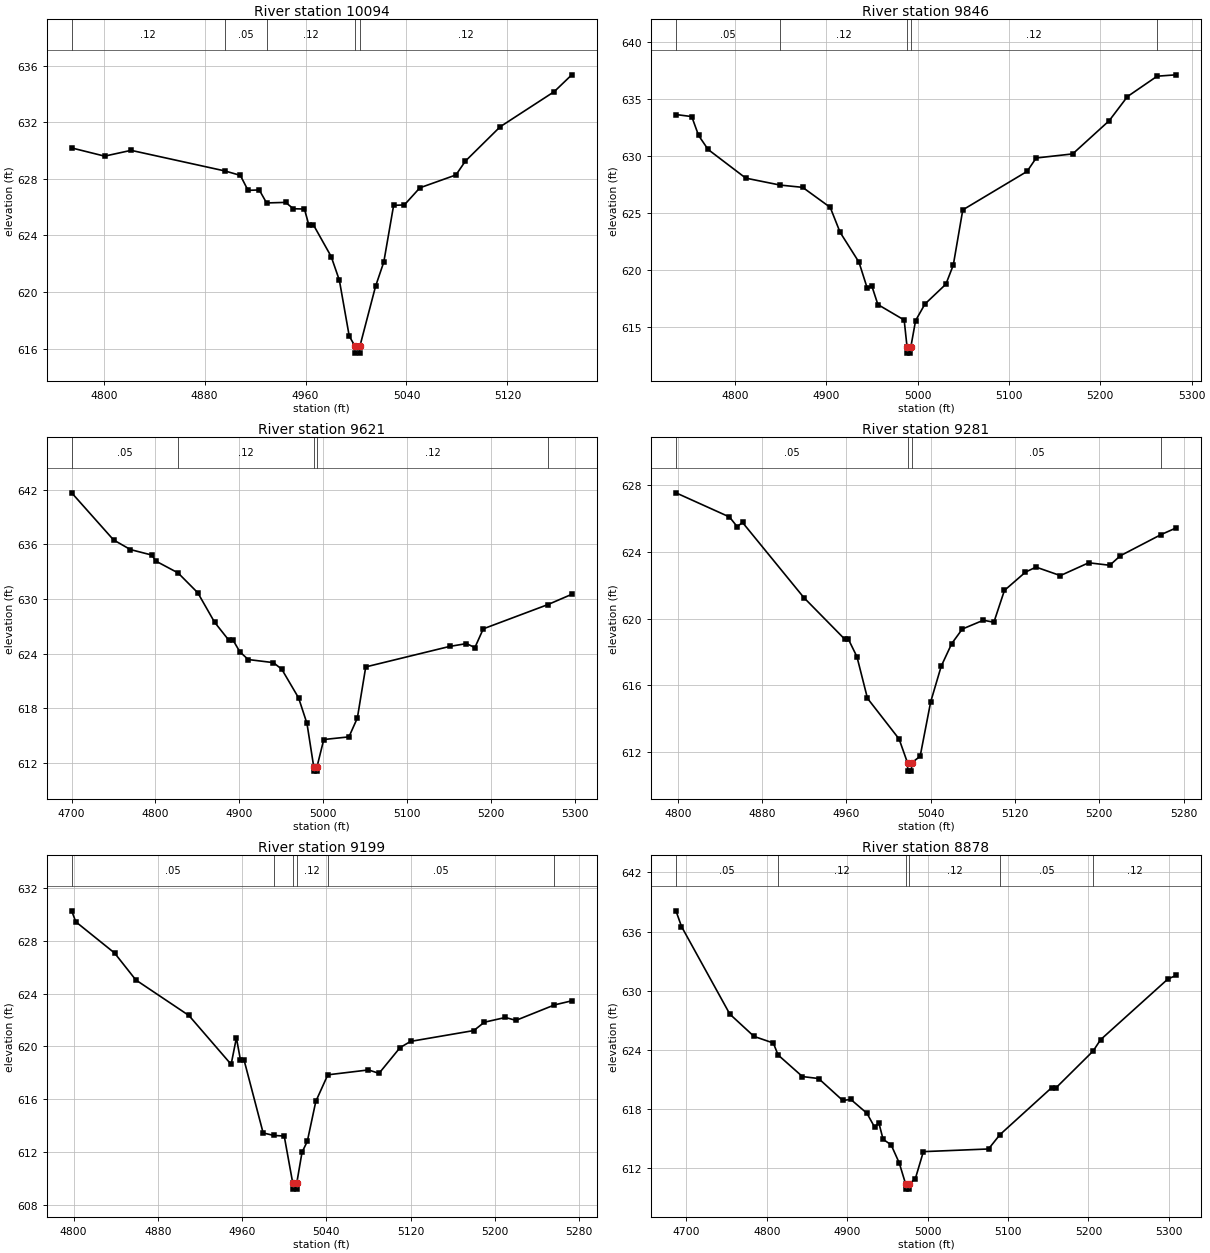
Type RM Length L Ch R = 1 ,10094   ,248,248,248
BEGIN DESCRIPTION:
South Fork Kirkwood Br 25.0
END DESCRIPTION:
XS GIS Cut Line= 4
      2379377.93       7035805.4      2379484.17       7035960.6
      2379540.42      7036007.47      2379642.93      7036095.48
#Sta/Elev= 30
  4774.6  630.19  4800.7  629.61  4821.7  630.02  4896.2  628.56  4908.3  628.25
  4914.4  627.19  4923.3  627.22  4929.1   626.3  4944.2  626.34  4950.3  625.89
  4959.1  625.87  4962.5  624.77  4966.1  624.77  4980.3  622.51  4986.8  620.83
  4994.6  616.89  4999.1  616.18  4999.4  615.68  5002.9  615.68  5003.1  616.18
  5015.5  620.41    5022  622.12  5029.8  626.13  5038.3  626.16  5050.6  627.37
  5079.2  628.28  5086.7  629.26  5114.3  631.69  5157.1  634.17    5171  635.36
#Mann= 5 ,-1 , 0
  4774.6     .12       0  4896.2     .05       0  4929.1     .12       0
  4999.1     .07       0  5003.1     .12       0
Bank Sta=4999.1,5003.1
XS Rating Curve= 0 ,0
Exp/Cntr=0.3,0.1

Type RM Length L Ch R = 1 ,9846    ,225,225,225
BEGIN DESCRIPTION:
South Fork Kirkwood Br 24.0
END DESCRIPTION:
XS GIS Cut Line= 3
      2379134.96      7036131.23      2379451.44      7036213.68
       2379672.2      7036213.68
#Sta/Elev= 30
  4735.1  633.64  4752.4  633.46  4759.9   631.8  4770.3  630.57  4811.6  628.05
  4849.2  627.44  4873.9  627.24  4904.1  625.48  4914.9  623.29  4935.6  620.66
  4944.6  618.39  4949.8  618.54  4956.3  616.94  4985.1  615.58  4988.3  613.17
  4988.5  612.67    4992  612.67  4992.3  613.17  4997.6  615.53  5007.9  616.99
  5030.8  618.73  5038.9  620.41  5049.3  625.26  5119.7  628.64  5129.7  629.82
  5169.7  630.18  5209.7   633.1  5229.7  635.22  5262.2  637.01  5282.9  637.13
#Mann= 5 ,-1 , 0
  4735.1     .05       0  4849.2     .12       0  4988.3     .07       0
  4992.3     .12       0  5262.2     .05       0
Bank Sta=4988.3,4992.3
XS Rating Curve= 0 ,0
Exp/Cntr=0.3,0.1

Type RM Length L Ch R = 1 ,9621    ,340,340,340
BEGIN DESCRIPTION:
South Fork Kirkwood Br 23.0
END DESCRIPTION:
XS GIS Cut Line= 3
      2379079.19      7036431.73      2379267.96      7036418.44
      2379674.39      7036423.75
#Sta/Elev= 30
  4700.2  641.66  4750.1  636.49  4770.2  635.43  4795.6  634.83  4800.6  634.16
  4826.9  632.87  4850.4  630.69  4870.4  627.46  4887.4  625.48  4892.5  625.48
  4900.5  624.21  4910.5  623.36  4940.5  623.02  4950.5  622.29  4970.5  619.15
  4980.5  616.34  4988.5  611.61  4988.7  611.11  4992.2  611.11  4992.5  611.61
  5000.5  614.58  5030.5  614.87  5040.5  616.94  5050.5  622.55  5150.5   624.8
  5170.5  625.11  5180.5  624.67  5190.5  626.73  5267.7   629.4  5295.9  630.52
#Mann= 5 ,-1 , 0
  4700.2     .05       0  4826.9     .12       0  4988.5     .07       0
  4992.5     .12       0  5267.7     .05       0
Bank Sta=4988.5,4992.5
XS Rating Curve= 0 ,0
Exp/Cntr=0.3,0.1

Type RM Length L Ch R = 1 ,9281    ,82,82,82
BEGIN DESCRIPTION:
South Fork Kirkwood Br 22.2
END DESCRIPTION:
XS GIS Cut Line= 3
      2379278.63      7036742.86      2379440.81      7036721.59
       2379751.9      7036726.91
#Sta/Elev= 30
  4798.2  627.55    4849   626.1  4856.3  625.52  4861.4  625.77  4919.6  621.26
  4958.3  618.77  4961.8  618.77    4970  617.71    4980  615.21    5010  612.77
    5018  611.34  5018.2  610.84  5021.7  610.84    5022  611.34    5030  611.73
    5040     615    5050  617.14    5060   618.5    5070  619.37    5090   619.9
    5100  619.78    5110  621.69    5130  622.79    5140  623.09  5163.1  622.58
    5190  623.35    5210   623.2    5220  623.77  5258.6  625.04  5272.9  625.44
#Mann= 4 ,-1 , 0
  4798.2     .05       0    5018     .05       0    5022     .05       0
  5258.6     .12       0
Bank Sta=5018,5022
XS Rating Curve= 0 ,0
Exp/Cntr=0.3,0.1

Type RM Length L Ch R = 1 ,9199    ,321,321,321
BEGIN DESCRIPTION:
South Fork Kirkwood Br 22.0
END DESCRIPTION:
XS GIS Cut Line= 3
       2379278.6       7036825.3      2379440.81      7036804.03
      2379751.97      7036809.35
#Sta/Elev= 30
  4798.2  630.26  4802.1  629.43  4838.9  627.07  4859.1  625.03  4909.5  622.34
  4949.6  618.64  4954.6  620.65  4958.4  618.99  4961.8  618.99    4980  613.45
  4990.3  613.26    5000  613.22    5008   609.7  5008.2   609.2  5011.7   609.2
    5012   609.7  5016.9  611.99  5021.9  612.81    5030  615.84  5041.4  617.85
    5080  618.22    5090  617.96    5110  619.91    5120  620.38    5180   621.2
    5190  621.83    5210  622.19    5220  621.97  5256.6  623.14    5273  623.45
#Mann= 6 ,-1 , 0
  4798.2     .05       0  4990.3     .12       0    5008     .07       0
    5012     .12       0  5041.4     .05       0  5256.6     .12       0
Bank Sta=5008,5012
XS Rating Curve= 0 ,0
Exp/Cntr=0.3,0.1

Type RM Length L Ch R = 1 ,8878    ,385,385,385
BEGIN DESCRIPTION:
South Fork Kirkwood Br 21.0
END DESCRIPTION:
XS GIS Cut Line= 3
      2379212.15      7037085.91        2379529.        7037110.
        2379829.        7037160.
#Sta/Elev= 30
    4687  638.11  4693.9  636.52    4754  627.64  4784.1  625.38  4808.1  624.71
    4814   623.5  4844.3  621.31  4864.4  621.11  4894.4  618.89  4904.5  618.99
  4924.5  617.59  4934.2  616.16  4939.2  616.65  4944.6  614.95  4954.6  614.39
  4964.7  612.55  4972.7   610.4  4972.9   609.9  4976.4   609.9  4976.7   610.4
  4984.7  610.96  4994.7   613.7  5075.7  613.97  5089.9  615.42  5154.3  620.19
  5159.4  620.15  5205.7  623.89  5215.1  625.05  5298.8   631.2  5308.9  631.56
#Mann= 6 ,-1 , 0
    4687     .05       0    4814     .12       0  4972.7     .07       0
  4976.7     .12       0  5089.9     .05       0  5205.7     .12       0
Bank Sta=4972.7,4976.7
XS Rating Curve= 0 ,0
Exp/Cntr=0.3,0.1

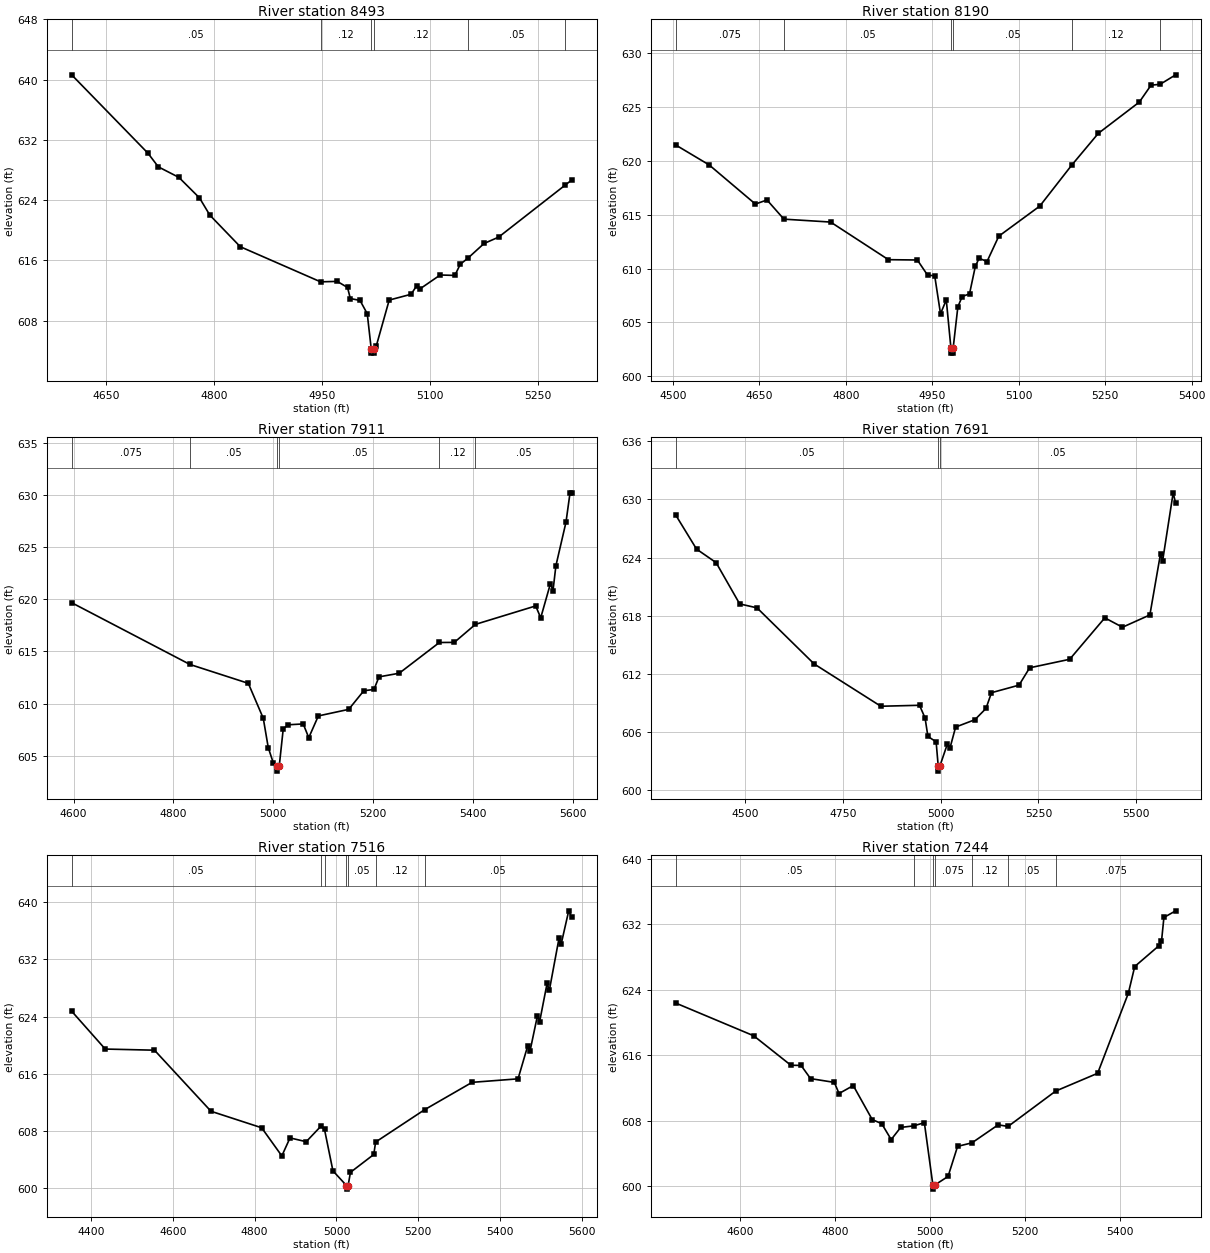
Type RM Length L Ch R = 1 ,8493    ,303,303,303
BEGIN DESCRIPTION:
South Fork Kirkwood Br 20.0
END DESCRIPTION:
XS GIS Cut Line= 3
      2379129.03      7037210.03        2379429.        7037460.
      2379728.99        7037410.
#Sta/Elev= 30
  4601.7  640.63  4707.7  630.23  4722.1  628.42  4750.7  627.02  4779.3   624.3
  4793.7  622.01    4836  617.82  4947.6  613.16  4970.7  613.22    4985  612.41
  4988.9  610.94  5002.3   610.7  5012.4  608.93    5018   604.2  5018.3   603.7
  5021.8   603.7    5022   604.2  5025.1   604.7  5042.9  610.74  5073.3  611.51
  5080.9  612.61  5085.9  612.24  5113.8  614.07  5134.1  614.01  5141.7   615.5
  5151.9  616.27  5174.7  618.25  5194.9  619.09  5287.6  626.01  5296.3  626.66
#Mann= 6 ,-1 , 0
  4601.7     .05       0  4947.6     .12       0    5018     .07       0
    5022     .12       0  5151.9     .05       0  5287.6     .12       0
Bank Sta=5018,5022
XS Rating Curve= 0 ,0
Exp/Cntr=0.3,0.1

Type RM Length L Ch R = 1 ,8190    ,279,279,279
BEGIN DESCRIPTION:
South Fork Kirkwood Br 19.0
END DESCRIPTION:
XS GIS Cut Line= 3
      2379031.25      7037668.28        2379529.        7037710.
      2379891.05      7037644.68
#Sta/Elev= 30
  4504.9  621.46  4562.9  619.61  4643.1  615.98  4663.2  616.36  4692.6  614.58
  4773.6  614.31  4873.9  610.82  4924.1  610.79  4941.9  609.38  4954.2  609.33
  4964.3   605.8  4974.3  607.09  4982.3  602.65  4982.6  602.15  4986.1  602.15
  4986.3  602.65  4994.4  606.45  5001.9   607.4  5014.6  607.65  5024.7   610.2
  5031.2  610.95    5045  610.65  5065.4     613  5136.5  615.79  5192.1   619.6
  5238.1  622.54  5309.2  625.44  5329.6  627.01  5345.3  627.09  5372.3  627.97
#Mann= 6 ,-1 , 0
  4504.9    .075       0  4692.6     .05       0  4982.3    .033       0
  4986.3     .05       0  5192.1     .12       0  5345.3     .05       0
Bank Sta=4982.3,4986.3
XS Rating Curve= 0 ,0
Exp/Cntr=0.3,0.1

Type RM Length L Ch R = 1 ,7911    ,220,220,220
BEGIN DESCRIPTION:
South Fork Kirkwood Br 18.0
END DESCRIPTION:
XS GIS Cut Line= 3
      2378975.43      7037915.59      2379446.12      7037931.55
      2379970.02      7037849.11
#Sta/Elev= 30
  4596.2  619.68  4833.2  613.75    4950  611.94    4980  608.58    4990  605.76
    5000  604.31    5008  604.01  5008.3  603.51    5012  604.01    5020  607.58
    5030  607.96    5060  608.04  5071.1  606.72  5090.3  608.81  5151.1  609.44
  5181.4  611.23  5201.7  611.35  5211.8  612.56  5252.3  612.91  5332.7  615.86
  5362.6  615.87  5404.9   617.6  5525.6  619.37  5535.7  618.23  5555.2  621.52
  5560.3  620.84  5566.1  623.23  5586.3  627.41  5594.4  630.23  5597.5  630.23
#Mann= 6 ,-1 , 0
  4596.2    .075       0  4833.2     .05       0    5008    .033       0
    5012     .05       0  5332.7     .12       0  5404.9     .05       0
Bank Sta=5008,5012
XS Rating Curve= 0 ,0
Exp/Cntr=0.3,0.1

Type RM Length L Ch R = 1 ,7691    ,175,175,175
BEGIN DESCRIPTION:
South Fork Kirkwood Br 17.4
END DESCRIPTION:
XS GIS Cut Line= 4
      2378776.04      7038242.67      2379366.35      7038192.15
      2379563.13      7038008.66      2379961.99      7037883.69
#Sta/Elev= 30
  4321.7  628.38  4374.9  624.87    4425  623.47  4485.3  619.21  4529.7   618.8
  4675.9  613.01  4846.6  608.64  4945.6  608.74  4959.8  607.43  4967.1  605.52
  4988.1  604.97  4993.5  602.44  4993.7  601.94  4997.5  602.44  5016.5  604.69
  5023.8  604.36    5038  606.49  5087.3  607.25  5115.7  608.41  5129.8  610.04
  5200.3  610.82  5227.5  612.61    5330  613.49  5419.9  617.77  5465.1   616.8
  5535.2  618.07  5562.4  624.39  5567.6   623.6  5594.8  630.68  5601.2  629.59
#Mann= 3 ,-1 , 0
  4321.7     .05       0  4993.5    .033       0  4997.5     .05       0
Bank Sta=4993.5,4997.5
XS Rating Curve= 0 ,0
Exp/Cntr=0.3,0.1

Type RM Length L Ch R = 1 ,7516    ,272,272,272
BEGIN DESCRIPTION:
South Fork Kirkwood Br 17.2
END DESCRIPTION:
XS GIS Cut Line= 4
       2378797.3      7038394.25      2379387.62      7038343.73
      2379544.52      7038208.11      2379932.79      7038043.22
#Sta/Elev= 30
  4352.8  624.75  4434.8  619.45  4555.2  619.29  4693.3  610.74  4817.1  608.43
  4866.4  604.49  4886.4  607.01    4926  606.48  4961.8  608.64  4970.7   608.2
  4991.3   602.4  5024.4  600.34  5024.7  599.84  5028.4  600.34  5034.1  602.19
  5091.1  604.69  5095.6  606.43  5215.1  610.95  5331.4  614.79  5443.7  615.28
  5467.4  619.91  5472.8  619.13  5491.1  624.12  5496.5   623.3  5514.7  628.66
  5520.1  627.65  5543.8  634.96  5549.2  634.18  5567.5   638.8  5574.5  637.92
#Mann= 7 ,-1 , 0
  4352.8     .05       0  4961.8     .12       0  4970.7     .05       0
  5024.4     .05       0  5028.4     .05       0  5095.6     .12       0
  5215.1     .05       0
Bank Sta=5024.4,5028.4
XS Rating Curve= 0 ,0
Exp/Cntr=0.3,0.1

Type RM Length L Ch R = 1 ,7244    ,176,176,176
BEGIN DESCRIPTION:
South Fork Kirkwood Br 17.0
END DESCRIPTION:
XS GIS Cut Line= 3
      2378794.65       7038508.6       2379408.9      7038524.56
       2379844.5      7038460.81
#Sta/Elev= 30
  4463.5  622.36  4627.9  618.37  4706.4  614.77  4727.9  614.75  4747.9  613.14
    4798  612.68    4808  611.32    4838  612.29    4878  608.14    4898  607.64
    4918   605.7    4938  607.18  4965.3  607.37    4988  607.76    5006  600.15
  5006.3  599.65    5010  600.15    5038   601.2  5058.1  604.87  5088.4   605.3
  5143.8   607.5  5164.6   607.3  5265.1  611.62  5353.6  613.79  5418.4  623.57
  5431.8  626.82  5482.3  629.33  5488.3  629.88  5493.4  632.81  5518.2  633.62
#Mann= 7 ,-1 , 0
  4463.5     .05       0  4965.3    .075       0    5006     .07       0
    5010    .075       0  5088.4     .12       0  5164.6     .05       0
  5265.1    .075       0
Bank Sta=5006,5010
XS Rating Curve= 0 ,0
Exp/Cntr=0.3,0.1

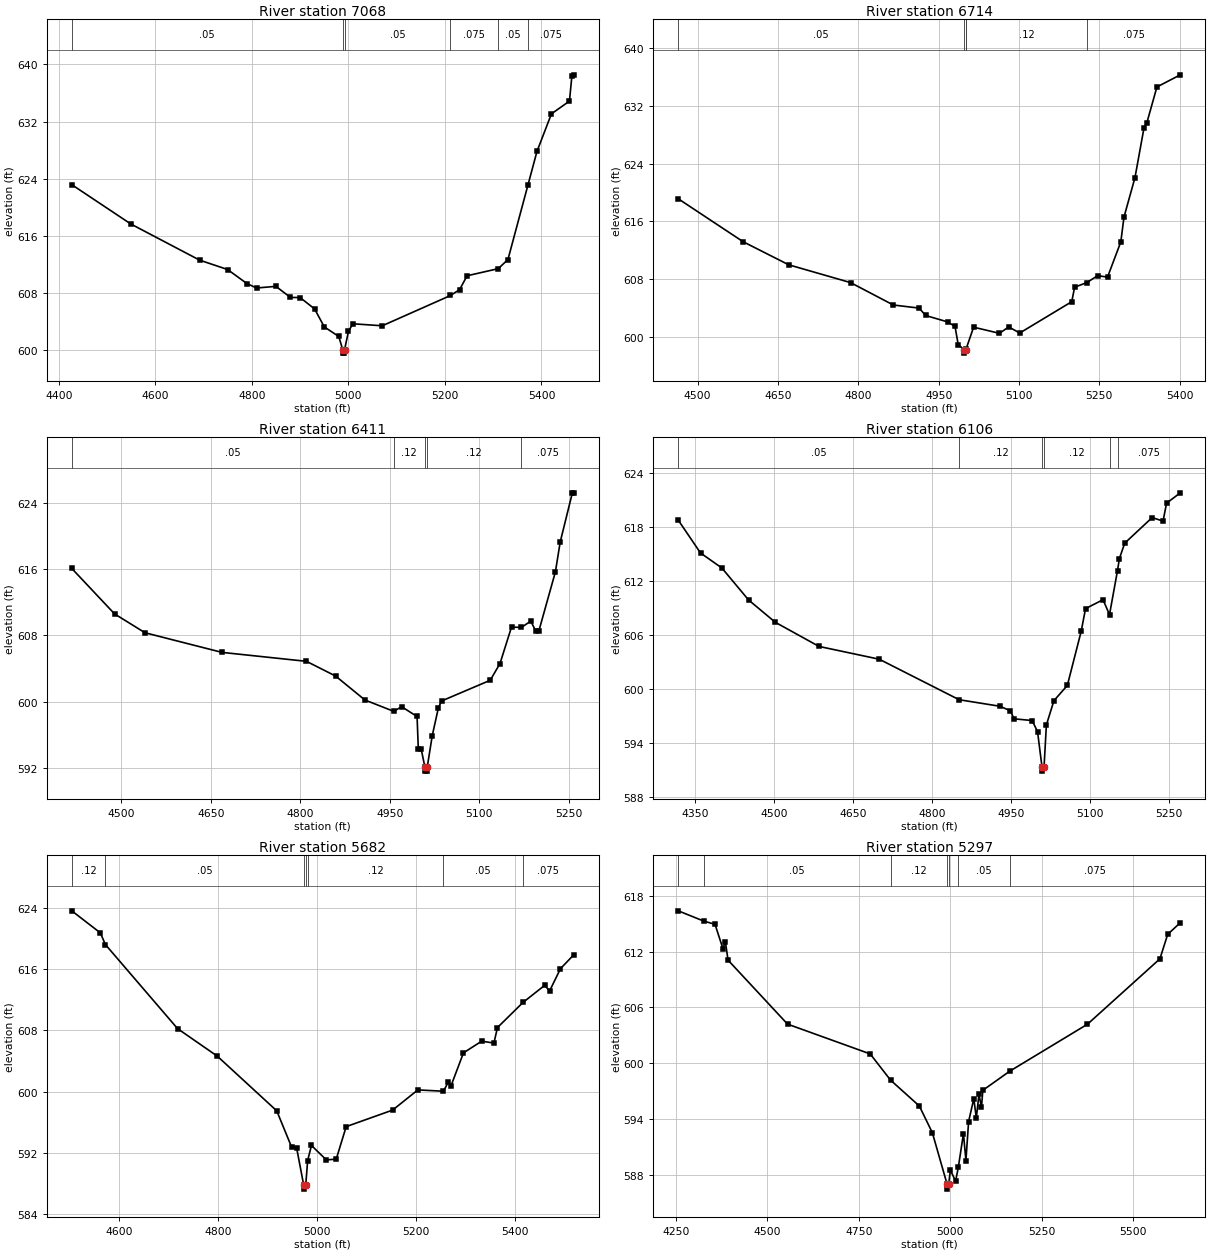
Type RM Length L Ch R = 1 ,7068    ,354,354,354
BEGIN DESCRIPTION:
South Fork Kirkwood Br 16.0
END DESCRIPTION:
XS GIS Cut Line= 3
      2378706.85      7038649.54      2379291.89      7038684.11
      2379745.34      7038705.32
#Sta/Elev= 30
  4427.1  623.17  4549.5  617.66    4692   612.6  4749.8  611.29  4789.9  609.32
  4809.9   608.7    4850  608.93    4880  607.38  4900.1  607.36  4930.1  605.77
  4950.2  603.25  4980.2  601.91  4988.2  600.08  4988.5  599.58    4992  599.58
  4992.2  600.08  5000.2  602.61  5009.2  603.69  5070.3  603.41  5211.6  607.65
  5230.5  608.47  5245.9  610.41  5310.6  611.41  5330.6  612.69  5371.8  623.06
  5390.7  627.82  5420.7  633.09    5458  634.87    5463  638.36  5467.1  638.55
#Mann= 6 ,-1 , 0
  4427.1     .05       0  4988.2    .033       0  4992.2     .05       0
  5211.6    .075       0  5310.6     .05       0  5371.8    .075       0
Bank Sta=4988.2,4992.2
XS Rating Curve= 0 ,0
Exp/Cntr=0.3,0.1

Type RM Length L Ch R = 1 ,6714    ,303,303,303
BEGIN DESCRIPTION:
South Fork Kirkwood Br 15.0
END DESCRIPTION:
XS GIS Cut Line= 3
      2378728.09      7038833.01      2379220.09      7039019.17
      2379621.59      7039109.58
#Sta/Elev= 30
  4463.7  619.13    4585  613.18  4670.1  609.99  4785.5  607.53  4865.3  604.43
  4913.7     604  4925.6  602.98  4967.2  602.08  4980.6  601.46  4986.5  598.96
  4996.9  598.27  4997.1  597.77  5000.9  598.27    5001  598.29  5015.3  601.36
  5063.6  600.51  5080.9   601.4  5101.4  600.55  5198.6  604.89  5203.9  606.89
  5226.7  607.53  5246.9  608.49  5265.4  608.29  5290.2  613.17  5296.1  616.59
  5316.6  622.05  5333.5  628.94  5338.6  629.58  5357.6   634.6  5401.3  636.28
#Mann= 5 ,-1 , 0
  4463.7     .05       0  4996.9    .033       0  5000.9     .05       0
    5001     .12       0  5226.7    .075       0
Bank Sta=4996.9,5000.9
XS Rating Curve= 0 ,0
Exp/Cntr=0.3,0.1

Type RM Length L Ch R = 1 ,6411    ,305,305,305
BEGIN DESCRIPTION:
South Fork Kirkwood Br 14.0
END DESCRIPTION:
XS GIS Cut Line= 3
      2378659.01      7039170.76      2379228.07      7039295.74
      2379478.95      7039359.99
#Sta/Elev= 30
  4416.9  616.08  4488.6  610.59  4539.7  608.31  4668.7  605.94  4810.3  604.86
  4859.2  603.08  4908.3  600.19  4956.6  598.82  4969.8  599.38  4995.7   598.2
  4997.8  594.26  5002.6  594.26  5008.8   592.1  5009.1   591.6  5012.6   591.6
  5012.8   592.1  5021.1  595.87  5031.4  599.23  5036.7  600.07  5118.3  602.57
  5134.7  604.59    5154     609  5170.6  608.95  5186.3  609.72  5194.8  608.49
  5199.9  608.54  5227.6  615.67  5235.6  619.26    5256  625.21  5258.5  625.21
#Mann= 5 ,-1 , 0
  4416.9     .05       0  4956.6     .12       0  5008.8     .07       0
  5012.8     .12       0  5170.6    .075       0
Bank Sta=5008.8,5012.8
XS Rating Curve= 0 ,0
Exp/Cntr=0.3,0.1

Type RM Length L Ch R = 1 ,6106    ,424,424,424
BEGIN DESCRIPTION:
South Fork Kirkwood Br 13.0
END DESCRIPTION:
XS GIS Cut Line= 3
      2378547.34      7039449.98      2379177.54        7039559.
      2379480.67      7039641.43
#Sta/Elev= 30
  4318.2  618.72  4360.5  615.07  4401.1   613.4  4451.8  609.85  4502.6  607.37
  4585.6  604.69    4700  603.27  4851.8  598.77  4928.8  598.05  4949.1  597.55
    4956  596.65  4990.4  596.46  5000.7  595.23  5009.1  591.34  5009.3  590.84
  5013.1  591.34  5017.5  595.97  5031.8  598.66  5057.3  600.36  5083.6  606.37
  5091.9  608.89  5125.1  609.88  5137.4  608.22  5152.6  613.12  5156.2  614.45
  5166.3  616.16  5218.4     619  5239.1  618.61  5245.8   620.6  5271.9  621.75
#Mann= 6 ,-1 , 0
  4318.2     .05       0  4851.8     .12       0  5009.1     .07       0
  5013.1     .12       0  5137.4     .05       0  5152.6    .075       0
Bank Sta=5009.1,5013.1
XS Rating Curve= 0 ,0
Exp/Cntr=0.3,0.1

Type RM Length L Ch R = 1 ,5682    ,385,385,385
BEGIN DESCRIPTION:
South Fork Kirkwood Br 12.0
END DESCRIPTION:
XS GIS Cut Line= 3
      2378435.57      7039840.88      2379023.31      7039883.43
      2379424.45      7039739.97
#Sta/Elev= 30
  4504.6  623.68  4562.4  620.79  4572.6  619.26  4718.6  608.24  4798.8  604.64
  4919.1  597.47  4949.2  592.71  4959.2  592.65  4973.7  587.71    4974  587.21
  4977.7  587.71  4981.6  590.96  4989.3  592.93  5019.4  591.04  5039.4  591.14
  5059.5   595.4  5153.5  597.57  5204.4  600.21  5256.3  600.04    5266  601.25
  5271.3  600.71  5296.7  605.07  5333.6   606.6  5358.3  606.35  5365.4  608.38
    5417  611.67    5461  613.92  5470.8  613.17  5492.9   616.1  5519.9  617.93
#Mann= 7 ,-1 , 0
  4504.6     .12       0  4572.6     .05       0  4973.7     .07       0
  4977.7     .05       0  4981.6     .12       0  5256.3     .05       0
    5417    .075       0
Bank Sta=4973.7,4977.7
XS Rating Curve= 0 ,0
Exp/Cntr=0.3,0.1

Type RM Length L Ch R = 1 ,5297    ,303,303,303
BEGIN DESCRIPTION:
South Fork Kirkwood Br 11.3
END DESCRIPTION:
XS GIS Cut Line= 3
       2378398.4      7040731.72      2379007.35      7040159.99
       2379391.6      7039783.69
#Sta/Elev= 30
    4256   616.4  4326.1  615.29  4356.6  614.95  4378.1  612.34  4384.9  613.08
  4392.2  611.09  4554.9   604.2    4781  600.99  4836.6  598.17  4915.4  595.38
    4951   592.5  4991.5  586.93  4991.7  586.43  4995.5  586.93  5000.3  588.48
  5014.5  587.29  5021.9  588.76    5036   592.4  5042.8  589.51  5050.1   593.7
  5064.3  596.17  5071.2   594.1  5078.5  596.64  5085.3  595.23    5089  597.07
  5162.6  599.13  5375.2  604.19  5573.3  611.23  5594.6  613.87  5629.1  615.12
#Mann= 7 ,-1 , 0
    4256     .12       0  4326.1     .05       0  4836.6     .12       0
  4991.5     .07       0  4995.5     .12       0  5021.9     .05       0
  5162.6    .075       0
Bank Sta=4991.5,4995.5
XS Rating Curve= 0 ,0
Exp/Cntr=0.3,0.1

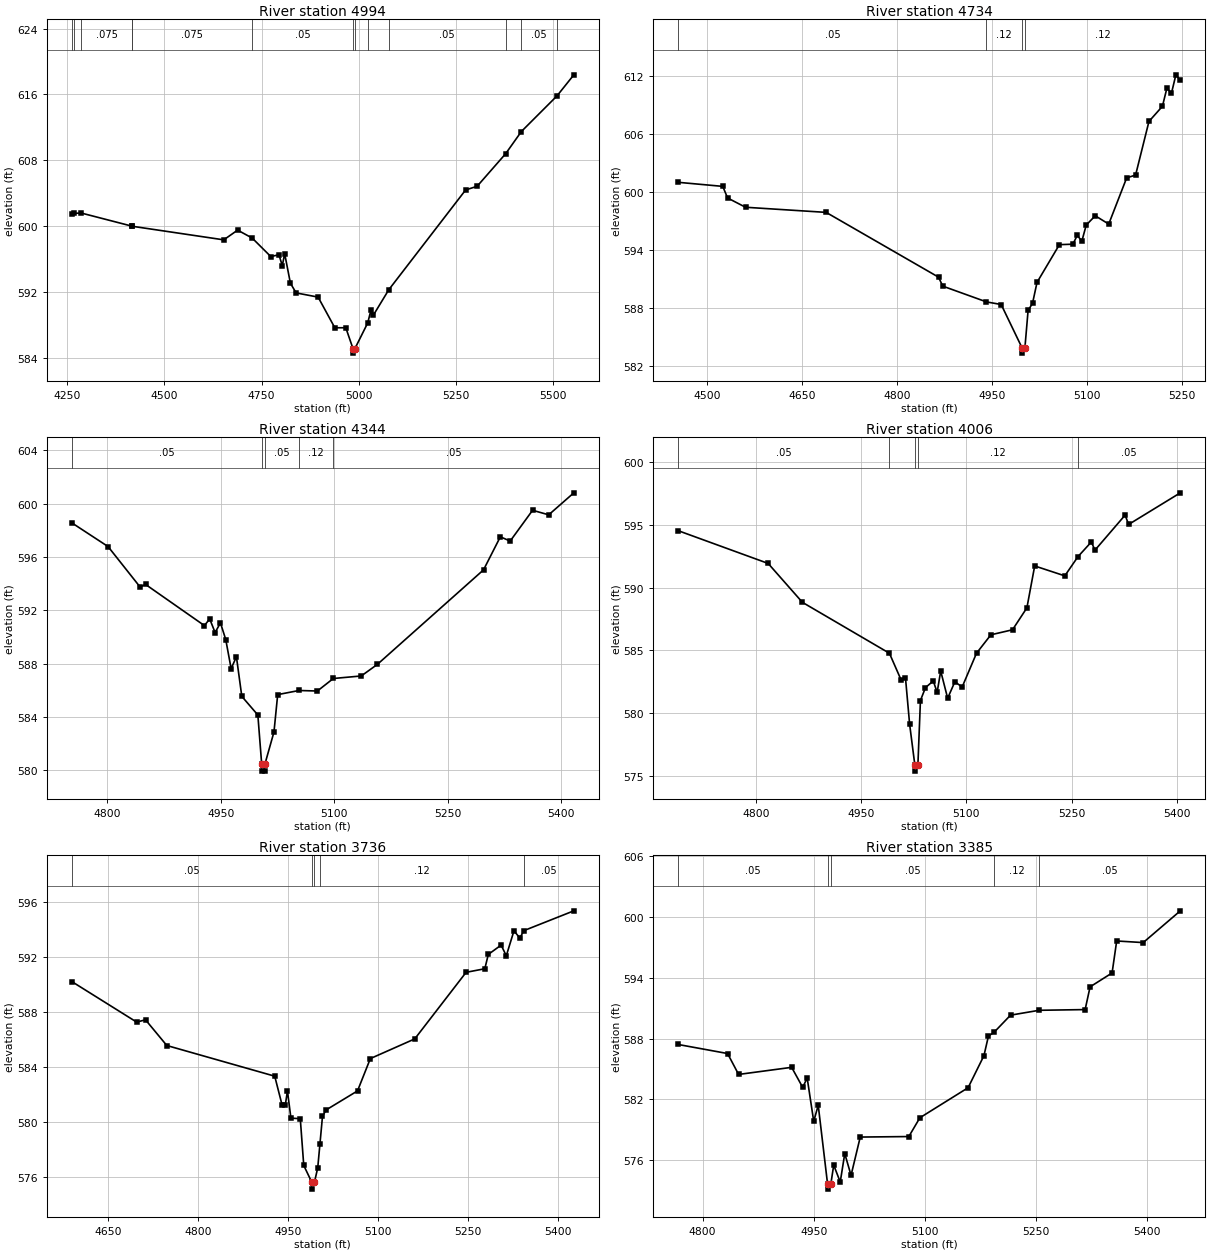
Type RM Length L Ch R = 1 ,4994    ,260,260,260
BEGIN DESCRIPTION:
South Fork Kirkwood Br 11.0
END DESCRIPTION:
XS GIS Cut Line= 3
       2378738.8      7040872.63      2379057.88      7040529.62
      2379536.54      7039859.49
#Sta/Elev= 30
  4261.6  601.54  4266.4  601.57  4286.3   601.6  4415.8  600.02  4416.9     600
  4652.7  598.35  4688.4  599.53  4725.8  598.57  4773.8  596.32  4794.7  596.54
  4803.3  595.23  4809.5  596.66  4824.2  593.09  4838.9  591.91  4895.5   591.4
  4938.5  587.68  4966.8  587.68  4985.6   585.1  4985.9   584.6  4989.7   585.1
  5023.2  588.27  5031.9  589.89    5038  589.23  5077.3  592.29  5275.2  604.41
  5304.7  604.85  5378.2  608.81  5418.6   611.5    5510  615.81  5553.6  618.38
#Mann= 13 ,-1 , 0
  4261.6    .075       0  4266.4     .05       0  4286.3    .075       0
  4415.8     .05       0  4416.9    .075       0  4725.8     .05       0
  4985.6     .05       0  4989.7     .05       0  5023.2    .075       0
  5077.3     .05       0  5378.2    .075       0  5418.6     .05       0
    5510    .075       0
Bank Sta=4985.6,4989.7
XS Rating Curve= 0 ,0
Exp/Cntr=0.3,0.1

Type RM Length L Ch R = 1 ,4734    ,390,390,390
BEGIN DESCRIPTION:
South Fork Kirkwood Br 10.0
END DESCRIPTION:
XS GIS Cut Line= 3
      2379089.77      7040790.25      2379414.21       7040420.6
      2379628.97      7040210.03
#Sta/Elev= 30
  4454.9  601.03  4525.2  600.61  4532.8  599.41  4561.2  598.45  4688.4  597.92
  4865.8  591.22  4872.5  590.29  4941.5  588.66  4964.7  588.39    4998  583.86
  4998.3  583.36  5002.1  583.86  5007.2  587.78  5014.2  588.51  5021.3  590.68
  5056.6  594.58  5077.9  594.63  5084.9  595.55    5092  594.93    5099  596.61
  5113.2  597.57  5134.5  596.71  5162.8  601.49  5176.9  601.78    5198  607.33
  5219.3   608.9  5226.3  610.77  5233.5  610.24  5240.5  612.15  5247.5  611.59
#Mann= 4 ,-1 , 0
  4454.9     .05       0  4941.5     .12       0    4998     .07       0
  5002.1     .12       0
Bank Sta=4998,5002.1
XS Rating Curve= 0 ,0
Exp/Cntr=0.3,0.1

Type RM Length L Ch R = 1 ,4344    ,338,338,338
BEGIN DESCRIPTION:
South Fork Kirkwood Br 9.0
END DESCRIPTION:
XS GIS Cut Line= 3
      2379446.12      7040824.81      2379640.25      7040628.02
      2379842.36      7040298.26
#Sta/Elev= 30
  4753.3  598.57  4801.2  596.79  4843.6  593.75  4850.7  593.95  4928.5  590.86
  4935.5  591.36  4942.6  590.34  4949.7  591.06  4956.7  589.81  4963.8  587.63
  4970.8  588.52  4977.9  585.55  4999.1  584.15  5004.2  580.44  5004.5  579.94
    5008  579.94  5008.3  580.44  5020.4  582.88  5025.3  585.68  5053.5  585.99
  5077.7  585.95  5098.8  586.89  5135.7  587.08    5157  587.95  5297.2  595.04
  5319.4  597.52  5332.4   597.2    5362  599.51  5383.3  599.17  5416.5  600.82
#Mann= 5 ,-1 , 0
  4753.3     .05       0  5004.2    .033       0  5008.3     .05       0
  5053.5     .12       0  5098.8     .05       0
Bank Sta=5004.2,5008.3
XS Rating Curve= 0 ,0
Exp/Cntr=0.3,0.1

Type RM Length L Ch R = 1 ,4006    ,270,270,270
BEGIN DESCRIPTION:
South Fork Kirkwood Br 8.0
END DESCRIPTION:
XS GIS Cut Line= 3
      2379725.33      7040971.08      2379911.49      7040665.25
      2379991.27       7040316.9
#Sta/Elev= 30
  4689.5  594.54  4817.6  591.93  4866.4  588.83  4990.4  584.77  5006.9  582.66
  5013.3  582.81  5019.2  579.11  5026.6  575.87    5027  575.37    5031  575.87
  5034.6     581  5041.8  582.03  5052.9  582.56  5058.4  581.65  5063.5  583.35
  5073.4  581.18  5083.7   582.5    5094  582.07  5114.5  584.77    5135  586.24
  5165.8  586.64  5186.3  588.39  5197.4  591.73  5240.3  590.94  5259.2  592.48
  5278.1  593.64  5283.3  592.99  5326.2  595.78  5331.3  595.04  5404.9  597.56
#Mann= 5 ,-1 , 0
  4689.5     .05       0  4990.4     .12       0  5026.6     .07       0
    5031     .12       0  5259.2     .05       0
Bank Sta=5026.6,5031
XS Rating Curve= 0 ,0
Exp/Cntr=0.3,0.1

Type RM Length L Ch R = 1 ,3736    ,351,351,351
BEGIN DESCRIPTION:
South Fork Kirkwood Br 7.6
END DESCRIPTION:
XS GIS Cut Line= 3
      2379821.07       7041223.7      2380031.16      7040936.49
      2380277.49      7040523.29
#Sta/Elev= 30
  4589.6  590.24  4697.8  587.29  4712.5  587.46    4748  585.59  4927.9  583.36
  4940.2  581.26  4945.5  581.26  4949.1  582.28  4954.9  580.31  4970.5  580.27
  4976.3  576.87  4989.7  575.65  4990.1  575.15  4994.1  575.65  4999.6   576.7
  5003.2   578.4  5007.5  580.43  5013.3   580.9  5065.9  582.29  5087.3  584.64
  5161.3  586.07  5246.9  590.91  5278.1  591.17  5283.9  592.21  5305.3  592.89
  5313.9  592.11  5326.7  593.93  5336.5   593.4  5343.2  593.94  5426.5  595.38
#Mann= 5 ,-1 , 0
  4589.6     .05       0  4989.7    .033       0  4994.1     .05       0
  5003.2     .12       0  5343.2     .05       0
Bank Sta=4989.7,4994.1
XS Rating Curve= 0 ,0
Exp/Cntr=0.3,0.1

Type RM Length L Ch R = 1 ,3385    ,234,234,234
BEGIN DESCRIPTION:
South Fork Kirkwood Br 7.4
END DESCRIPTION:
XS GIS Cut Line= 2
      2379837.02      7041351.34      2380394.78      7040966.22
#Sta/Elev= 30
  4767.1  587.41  4833.7  586.52  4848.6  584.46  4920.2  585.16  4935.1  583.19
  4941.2   584.1    4950  579.84  4956.1  581.42  4968.7  573.66  4969.1  573.16
  4973.1  573.66    4977  575.53  4985.8  573.86  4991.9  576.66  5000.4  574.52
  5012.8  578.29  5078.4  578.34  5093.3  580.19  5158.4  583.15  5179.8  586.31
  5185.9  588.25  5193.3   588.6  5215.7   590.3  5254.3  590.78  5316.4  590.85
  5323.1  593.09  5352.8  594.46    5359  597.61  5394.8  597.45  5444.9  600.58
#Mann= 5 ,-1 , 0
  4767.1     .05       0  4968.7     .05       0  4973.1     .05       0
  5193.3     .12       0  5254.3     .05       0
Bank Sta=4968.7,4973.1
XS Rating Curve= 0 ,0
Exp/Cntr=0.3,0.1

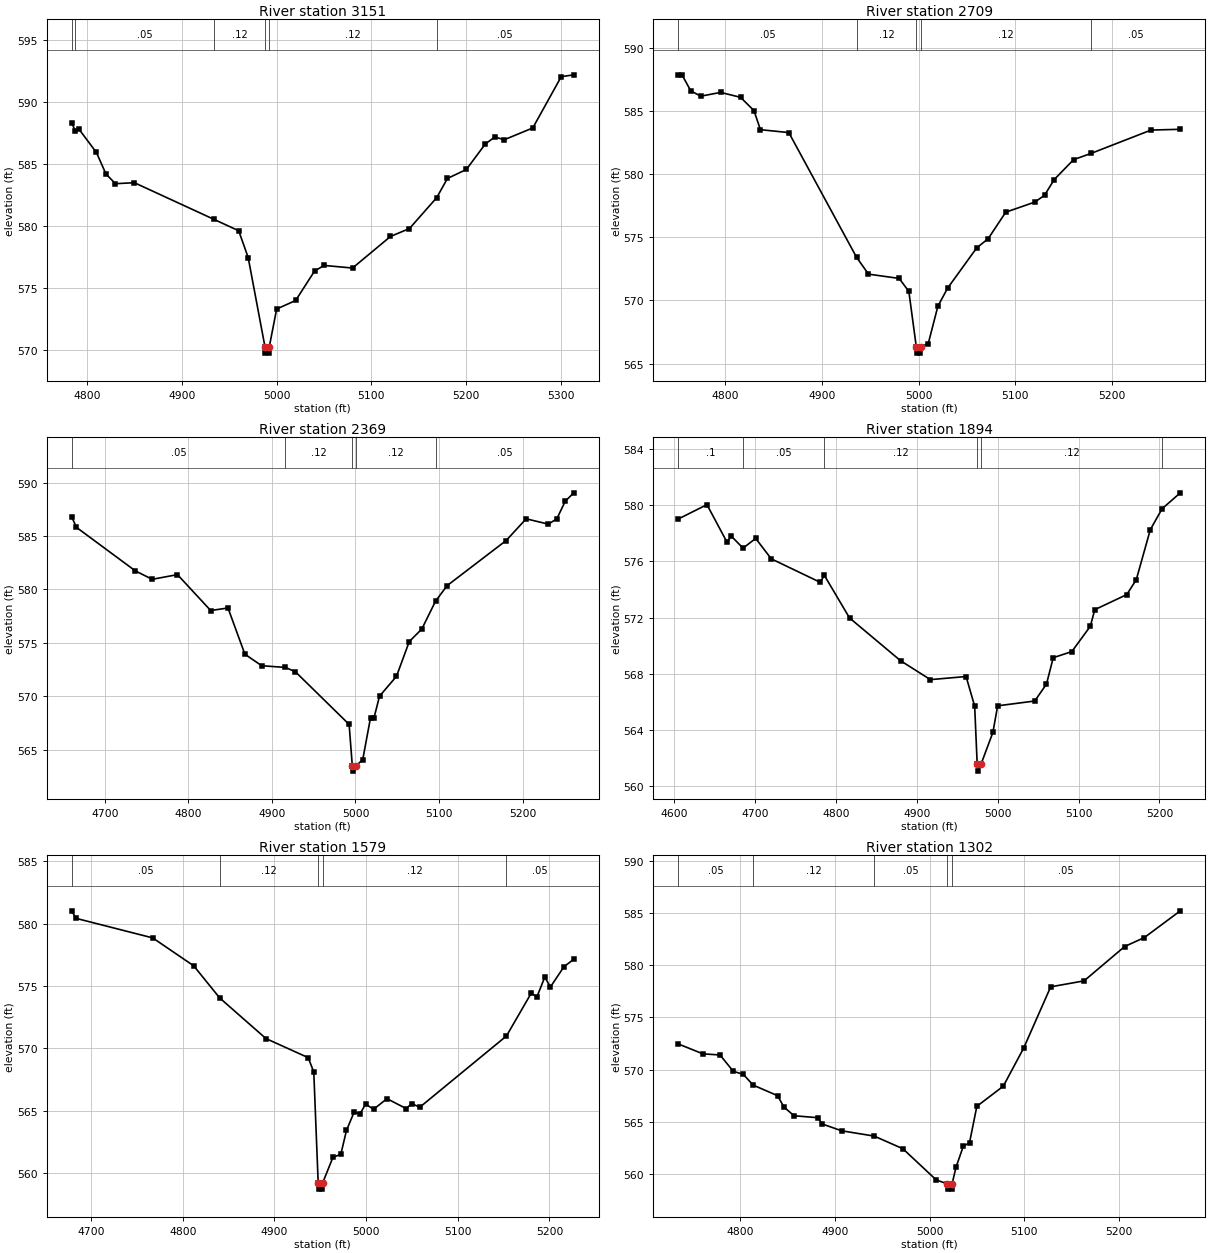
Type RM Length L Ch R = 1 ,3151    ,442,442,442
BEGIN DESCRIPTION:
South Fork Kirkwood Br 7.0
END DESCRIPTION:
XS GIS Cut Line= 2
      2379813.05      7041455.04      2380342.32      7041449.72
#Sta/Elev= 30
  4784.1  588.31    4788  587.66  4791.6  587.83  4810.1  585.94  4820.1  584.21
  4830.1  583.42  4850.1   583.5    4934  580.54  4960.1  579.62  4970.1  577.45
  4987.8  570.24  4988.3  569.74  4991.9  569.74  4992.3  570.24  5000.1   573.3
  5020.1  573.99  5040.1  576.37  5050.1  576.82  5080.1  576.61  5120.1  579.16
  5140.1   579.8  5168.8  582.29  5180.1  583.84  5200.1  584.57  5220.1  586.63
  5230.1  587.19  5240.1  586.97  5270.1  587.92  5300.1  592.06  5313.4  592.21
#Mann= 6 ,-1 , 0
  4784.1     .12       0    4788     .05       0    4934     .12       0
  4987.8     .07       0  4992.3     .12       0  5168.8     .05       0
Bank Sta=4987.8,4992.3
XS Rating Curve= 0 ,0
Exp/Cntr=0.3,0.1

Type RM Length L Ch R = 1 ,2709    ,340,340,340
BEGIN DESCRIPTION:
South Fork Kirkwood Br 6.0
END DESCRIPTION:
XS GIS Cut Line= 3
      2379736.41      7041766.36      2379936.45      7041816.37
      2380249.21      7041840.63
#Sta/Elev= 30
  4751.2  587.85  4755.1  587.85  4764.2  586.58  4774.5  586.16  4795.1  586.46
  4815.7  586.07  4829.6  585.02  4836.3  583.51  4865.7  583.28  4935.8  573.42
  4948.2  572.08    4980  571.74    4990  570.71  4997.7  566.33  4998.2  565.83
  5001.9  565.83  5002.4  566.33  5010.1  566.59  5020.1  569.55  5030.2  570.98
  5060.3  574.16  5072.1  574.88  5090.3  576.98  5120.4  577.78  5130.5  578.32
  5140.5  579.56  5160.6  581.14  5178.6  581.63  5240.8  583.48  5271.1  583.54
#Mann= 5 ,-1 , 0
  4751.2     .05       0  4935.8     .12       0  4997.7     .07       0
  5002.4     .12       0  5178.6     .05       0
Bank Sta=4997.7,5002.4
XS Rating Curve= 0 ,0
Exp/Cntr=0.3,0.1

Type RM Length L Ch R = 1 ,2369    ,475,475,475
BEGIN DESCRIPTION:
South Fork Kirkwood Br 5.0
END DESCRIPTION:
XS GIS Cut Line= 3
      2379693.46      7042186.33      2380052.43      7042141.12
      2380289.11      7042106.55
#Sta/Elev= 30
  4660.4  586.78    4666  585.81  4736.5  581.74  4756.7  580.95  4786.9  581.39
  4826.7  578.03  4847.4  578.27  4867.6  573.95  4887.7  572.87  4915.9  572.71
    4928  572.31  4992.4  567.38  4996.2  563.51  4996.7  563.01  5000.9  563.51
  5008.7  564.09    5018     568  5022.2     568  5028.8  570.02  5049.1  571.88
  5064.4  575.13  5079.4   576.3  5095.8   578.9  5109.7  580.36  5180.4  584.58
  5204.3  586.61    5231  586.11  5241.1  586.62  5251.2  588.27  5261.4  589.04
#Mann= 5 ,-1 , 0
  4660.4     .05       0  4915.9     .12       0  4996.2     .07       0
  5000.9     .12       0  5095.8     .05       0
Bank Sta=4996.2,5000.9
XS Rating Curve= 0 ,0
Exp/Cntr=0.3,0.1

Type RM Length L Ch R = 1 ,1894    ,315,315,315
BEGIN DESCRIPTION:
South Fork Kirkwood Br 4.0
END DESCRIPTION:
XS GIS Cut Line= 3
      2379810.49      7042707.53      2380012.54      7042630.42
      2380378.99      7042460.01
#Sta/Elev= 30
  4605.4     579  4640.9  580.02  4665.6  577.36    4671  577.78  4685.5  576.93
  4701.1  577.62  4720.4  576.17  4780.6  574.51    4786  574.99  4817.1  571.97
  4880.2  568.93    4917  567.59  4961.1  567.81  4971.7   565.7  4974.8  561.59
  4975.4  561.09  4979.6  561.59  4994.2  563.84  5000.1  565.73  5045.9  566.07
  5060.4  567.27  5068.8  569.15  5091.7  569.58  5114.6  571.38  5120.1  572.56
  5159.6  573.63  5171.4  574.69  5188.7  578.24  5203.3  579.73  5225.8  580.86
#Mann= 6 ,-1 , 0
  4605.4      .1       0  4685.5     .05       0    4786     .12       0
  4974.8     .07       0  4979.6     .12       0  5203.3     .05       0
Bank Sta=4974.8,4979.6
XS Rating Curve= 0 ,0
Exp/Cntr=0.3,0.1

Type RM Length L Ch R = 1 ,1579    ,277,277,277
BEGIN DESCRIPTION:
South Fork Kirkwood Br 3.0
END DESCRIPTION:
XS GIS Cut Line= 3
      2379919.48      7042986.76      2380126.89      7042883.05
      2380384.39      7042699.88
#Sta/Elev= 30
  4678.8  581.02  4683.3  580.42  4767.1  578.85  4811.9  576.61  4840.3  574.03
  4890.7  570.78  4936.8  569.25  4942.9   568.1  4947.7  559.21  4948.3  558.71
    4952  558.71  4952.6  559.21  4963.8  561.26  4972.4   561.5  4978.6  563.42
  4986.9  564.88  4993.3  564.74  4999.5  565.53  5008.1  565.11  5022.8  565.96
  5043.7  565.17  5049.9  565.57  5058.5  565.27  5153.2  570.99  5180.2  574.42
  5186.4  574.12    5195  575.71  5201.1  574.91  5215.9  576.54  5226.7  577.14
#Mann= 5 ,-1 , 0
  4678.8     .05       0  4840.3     .12       0  4947.7     .07       0
  4952.6     .12       0  5153.2     .05       0
Bank Sta=4947.7,4952.6
XS Rating Curve= 0 ,0
Exp/Cntr=0.3,0.1

Type RM Length L Ch R = 1 ,1302    ,95,95,95
BEGIN DESCRIPTION:
South Fork Kirkwood Br 2.2
END DESCRIPTION:
XS GIS Cut Line= 3
      2380214.62      7043101.12      2380350.27      7043050.58
      2380600.22      7042758.09
#Sta/Elev= 30
  4734.9  572.46  4760.9  571.51    4779   571.4  4792.9  569.84  4803.6  569.54
  4813.8  568.52  4839.7   567.5  4846.3  566.42    4857  565.58  4882.5  565.39
  4886.2  564.81  4907.1  564.14  4941.6  563.63  4971.8  562.42    5007  559.43
  5018.8  559.05  5019.4  558.55  5023.1  558.55  5023.7  559.05  5027.8  560.63
  5035.5  562.65  5042.1     563  5049.8  566.48  5077.7  568.41  5099.2  572.06
  5127.7  577.93  5162.9   578.5  5205.7  581.79  5226.5  582.65  5264.4  585.21
#Mann= 5 ,-1 , 0
  4734.9     .05       0  4813.8     .12       0  4941.6     .05       0
  5018.8    .033       0  5023.7     .05       0
Bank Sta=5018.8,5023.7
XS Rating Curve= 0 ,0
Exp/Cntr=0.3,0.1