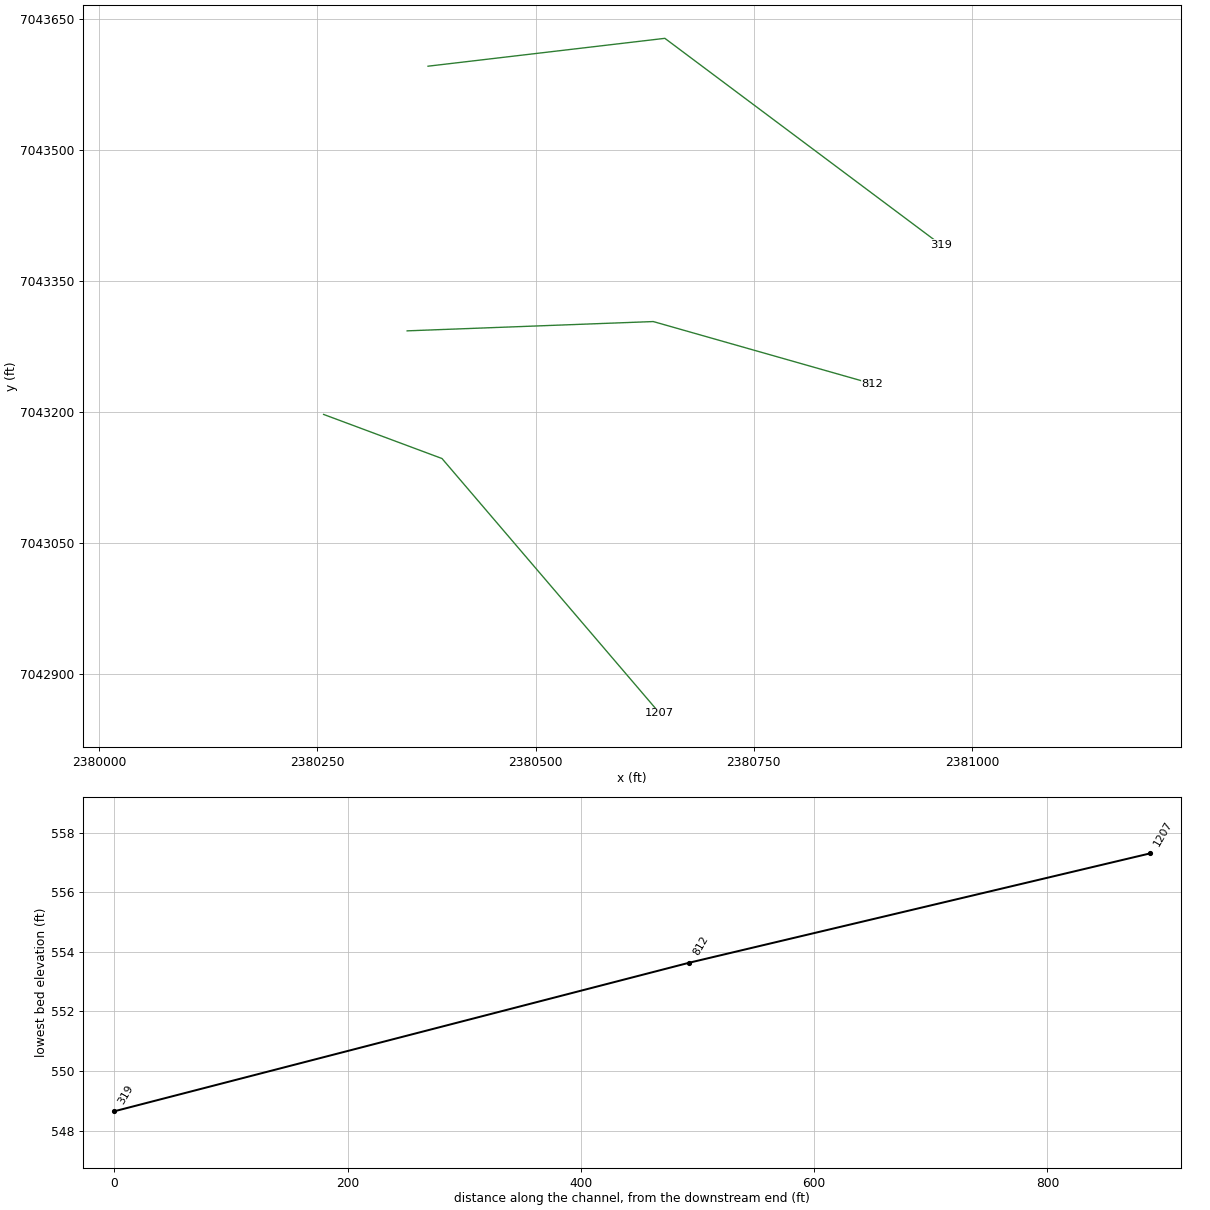
HEC-RAS study South Fork Kirkwood Br.prj: South Fork Kirkwood Br Base Level Engineering

--- South Fork Kirkwood Br.g01 (geometry) --- (continued)

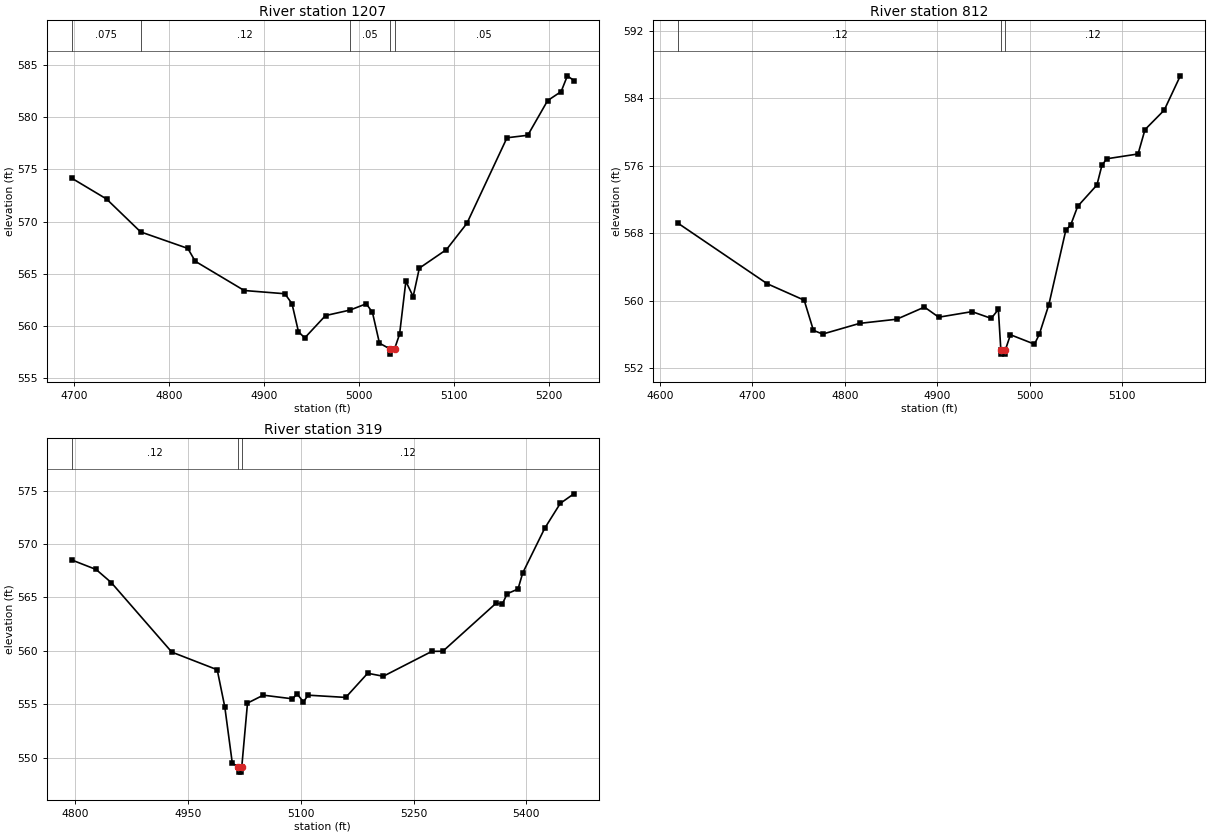
Type RM Length L Ch R = 1 ,1207    ,395,395,395
BEGIN DESCRIPTION:
South Fork Kirkwood Br 2.0
END DESCRIPTION:
XS GIS Cut Line= 3
      2380257.22      7043196.83      2380392.81      7043146.32
      2380642.28      7042854.39
#Sta/Elev= 30
  4697.9  574.15  4734.5  572.16  4770.4  569.01  4820.1  567.43  4827.9   566.2
  4879.5   563.4  4922.3  563.09  4929.8  562.14  4936.6  559.46  4943.2  558.86
  4965.1     561    4991  561.53    5008  562.13  5014.5  561.31  5021.9  558.36
  5032.9  557.81  5033.5  557.31  5037.8  557.81  5043.1  559.22  5049.7  564.28
  5057.4  562.82  5063.9  565.54  5092.5  567.32    5114  569.83  5156.2  578.02
  5178.1  578.26    5199  581.58  5213.2  582.44  5219.8  583.95  5226.6   583.5
#Mann= 5 ,-1 , 0
  4697.9    .075       0  4770.4     .12       0    4991     .05       0
  5032.9    .033       0  5037.8     .05       0
Bank Sta=5032.9,5037.8
XS Rating Curve= 0 ,0
Exp/Cntr=0.3,0.1

Type RM Length L Ch R = 1 ,812     ,493,493,493
BEGIN DESCRIPTION:
South Fork Kirkwood Br 1.0
END DESCRIPTION:
XS GIS Cut Line= 3
      2380352.89      7043292.57      2380634.81      7043303.21
      2380885.75      7043231.89
#Sta/Elev= 30
  4619.9  569.15  4716.1  561.99  4756.1  560.04  4766.1  556.46  4776.1  556.02
  4816.2  557.29  4856.2  557.78  4886.2  559.22  4901.6  558.02  4937.6  558.68
  4958.4  557.88  4966.1  558.94  4968.8  554.14  4969.4  553.64  4973.1  553.64
  4973.7  554.14  4979.2  555.94  5005.2  554.82  5010.4  555.99  5020.7   559.5
  5039.1  568.35  5044.3  568.94  5051.9  571.17  5072.7   573.7  5078.1  576.03
  5083.3  576.81  5117.2  577.38  5124.7  580.27  5145.5  582.58  5162.9  586.65
#Mann= 3 ,-1 , 0
  4619.9     .12       0  4968.8     .07       0  4973.7     .12       0
Bank Sta=4968.8,4973.7
XS Rating Curve= 0 ,0
Exp/Cntr=0.3,0.1

Type RM Length L Ch R = 1 ,319     ,0,0,0
BEGIN DESCRIPTION:
South Fork Kirkwood Br 0.5
END DESCRIPTION:
XS GIS Cut Line= 3
      2380376.82      7043595.73       2380648.1      7043627.64
       2380964.3      7043391.16
#Sta/Elev= 30
  4795.3   568.5  4827.7  567.61  4847.8  566.39  4928.4  559.88  4988.8  558.23
  4998.9  554.75  5008.9  549.48  5016.6  549.15  5017.2  548.65  5020.9  548.65
  5021.5  549.15  5029.1  555.11  5050.1  555.85  5088.9  555.51  5095.2  555.96
  5103.5  555.22  5109.8  555.85  5159.8  555.64    5189   557.9  5209.8  557.62
  5274.4  559.95    5289  559.96  5359.9  564.46  5368.2  564.38  5374.5  565.34
    5389  565.78  5395.3  567.29  5424.5  571.46  5445.3   573.8  5463.3  574.69
#Mann= 3 ,-1 , 0
  4795.3     .12       0  5016.6     .07       0  5021.5     .12       0
Bank Sta=5016.6,5021.5
XS Rating Curve= 0 ,0
Exp/Cntr=0.3,0.1

Chan Stop Cuts=-1
Use User Specified Reach Order=0
Composite Channel Slope=5