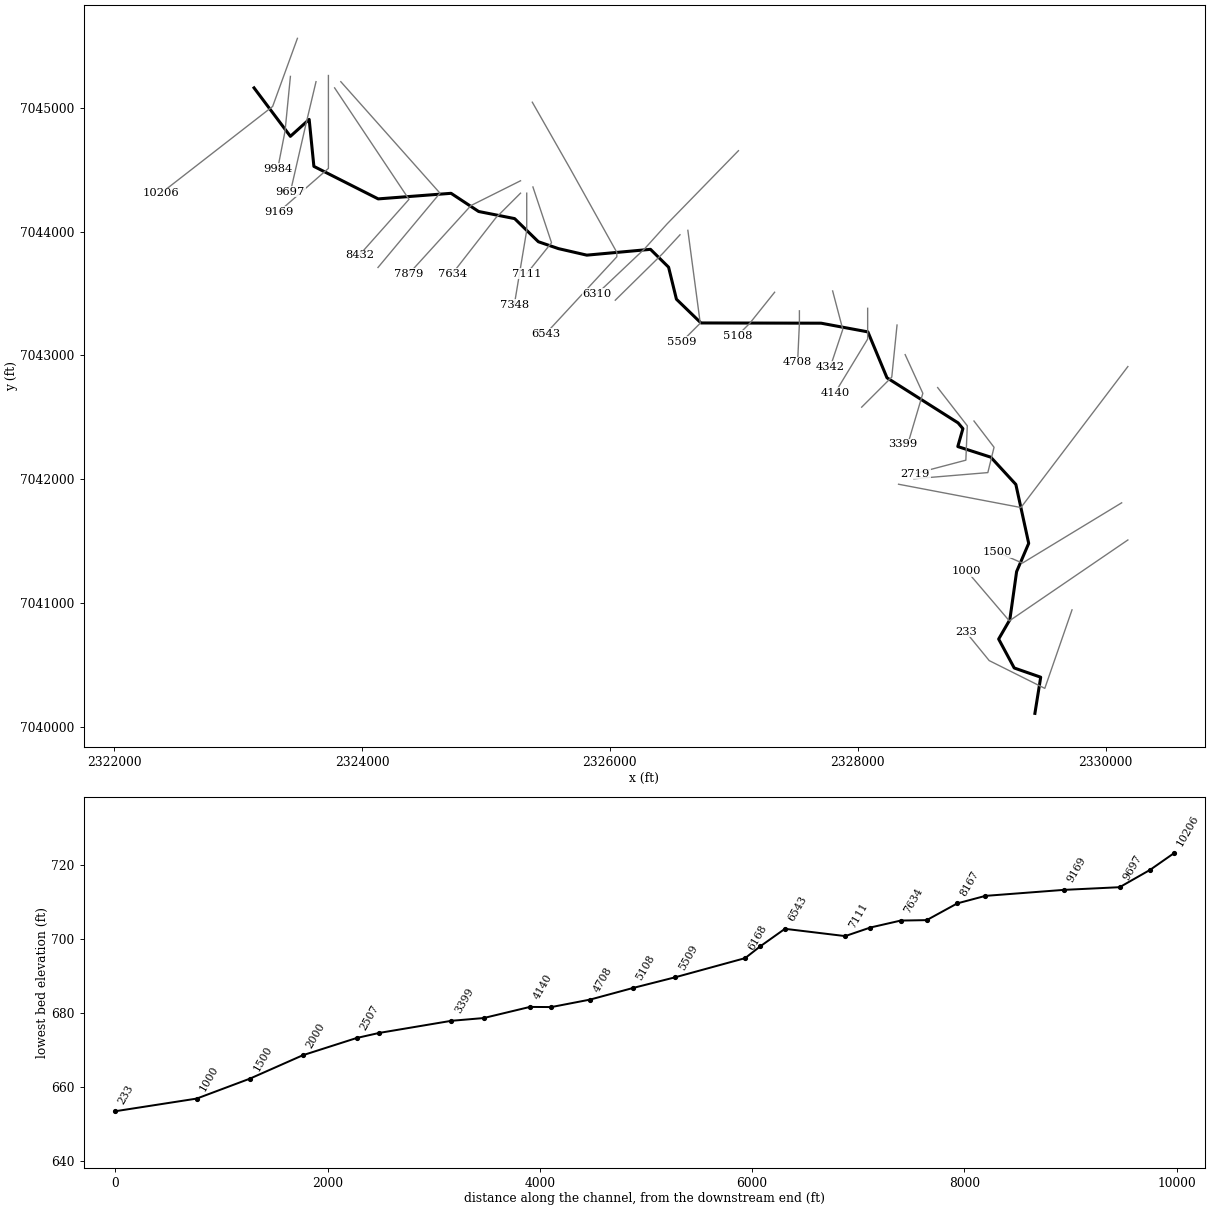
--- Stream HEN-1.prj (project) ---

Proj Title=Stream HEN-1 Base Level Engineering
Current Plan=p01
Default Exp/Contr=0.3,0.1
English Units
Geom File=g01
Flow File=f01
Plan File=p01
BEGIN DESCRIPTION:
Stream HEN-1
END DESCRIPTION:

--- Stream HEN-1.p01 (plan) ---

Plan Title=Multiple Run
Short Identifier=Multiple
Geom File=g01
Flow File=f01
Subcritical Flow
K Sum by GR= 0
Std Step Tol= 0.01
Critical Tol= 0.01
Num of Std Step Trials= 20
Max Error Tol= 0.3
Flow Tol Ratio= 0.001
Split Flow NTrial= 30
Split Flow Tol= 0.02
Split Flow Ratio= 0.02
Log Output Level= 0
Friction Slope Method= 1
Unsteady Friction Slope Method= 2
Unsteady Bridges Friction Slope Method= 1
Parabolic Critical Depth
Global Vel Dist=  1 , 1 , 1
Global Log Level= 0
CheckData=True
Encroach Param= -1, 0, 0, 0
BEGIN DESCRIPTION:
Multiple Run
END DESCRIPTION:

--- Stream HEN-1.f01 (steady flow) ---

Flow Title=Multiple
Number of Profiles=7
Profile Names=10-year,25-year,50-year,1pct_min,100-year,1pct_plu,500-year
River Rch & RM= Stream HEN-1,Reach-1,10206
     377     495     587     345     689    1370     949
River Rch & RM= Stream HEN-1,Reach-1,5108
     449     597     714     424     845    1690    1180
River Rch & RM= Stream HEN-1,Reach-1,4140
     424     562     672     399     795    1590    1110
River Rch & RM= Stream HEN-1,Reach-1,2000
     424     562     672     399     795    1590    1110
River Rch & RM= Stream HEN-1,Reach-1,233
     431     572     683     406     809    1610    1130
Boundary for River Rch & Prof#=Stream HEN-1,Reach-1,1
Up Type=0
Dn Type=3
Dn Slope=0.005
Boundary for River Rch & Prof#=Stream HEN-1,Reach-1,2
Up Type=0
Dn Type=3
Dn Slope=0.005
Boundary for River Rch & Prof#=Stream HEN-1,Reach-1,3
Up Type=0
Dn Type=3
Dn Slope=0.005
Boundary for River Rch & Prof#=Stream HEN-1,Reach-1,4
Up Type=0
Dn Type=3
Dn Slope=0.005
Boundary for River Rch & Prof#=Stream HEN-1,Reach-1,5
Up Type=0
Dn Type=3
Dn Slope=0.005
Boundary for River Rch & Prof#=Stream HEN-1,Reach-1,6
Up Type=0
Dn Type=3
Dn Slope=0.005
Boundary for River Rch & Prof#=Stream HEN-1,Reach-1,7
Up Type=0
Dn Type=3
Dn Slope=0.005

--- Stream HEN-1.g01 (geometry) ---

Geom Title=Existing Conditions

River Reach=Stream HEN-1,Reach-1
Reach XY= 30
      2323129.00      7045160.00      2323422.20      7044768.77
      2323573.79      7044905.45      2323611.78      7044526.27
      2324130.55      7044263.75      2324718.50      7044308.81
      2324940.99      7044162.03      2325231.45      7044104.53
      2325422.83      7043917.86      2325584.94      7043862.27
      2325813.82      7043809.57      2326327.54      7043856.46
      2326473.48      7043712.43      2326536.86      7043453.83
      2326734.85      7043262.06      2327704.08      7043260.20
      2328081.51      7043190.00      2328235.59      7042819.33
      2328809.00      7042455.46      2328848.12      7042408.84
      2328806.85      7042264.14      2329073.19      7042178.40
      2329275.24      7041958.44      2329378.98      7041482.78
      2329281.38      7041254.47      2329226.75      7040865.93
      2329136.53      7040710.01      2329262.21      7040476.44
      2329475.78      7040402.02      2329429.00      7040110.00

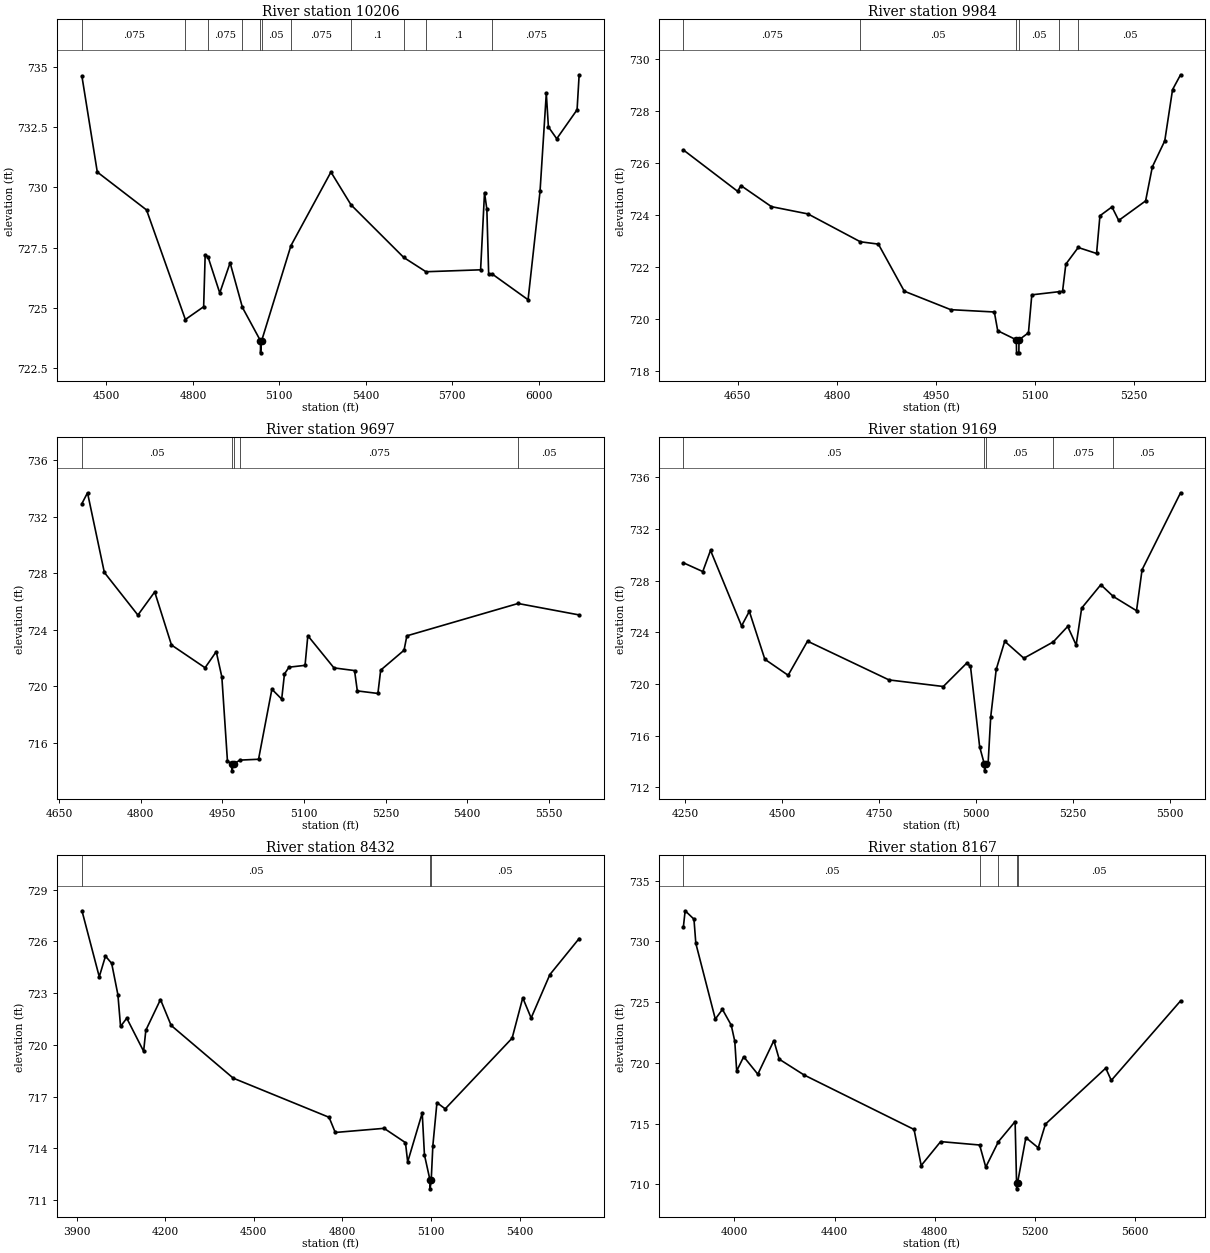
Type RM Length L Ch R = 1,10206,222,222,222
BEGIN DESCRIPTION:
Stream HEN-1 20.0
END DESCRIPTION:
XS GIS Cut Line= 3
      2323479.01      7045560.02      2323279.00      7045010.00
      2322379.03      7044310.02
#Sta/Elev= 30
  4415.0  734.59  4468.2  730.63  4639.1  729.06  4773.8  724.52  4837.3  725.05
  4842.6  727.20  4852.6  727.11  4893.2  725.62  4929.1  726.87  4971.9  725.02
  5034.5  723.64  5034.7  723.14  5038.5  723.64  5140.2  727.58  5279.0  730.63
  5348.8  729.27  5531.8  727.09  5608.8  726.50  5798.4  726.58  5812.0  729.78
  5820.1  729.09  5826.4  726.39  5838.1  726.41  5963.1  725.34  6004.7  729.84
  6026.4  733.89  6033.7  732.50  6062.6  732.01  6133.2  733.21  6140.4  734.66
#Mann=11,-1,0
  4415.0   0.075       0  4773.8    0.05       0  4852.6   0.075       0
  4971.9    0.05       0  5034.5    0.05       0  5038.5    0.05       0
  5140.2   0.075       0  5348.8     0.1       0  5531.8   0.075       0
  5608.8     0.1       0  5838.1   0.075       0
Bank Sta=5034.5,5038.5
Exp/Cntr=0.3,0.1

Type RM Length L Ch R = 1,9984,287,287,287
BEGIN DESCRIPTION:
Stream HEN-1 19.0
END DESCRIPTION:
XS GIS Cut Line= 3
      2323422.40      7045252.69      2323379.00      7044810.00
      2323320.09      7044508.11
#Sta/Elev= 30
  4567.6  726.49  4649.7  724.90  4654.7  725.12  4700.9  724.31  4756.2  724.03
  4835.4  722.96  4862.7  722.87  4901.9  721.06  4972.2  720.35  5038.2  720.26
  5043.3  719.54  5071.5  719.19  5071.8  718.69  5075.3  718.69  5075.5  719.19
  5089.8  719.46  5094.9  720.92  5135.8  721.04  5141.4  721.05  5146.4  722.10
  5165.1  722.74  5192.9  722.51  5198.0  723.96  5216.2  724.30  5226.4  723.78
  5267.1  724.53  5277.3  725.84  5296.1  726.84  5307.9  728.81  5320.0  729.38
#Mann=6,-1,0
  4567.6   0.075       0  4835.4    0.05       0  5071.5    0.05       0
  5075.5    0.05       0  5135.8   0.075       0  5165.1    0.05       0
Bank Sta=5071.5,5075.5
Exp/Cntr=0.3,0.1

Type RM Length L Ch R = 1,9697,528,528,528
BEGIN DESCRIPTION:
Stream HEN-1 18.0
END DESCRIPTION:
XS GIS Cut Line= 3
      2323628.99      7045209.95      2323547.45      7044866.22
      2323422.40      7044320.54
#Sta/Elev= 30
  4692.3  732.93  4702.5  733.69  4733.4  728.05  4795.0  725.03  4825.9  726.67
  4856.7  722.91  4918.4  721.30  4938.9  722.44  4949.2  720.65  4959.5  714.69
  4967.2  714.50  4967.5  714.00  4971.2  714.50  4982.6  714.76  5016.6  714.82
  5041.1  719.78  5059.1  719.08  5064.2  720.86  5072.5  721.34  5102.0  721.47
  5107.1  723.57  5155.1  721.29  5192.9  721.10  5198.0  719.66  5235.8  719.48
  5240.9  721.13  5283.8  722.54  5289.0  723.56  5493.2  725.85  5605.4  725.04
#Mann=5,-1,0
  4692.3    0.05       0  4967.2    0.07       0  4971.2    0.05       0
  4982.6   0.075       0  5493.2    0.05       0
Bank Sta=4967.2,4971.2
Exp/Cntr=0.3,0.1

Type RM Length L Ch R = 1,9169,737,737,737
BEGIN DESCRIPTION:
Stream HEN-1 17.0
END DESCRIPTION:
XS GIS Cut Line= 3
      2323729.00      7045259.96      2323729.00      7044510.00
      2323328.97      7044159.98
#Sta/Elev= 30
  4245.5  729.38  4295.5  728.70  4315.5  730.34  4395.5  724.49  4415.5  725.62
  4455.5  721.91  4515.5  720.67  4565.5  723.31  4775.5  720.31  4915.5  719.80
  4975.5  721.60  4985.5  721.37  5009.2  715.13  5021.5  713.77  5021.7  713.27
  5025.5  713.77  5031.1  713.91  5037.7  717.45  5051.9  721.13  5073.8  723.30
  5123.1  721.99  5198.8  723.25  5236.1  724.45  5257.9  723.01  5272.1  725.87
  5321.5  727.68  5353.7  726.77  5413.5  725.67  5427.8  728.84  5527.0  734.80
#Mann=5,-1,0
  4245.5    0.05       0  5021.5    0.04       0  5025.5    0.05       0
  5198.8   0.075       0  5353.7    0.05       0
Bank Sta=5021.5,5025.5
Exp/Cntr=0.3,0.1

Type RM Length L Ch R = 1,8432,265,265,265
BEGIN DESCRIPTION:
Stream HEN-1 16.0
END DESCRIPTION:
XS GIS Cut Line= 3
      2323779.00      7045159.99      2324379.00      7044260.00
      2323979.02      7043810.03
#Sta/Elev= 30
  3918.3  727.78  3976.9  723.95  3997.9  725.15  4018.9  724.73  4040.0  722.91
  4049.0  721.07  4070.0  721.55  4127.1  719.63  4134.6  720.85  4184.2  722.63
  4220.3  721.13  4430.6  718.07  4755.1  715.80  4776.1  714.92  4941.4  715.16
  5013.8  714.33  5021.3  713.21  5070.6  716.05  5078.1  713.62  5097.0  712.15
  5097.3  711.65  5101.0  712.15  5106.6  714.16  5120.4  716.65  5148.4  716.29
  5375.0  720.39  5411.0  722.73  5439.4  721.56  5502.9  724.08  5602.0  726.17
#Mann=3,-1,0
  3918.3    0.05       0  5097.0   0.033       0  5101.0    0.05       0
Bank Sta=5097,5101
Exp/Cntr=0.3,0.1

Type RM Length L Ch R = 1,8167,288,288,288
BEGIN DESCRIPTION:
Stream HEN-1 15.0
END DESCRIPTION:
XS GIS Cut Line= 3
      2323828.98      7045210.03      2324629.00      7044310.00
      2324129.01      7043710.02
#Sta/Elev= 30
  3796.4  731.18  3803.5  732.52  3838.7  731.83  3846.2  729.83  3924.0  723.60
  3952.4  724.40  3987.5  723.10  4001.7  721.77  4009.3  719.33  4037.3  720.50
  4093.7  719.06  4157.7  721.83  4179.0  720.30  4278.1  719.00  4717.5  714.51
  4746.0  711.54  4823.7  713.51  4979.4  713.23  5003.8  711.41  5054.5  713.51
  5121.0  715.16  5126.8  710.12  5127.1  709.62  5130.8  710.12  5164.0  713.84
  5213.4  713.00  5242.1  714.95  5482.9  719.56  5505.0  718.55  5781.6  725.10
#Mann=5,-1,0
  3796.4    0.05       0  4979.4    0.12       0  5054.5    0.05       0
  5126.8    0.07       0  5130.8    0.05       0
Bank Sta=5126.8,5130.8
Exp/Cntr=0.3,0.1

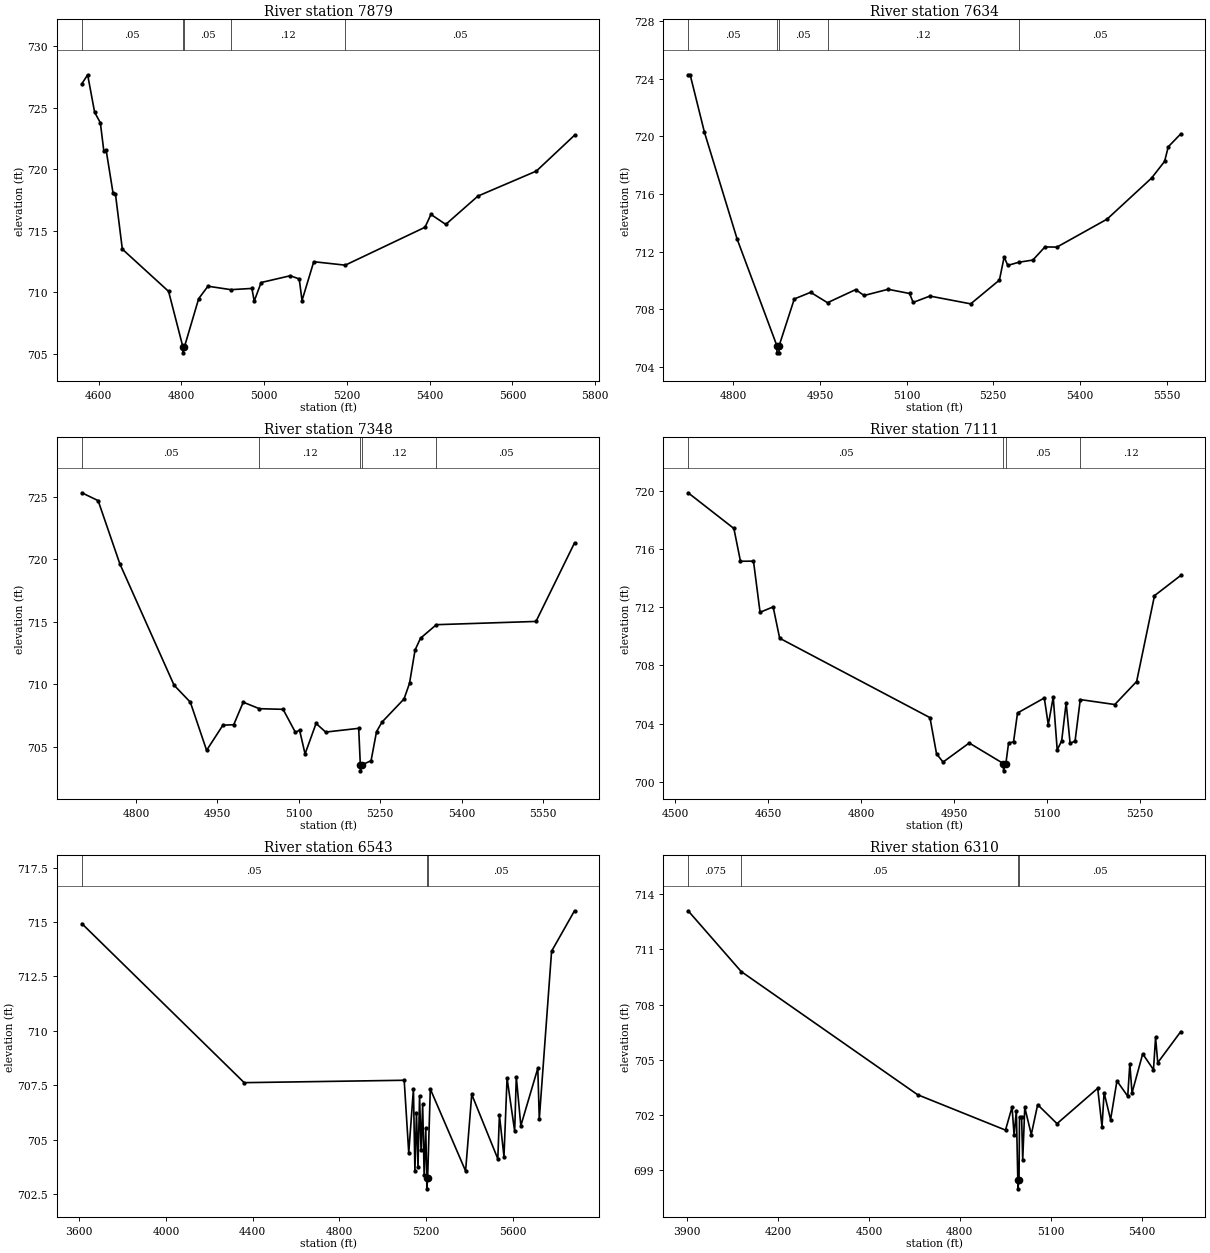
Type RM Length L Ch R = 1,7879,245,245,245
BEGIN DESCRIPTION:
Stream HEN-1 14.0
END DESCRIPTION:
XS GIS Cut Line= 3
      2325279.01      7044410.00      2324879.00      7044210.00
      2324379.02      7043660.02
#Sta/Elev= 30
  4559.4  726.94  4573.4  727.67  4590.2  724.63  4604.1  723.77  4612.5  721.47
  4618.1  721.55  4634.9  718.03  4640.5  718.00  4657.2  713.51  4769.0  710.08
  4803.4  705.59  4803.6  705.09  4807.4  705.59  4841.7  709.49  4864.1  710.50
  4919.5  710.22  4970.3  710.32  4975.9  709.29  4992.6  710.80  5063.0  711.35
  5084.7  711.09  5091.4  709.34  5119.8  712.49  5195.9  712.21  5388.7  715.29
  5402.9  716.33  5438.8  715.52  5516.5  717.82  5657.7  719.85  5749.9  722.76
#Mann=5,-1,0
  4559.4    0.05       0  4803.4    0.07       0  4807.4    0.05       0
  4919.5    0.12       0  5195.9    0.05       0
Bank Sta=4803.4,4807.4
Exp/Cntr=0.3,0.1

Type RM Length L Ch R = 1,7634,286,286,286
BEGIN DESCRIPTION:
Stream HEN-1 13.0
END DESCRIPTION:
XS GIS Cut Line= 3
      2325279.00      7044310.00      2325079.00      7044110.00
      2324729.02      7043660.03
#Sta/Elev= 30
  4721.7  724.27  4725.2  724.27  4750.0  720.27  4806.6  712.86  4875.3  705.47
  4875.5  704.97  4879.0  704.97  4879.3  705.47  4905.5  708.71  4933.8  709.17
  4963.0  708.45  5011.8  709.36  5026.3  708.95  5067.9  709.38  5105.0  709.09
  5111.3  708.47  5140.3  708.91  5210.9  708.37  5260.6  710.02  5268.8  711.62
  5275.1  711.04  5294.5  711.26  5318.5  711.41  5339.4  712.32  5360.2  712.31
  5447.0  714.25  5524.0  717.10  5546.6  718.26  5552.9  719.27  5574.6  720.17
#Mann=5,-1,0
  4721.7    0.05       0  4875.3    0.07       0  4879.3    0.05       0
  4963.0    0.12       0  5294.5    0.05       0
Bank Sta=4875.3,4879.3
Exp/Cntr=0.3,0.1

Type RM Length L Ch R = 1,7348,237,237,237
BEGIN DESCRIPTION:
Stream HEN-1 12.0
END DESCRIPTION:
XS GIS Cut Line= 3
      2325329.00      7044309.99      2325329.00      7044010.00
      2325228.99      7043409.97
#Sta/Elev= 30
  4700.0  725.33  4730.0  724.70  4770.0  719.65  4870.0  709.94  4900.0  708.58
  4930.0  704.73  4960.0  706.74  4980.0  706.78  4997.5  708.58  5027.3  708.06
  5071.0  708.01  5093.8  706.16  5101.4  706.35  5111.5  704.44  5131.8  706.88
  5149.5  706.19  5210.4  706.49  5213.4  703.59  5213.7  703.09  5217.4  703.59
  5233.2  703.90  5243.3  706.23  5253.4  706.99  5294.0  708.84  5304.1  710.09
  5314.3  712.75  5324.4  713.70  5353.6  714.78  5537.3  715.04  5608.3  721.32
#Mann=5,-1,0
  4700.0    0.05       0  5027.3    0.12       0  5213.4   0.033       0
  5217.4    0.12       0  5353.6    0.05       0
Bank Sta=5213.4,5217.4
Exp/Cntr=0.3,0.1

Type RM Length L Ch R = 1,7111,568,568,568
BEGIN DESCRIPTION:
Stream HEN-1 11.0
END DESCRIPTION:
XS GIS Cut Line= 3
      2325378.99      7044360.03      2325529.00      7043910.00
      2325329.02      7043660.02
#Sta/Elev= 30
  4521.2  719.85  4595.0  717.40  4605.6  715.15  4626.6  715.16  4637.2  711.65
  4658.3  712.02  4668.8  709.87  4911.2  704.42  4921.8  701.94  4932.3  701.37
  4974.5  702.68  5029.6  701.27  5029.8  700.77  5033.6  701.27  5038.0  702.68
  5046.0  702.76  5052.4  704.74  5095.6  705.77  5102.0  703.93  5110.0  705.83
  5116.4  702.21  5123.6  702.82  5130.8  705.43  5137.2  702.66  5145.2  702.81
  5153.6  705.66  5209.3  705.32  5244.5  706.90  5273.3  712.79  5315.7  714.18
#Mann=4,-1,0
  4521.2    0.05       0  5029.6   0.033       0  5033.6    0.05       0
  5153.6    0.12       0
Bank Sta=5029.6,5033.6
Exp/Cntr=0.3,0.1

Type RM Length L Ch R = 1,6543,233,233,233
BEGIN DESCRIPTION:
Stream HEN-1 10.0
END DESCRIPTION:
XS GIS Cut Line= 5
      2325374.01      7045044.30      2325676.58      7044512.90
      2326055.85      7043832.15      2326055.85      7043796.07
      2325483.11      7043176.50
#Sta/Elev= 30
  3612.7  714.93  4360.9  707.62  5098.3  707.73  5119.3  704.39  5140.9  707.33
  5147.7  703.58  5155.0  706.24  5161.9  703.73  5169.2  707.02  5176.0  704.52
  5183.4  706.62  5190.2  703.38  5197.6  705.53  5202.4  703.24  5202.6  702.74
  5206.4  703.24  5218.6  707.33  5381.3  703.56  5409.6  707.08  5529.8  704.12
  5537.2  706.13  5558.2  704.22  5572.4  707.83  5607.5  705.39  5614.9  707.89
  5635.9  705.64  5714.1  708.28  5720.9  705.94  5777.6  713.66  5883.3  715.52
#Mann=3,-1,0
  3612.7    0.05       0  5202.4   0.033       0  5206.4    0.05       0
Bank Sta=5202.4,5206.4
Exp/Cntr=0.3,0.1

Type RM Length L Ch R = 1,6310,142,142,142
BEGIN DESCRIPTION:
Stream HEN-1 9.0
END DESCRIPTION:
XS GIS Cut Line= 4
      2327037.14      7044652.90      2326460.38      7044060.80
      2326279.00      7043860.00      2325895.02      7043496.38
#Sta/Elev= 30
  3903.4  713.09  4078.6  709.79  4660.9  703.10  4950.9  701.18  4972.5  702.43
  4979.3  700.90  4986.7  702.24  4991.5  698.49  4991.7  697.99  4995.5  698.49
  4997.2  701.89  5004.0  701.89  5007.7  699.55  5014.5  702.41  5036.0  700.94
  5057.0  702.56  5120.9  701.53  5255.2  703.45  5269.4  701.36  5276.3  703.21
  5297.7  701.75  5318.7  703.85  5354.3  703.02  5361.2  704.78  5368.5  703.20
  5403.7  705.32  5439.3  704.46  5446.2  706.21  5453.4  704.84  5529.4  706.53
#Mann=4,-1,0
  3903.4   0.075       0  4078.6    0.05       0  4991.5    0.05       0
  4995.5    0.05       0
Bank Sta=4991.5,4995.5
Exp/Cntr=0.3,0.1

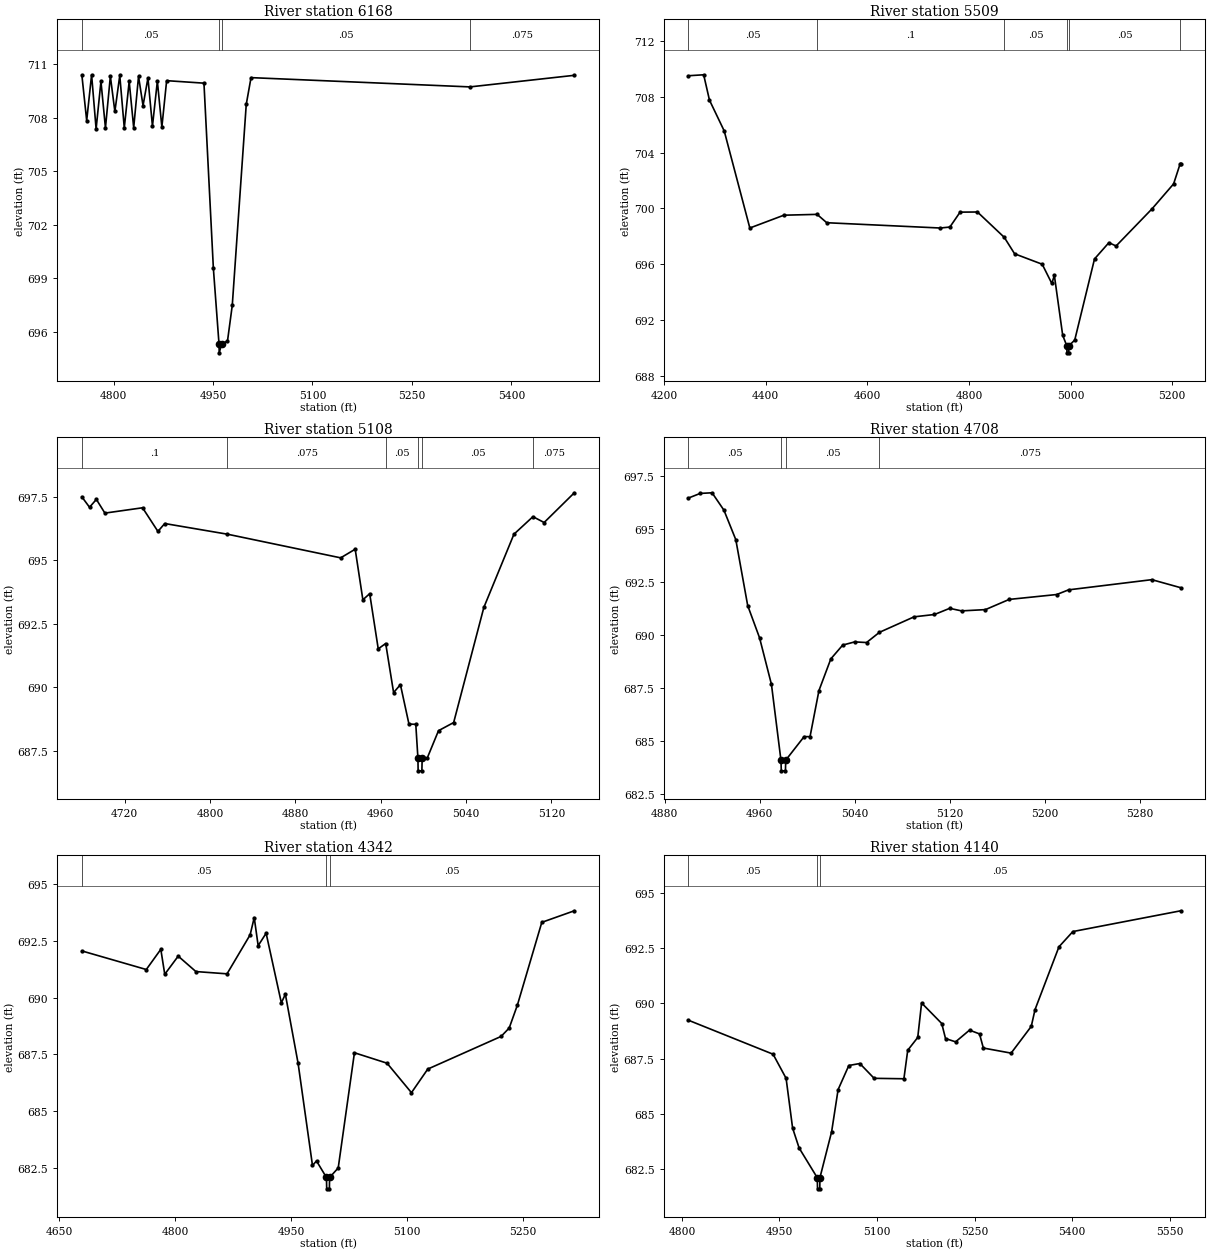
Type RM Length L Ch R = 1,6168,659,659,659
BEGIN DESCRIPTION:
Stream HEN-1 8.0
END DESCRIPTION:
XS GIS Cut Line= 3
      2326565.74      7043973.84      2326423.61      7043820.34
      2326043.39      7043445.80
#Sta/Elev= 30
  4752.1  710.40  4759.4  707.84  4766.8  710.41  4773.6  707.37  4780.9  710.04
  4787.7  707.43  4795.1  710.33  4801.9  708.35  4809.3  710.37  4816.1  707.43
  4823.5  710.04  4830.3  707.44  4837.6  710.32  4844.4  708.68  4851.8  710.23
  4858.6  707.53  4866.0  710.05  4872.8  707.48  4880.0  710.08  4936.3  709.94
  4950.5  699.55  4959.0  695.31  4959.3  694.81  4963.0  695.31  4971.8  695.47
  4979.0  697.47  5000.1  708.75  5007.3  710.25  5337.6  709.73  5495.0  710.38
#Mann=4,-1,0
  4752.1    0.05       0  4959.0    0.05       0  4963.0    0.05       0
  5337.6   0.075       0
Bank Sta=4959,4963
Exp/Cntr=0.3,0.1

Type RM Length L Ch R = 1,5509,401,401,401
BEGIN DESCRIPTION:
Stream HEN-1 7.0
END DESCRIPTION:
XS GIS Cut Line= 3
      2326629.01      7044009.96      2326729.00      7043260.00
      2326579.02      7043110.02
#Sta/Elev= 30
  4248.0  709.52  4278.2  709.59  4289.6  707.77  4318.6  705.56  4369.0  698.59
  4435.9  699.51  4501.3  699.57  4520.3  698.97  4743.6  698.59  4762.5  698.66
  4782.6  699.73  4816.7  699.74  4869.5  697.92  4889.8  696.74  4944.1  695.99
  4963.0  694.61  4968.0  695.19  4984.4  690.89  4992.5  690.13  4992.8  689.63
  4996.3  689.63  4996.5  690.13  5008.1  690.55  5047.0  696.37  5075.3  697.54
  5089.4  697.30  5160.2  699.97  5202.6  701.76  5215.6  703.22  5216.7  703.22
#Mann=6,-1,0
  4248.0    0.05       0  4501.3     0.1       0  4869.5    0.05       0
  4992.5   0.033       0  4996.5    0.05       0  5215.6   0.075       0
Bank Sta=4992.5,4996.5
Exp/Cntr=0.3,0.1

Type RM Length L Ch R = 1,5108,400,400,400
BEGIN DESCRIPTION:
Stream HEN-1 6.0
END DESCRIPTION:
XS GIS Cut Line= 3
      2327329.02      7043510.03      2327129.00      7043260.00
      2327029.01      7043160.01
#Sta/Elev= 30
  4679.8  697.49  4687.0  697.08  4693.4  697.39  4701.4  696.85  4736.7  697.06
  4751.1  696.13  4757.5  696.44  4816.3  696.02  4922.4  695.09  4936.0  695.43
  4943.2  693.44  4949.6  693.68  4957.6  691.51  4964.6  691.72  4972.0  689.79
  4978.4  690.10  4986.4  688.55  4992.8  688.54  4994.8  687.21  4995.0  686.71
  4998.5  686.71  4998.8  687.21  5003.5  687.21  5014.1  688.29  5028.3  688.61
  5056.6  693.14  5084.8  696.02  5102.6  696.71  5113.1  696.48  5141.4  697.65
#Mann=6,-1,0
  4679.8     0.1       0  4816.3   0.075       0  4964.6    0.05       0
  4994.8    0.05       0  4998.8    0.05       0  5102.6   0.075       0
Bank Sta=4994.8,4998.8
Exp/Cntr=0.3,0.1

Type RM Length L Ch R = 1,4708,366,366,366
BEGIN DESCRIPTION:
Stream HEN-1 5.0
END DESCRIPTION:
XS GIS Cut Line= 3
      2327529.00      7043360.01      2327529.00      7043260.00
      2327514.62      7042945.64
#Sta/Elev= 30
  4900.0  696.44  4910.0  696.66  4920.0  696.69  4930.0  695.87  4940.0  694.48
  4950.0  691.38  4960.0  689.86  4970.0  687.67  4978.0  684.10  4978.3  683.60
  4981.8  683.60  4982.0  684.10  4997.5  685.21  5002.5  685.21  5010.0  687.38
  5020.0  688.87  5030.0  689.52  5040.1  689.67  5050.1  689.64  5060.9  690.12
  5090.1  690.85  5107.3  690.96  5120.1  691.25  5130.1  691.13  5150.2  691.19
  5170.2  691.67  5210.2  691.90  5220.2  692.12  5290.3  692.60  5314.7  692.22
#Mann=4,-1,0
  4900.0    0.05       0  4978.0    0.05       0  4982.0    0.05       0
  5060.9   0.075       0
Bank Sta=4978,4982
Exp/Cntr=0.3,0.1

Type RM Length L Ch R = 1,4342,202,202,202
BEGIN DESCRIPTION:
Stream HEN-1 4.0
END DESCRIPTION:
XS GIS Cut Line= 3
      2327797.12      7043520.61      2327879.00      7043210.00
      2327779.02      7042910.05
#Sta/Elev= 30
  4679.3  692.06  4762.7  691.24  4781.5  692.13  4786.6  691.03  4804.0  691.83
  4826.9  691.15  4867.2  691.05  4897.1  692.77  4902.4  693.53  4907.5  692.29
  4917.8  692.84  4937.5  689.77  4942.7  690.15  4959.2  687.10  4977.8  682.60
  4983.0  682.80  4995.9  682.07  4996.2  681.57  4999.7  681.57  4999.9  682.07
  5011.1  682.49  5032.1  687.57  5074.3  687.11  5105.9  685.81  5127.0  686.85
  5221.9  688.29  5232.4  688.66  5243.0  689.67  5274.6  693.32  5316.7  693.83
#Mann=3,-1,0
  4679.3    0.05       0  4995.9   0.033       0  4999.9    0.05       0
Bank Sta=4995.9,4999.9
Exp/Cntr=0.3,0.1

Type RM Length L Ch R = 1,4140,436,436,436
BEGIN DESCRIPTION:
Stream HEN-1 3.0
END DESCRIPTION:
XS GIS Cut Line= 3
      2328079.62      7043380.40      2328079.62      7043131.94
      2327815.75      7042696.63
#Sta/Elev= 30
  4809.8  689.24  4940.2  687.70  4960.2  686.61  4970.2  684.36  4980.2  683.46
  5008.2  682.11  5008.5  681.61  5012.0  681.61  5012.2  682.11  5030.2  684.19
  5040.2  686.10  5056.7  687.19  5073.6  687.28  5095.6  686.61  5141.4  686.59
  5147.3  687.88  5162.7  688.46  5168.6  690.02  5199.6  689.09  5205.4  688.41
  5220.9  688.26  5242.3  688.79  5257.7  688.62  5263.6  687.98  5306.3  687.75
  5337.3  688.96  5343.1  689.72  5379.9  692.56  5401.3  693.25  5567.3  694.19
#Mann=3,-1,0
  4809.8    0.05       0  5008.2   0.033       0  5012.2    0.05       0
Bank Sta=5008.2,5012.2
Exp/Cntr=0.3,0.1

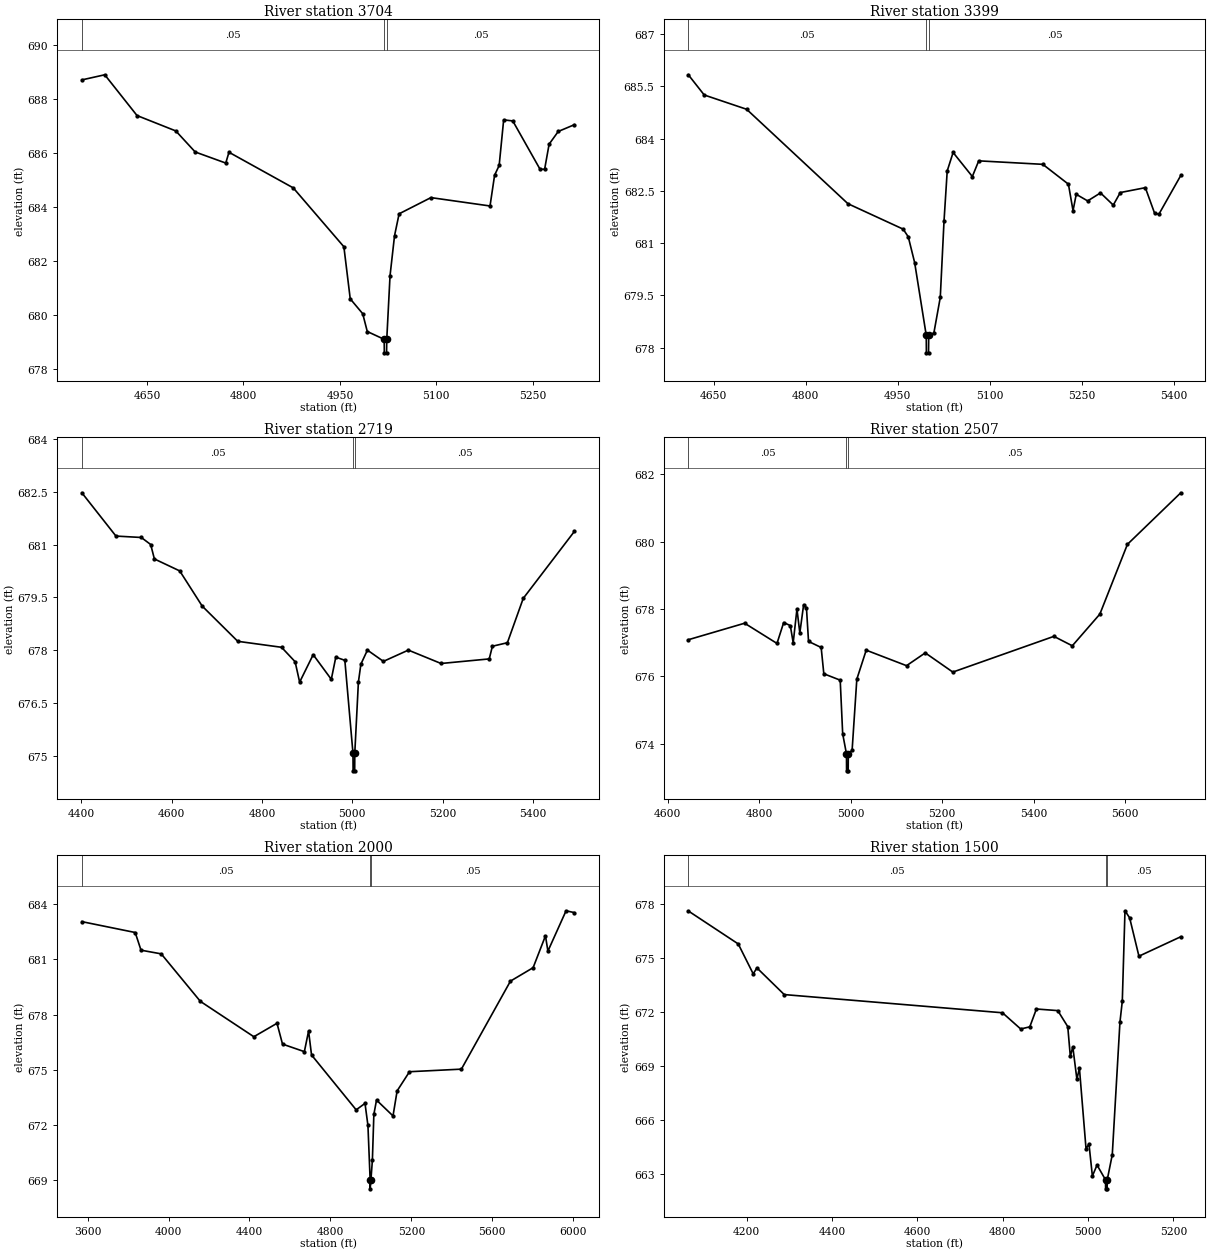
Type RM Length L Ch R = 1,3704,305,305,305
BEGIN DESCRIPTION:
Stream HEN-1 2.0
END DESCRIPTION:
XS GIS Cut Line= 3
      2328316.69      7043245.40      2328274.28      7042825.15
      2328031.38      7042582.25
#Sta/Elev= 30
  4548.7  688.71  4584.3  688.90  4634.5  687.39  4694.8  686.82  4725.0  686.04
  4772.5  685.63  4777.5  686.03  4877.5  684.71  4956.2  682.53  4966.1  680.60
  4985.5  680.05  4992.6  679.39  5018.9  679.10  5019.1  678.60  5022.6  678.60
  5022.9  679.10  5028.0  681.46  5035.0  682.94  5042.1  683.75  5091.6  684.35
  5183.5  684.04  5190.6  685.18  5197.7  685.54  5204.7  687.23  5218.9  687.19
  5261.3  685.40  5268.4  685.40  5275.4  686.33  5289.6  686.80  5314.6  687.05
#Mann=3,-1,0
  4548.7    0.05       0  5018.9    0.04       0  5022.9    0.05       0
Bank Sta=5018.9,5022.9
Exp/Cntr=0.3,0.1

Type RM Length L Ch R = 1,3399,680,680,680
BEGIN DESCRIPTION:
Stream HEN-1 1.5
END DESCRIPTION:
XS GIS Cut Line= 4
      2328382.25      7043006.35      2328524.91      7042694.05
      2328413.09      7042316.19      2328359.08      7042281.47
#Sta/Elev= 30
  4609.0  685.83  4634.9  685.25  4703.9  684.84  4868.8  682.13  4958.7  681.40
  4967.0  681.18  4977.4  680.44  4996.3  678.35  4996.5  677.85  5000.0  677.85
  5000.3  678.35  5008.7  678.42  5019.1  679.44  5025.2  681.63  5030.4  683.07
  5040.0  683.60  5071.3  682.91  5081.7  683.36  5186.0  683.26  5227.7  682.69
  5235.2  681.93  5240.4  682.40  5259.0  682.21  5279.9  682.44  5300.7  682.09
  5312.1  682.45  5352.9  682.59  5368.1  681.85  5375.0  681.83  5410.6  682.94
#Mann=3,-1,0
  4609.0    0.05       0  4996.3   0.033       0  5000.3    0.05       0
Bank Sta=4996.3,5000.3
Exp/Cntr=0.3,0.1

Type RM Length L Ch R = 1,2719,212,212,212
BEGIN DESCRIPTION:
Stream HEN-1 1.0
END DESCRIPTION:
XS GIS Cut Line= 4
      2328644.43      7042740.33      2328883.49      7042431.86
      2328871.92      7042154.25      2328463.64      7042046.40
#Sta/Elev= 30
  4401.4  682.47  4476.9  681.24  4533.0  681.20  4553.8  681.00  4562.0  680.59
  4618.1  680.25  4667.9  679.25  4746.6  678.25  4843.6  678.08  4873.6  677.67
  4883.6  677.09  4913.6  677.87  4953.7  677.17  4963.7  677.80  4983.7  677.71
  5001.7  675.07  5002.0  674.57  5005.5  674.57  5005.7  675.07  5013.7  677.09
  5019.2  677.60  5033.7  678.00  5069.1  677.68  5124.3  678.00  5196.7  677.62
  5303.4  677.75  5310.4  678.11  5343.6  678.21  5378.7  679.47  5491.8  681.37
#Mann=3,-1,0
  4401.4    0.05       0  5001.7    0.04       0  5005.7    0.05       0
Bank Sta=5001.7,5005.7
Exp/Cntr=0.3,0.1

Type RM Length L Ch R = 1,2507,507,507,507
BEGIN DESCRIPTION:
Stream HEN-1 0.5
END DESCRIPTION:
XS GIS Cut Line= 4
      2328937.50      7042470.39      2329099.41      7042258.35
      2329049.29      7042054.00      2328452.78      7042003.97
#Sta/Elev= 30
  4645.3  677.09  4768.3  677.58  4839.0  676.98  4853.6  677.60  4868.1  677.51
  4874.4  677.00  4882.6  678.00  4888.9  677.29  4897.2  678.13  4903.4  678.03
  4907.9  677.04  4935.5  676.86  4941.3  676.08  4977.1  675.89  4982.5  674.30
  4990.8  673.70  4991.0  673.20  4994.5  673.20  4994.8  673.70  5003.1  673.81
  5013.4  675.92  5033.9  676.78  5122.0  676.32  5162.9  676.70  5223.1  676.13
  5443.9  677.19  5484.1  676.91  5544.3  677.85  5604.5  679.92  5721.1  681.45
#Mann=3,-1,0
  4645.3    0.05       0  4990.8    0.04       0  4994.8    0.05       0
Bank Sta=4990.8,4994.8
Exp/Cntr=0.3,0.1

Type RM Length L Ch R = 1,2000,500,500,500
BEGIN DESCRIPTION:
Unnamed Tr to Walnut Cr 2C 4.0
END DESCRIPTION:
XS GIS Cut Line= 3
      2330179.02      7042910.02      2329316.19      7041771.91
      2328328.95      7041960.01
#Sta/Elev= 30
  3571.8  683.05  3835.4  682.46  3864.1  681.50  3964.0  681.30  4157.4  678.72
  4421.6  676.80  4536.0  677.53  4563.2  676.40  4671.2  675.99  4692.0  677.11
  4706.6  675.81  4927.1  672.83  4970.8  673.18  4985.3  671.98  4996.1  669.04
  4996.3  668.54  5000.1  669.04  5007.3  670.10  5014.5  672.58  5027.7  673.36
  5109.1  672.50  5129.5  673.86  5190.6  674.90  5447.0  675.04  5689.4  679.82
  5801.4  680.55  5862.4  682.28  5874.5  681.45  5964.2  683.64  6005.0  683.54
#Mann=3,-1,0
  3571.8    0.05       0  4996.1    0.05       0  5000.1    0.05       0
Bank Sta=4996.1,5000.1
Exp/Cntr=0.3,0.1

Type RM Length L Ch R = 1,1500,500,500,500
BEGIN DESCRIPTION:
Unnamed Tr to Walnut Cr 2C 3.0
END DESCRIPTION:
XS GIS Cut Line= 3
      2330128.97      7041809.98      2329328.21      7041323.40
      2329129.02      7041409.99
#Sta/Elev= 30
  4063.0  677.61  4180.0  675.78  4215.1  674.12  4223.8  674.45  4287.8  672.97
  4799.3  671.96  4842.0  671.06  4863.3  671.18  4878.8  672.17  4928.9  672.08
  4952.3  671.19  4958.3  669.54  4964.1  670.07  4973.7  668.27  4979.6  668.89
  4995.1  664.41  5002.0  664.68  5010.0  662.90  5020.9  663.51  5040.8  662.69
  5041.0  662.19  5044.5  662.19  5044.8  662.69  5056.6  664.08  5074.6  671.44
  5080.1  672.60  5086.4  677.62  5097.3  677.23  5119.1  675.10  5217.2  676.18
#Mann=3,-1,0
  4063.0    0.05       0  5040.8    0.05       0  5044.8    0.05       0
Bank Sta=5040.8,5044.8
Exp/Cntr=0.3,0.1

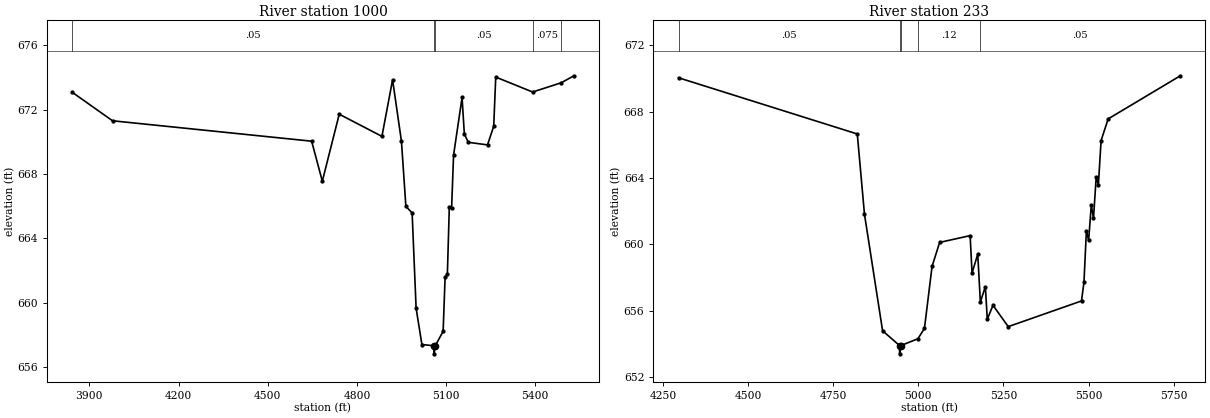
Type RM Length L Ch R = 1,1000,767,767,767
BEGIN DESCRIPTION:
Unnamed Tr to Walnut Cr 2C 2.0
END DESCRIPTION:
XS GIS Cut Line= 3
      2330179.03      7041510.02      2329222.68      7040856.71
      2328878.98      7041260.03
#Sta/Elev= 30
  3841.8  673.09  3978.0  671.31  4647.8  670.04  4683.7  667.55  4740.6  671.72
  4884.2  670.34  4920.1  673.86  4949.9  670.03  4964.8  665.98  4985.8  665.58
  4999.2  659.65  5018.7  657.39  5059.5  657.31  5059.8  656.81  5063.5  657.31
  5090.1  658.21  5096.7  661.56  5104.4  661.77  5110.9  665.94  5118.7  665.90
  5125.2  669.17  5153.8  672.76  5161.5  670.48  5175.1  669.97  5239.4  669.81
  5260.3  670.97  5267.1  674.03  5391.2  673.10  5488.1  673.68  5529.9  674.11
#Mann=5,-1,0
  3841.8    0.05       0  5059.5    0.05       0  5063.5    0.05       0
  5391.2   0.075       0  5488.1     0.1       0
Bank Sta=5059.5,5063.5
Exp/Cntr=0.3,0.1

Type RM Length L Ch R = 1,233,0,0,0
BEGIN DESCRIPTION:
Unnamed Tr to Walnut Cr 2C 1.0
END DESCRIPTION:
XS GIS Cut Line= 4
      2329728.52      7040945.96      2329508.84      7040311.81
      2329060.38      7040536.04      2328870.15      7040769.29
#Sta/Elev= 30
  4295.8  670.04  4820.7  666.65  4841.8  661.81  4895.0  654.78  4944.8  653.89
  4945.0  653.39  4948.8  653.89  4998.7  654.30  5017.9  654.92  5040.3  658.67
  5062.6  660.11  5152.1  660.52  5157.7  658.26  5174.4  659.40  5182.1  656.52
  5196.8  657.44  5202.4  655.47  5219.2  656.32  5263.9  655.03  5479.1  656.58
  5486.3  657.70  5493.5  660.81  5500.0  660.23  5507.9  662.37  5514.3  661.56
  5522.2  664.04  5528.7  663.59  5536.6  666.25  5557.4  667.56  5769.3  670.16
#Mann=5,-1,0
  4295.8    0.05       0  4944.8    0.07       0  4948.8    0.05       0
  4998.7    0.12       0  5182.1    0.05       0
Bank Sta=4944.8,4948.8
Exp/Cntr=0.3,0.1

Chan Stop Cuts=-1