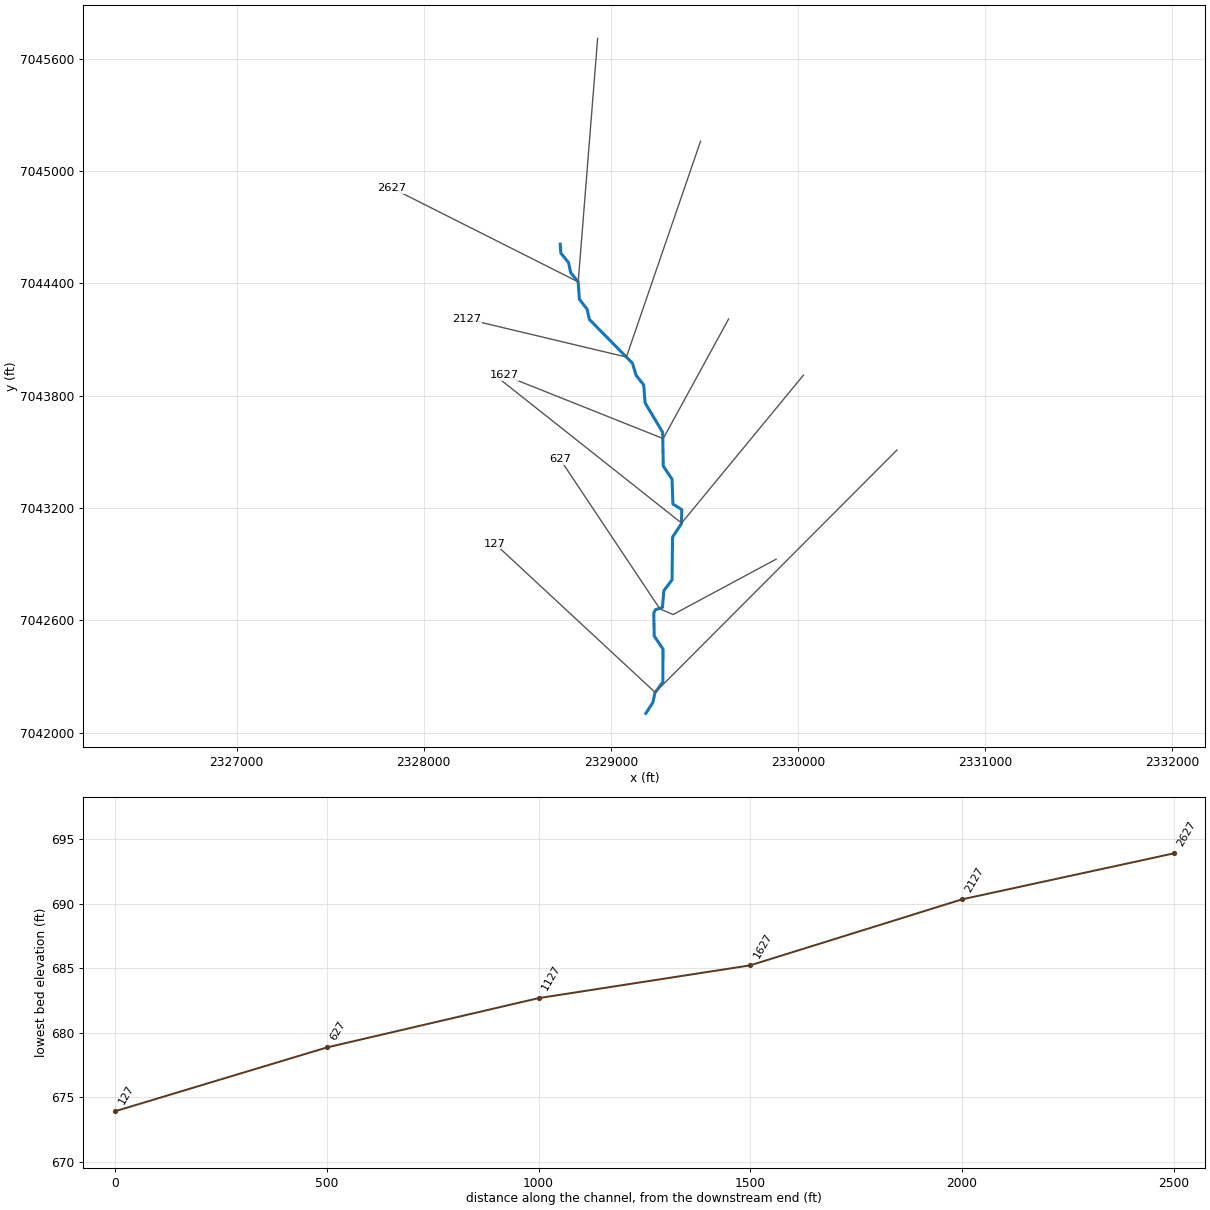
--- Stream HEN-1a.prj (project) ---

Proj Title=Stream HEN-1a Base Level Engineering
Current Plan=p01
Default Exp/Contr=0.3,0.1
English Units
Geom File=g01
Flow File=f01
Plan File=p01
BEGIN DESCRIPTION:
Stream HEN-1a
END DESCRIPTION:

--- Stream HEN-1a.p01 (plan) ---

Plan Title=Multiple Run
Short Identifier=Multiple
Geom File=g01
Flow File=f01
Subcritical Flow
K Sum by GR= 0
Std Step Tol= 0.01
Critical Tol= 0.01
Num of Std Step Trials= 20
Max Error Tol= 0.3
Flow Tol Ratio= 0.001
Split Flow NTrial= 30
Split Flow Tol= 0.02
Split Flow Ratio= 0.02
Log Output Level= 0
Friction Slope Method= 1
Unsteady Friction Slope Method= 2
Unsteady Bridges Friction Slope Method= 1
Parabolic Critical Depth
Global Vel Dist=  1 , 1 , 1
Global Log Level= 0
CheckData=True
Encroach Param= -1, 0, 0, 0
BEGIN DESCRIPTION:
Multiple Run
END DESCRIPTION:

--- Stream HEN-1a.f01 (steady flow) ---

Flow Title=Multiple
Number of Profiles=7
Profile Names=10-year,25-year,50-year,1pct_min,100-year,1pct_plu,500-year
River Rch & RM= Stream HEN-1a,Reach-1,2627
     424     562     672     399     795    1590    1110
Boundary for River Rch & Prof#=Stream HEN-1a,Reach-1,1
Up Type=0
Dn Type=3
Dn Slope=0.005
Boundary for River Rch & Prof#=Stream HEN-1a,Reach-1,2
Up Type=0
Dn Type=3
Dn Slope=0.005
Boundary for River Rch & Prof#=Stream HEN-1a,Reach-1,3
Up Type=0
Dn Type=3
Dn Slope=0.005
Boundary for River Rch & Prof#=Stream HEN-1a,Reach-1,4
Up Type=0
Dn Type=3
Dn Slope=0.005
Boundary for River Rch & Prof#=Stream HEN-1a,Reach-1,5
Up Type=0
Dn Type=3
Dn Slope=0.005
Boundary for River Rch & Prof#=Stream HEN-1a,Reach-1,6
Up Type=0
Dn Type=3
Dn Slope=0.005
Boundary for River Rch & Prof#=Stream HEN-1a,Reach-1,7
Up Type=0
Dn Type=3
Dn Slope=0.005

--- Stream HEN-1a.g01 (geometry) ---

Geom Title=Existing Conditions

River Reach=Stream HEN-1a,Reach-1
Reach XY= 30
      2328729.00      7044610.00      2328732.60      7044561.49
      2328773.05      7044512.25      2328785.10      7044457.81
      2328825.18      7044408.42      2328831.44      7044315.56
      2328872.86      7044262.17      2328884.83      7044207.70
      2329115.38      7043973.22      2329135.14      7043907.83
      2329175.17      7043858.42      2329182.83      7043761.58
      2329276.65      7043604.48      2329279.69      7043423.92
      2329326.61      7043354.46      2329331.22      7043221.29
      2329378.65      7043191.25      2329376.86      7043116.06
      2329329.52      7043044.79      2329326.62      7042815.53
      2329282.88      7042758.33      2329275.28      7042668.21
      2329237.57      7042656.42      2329229.02      7042637.22
      2329231.37      7042515.54      2329278.32      7042446.08
      2329277.64      7042269.65      2329235.09      7042212.17
      2329224.58      7042161.64      2329186.80      7042102.31

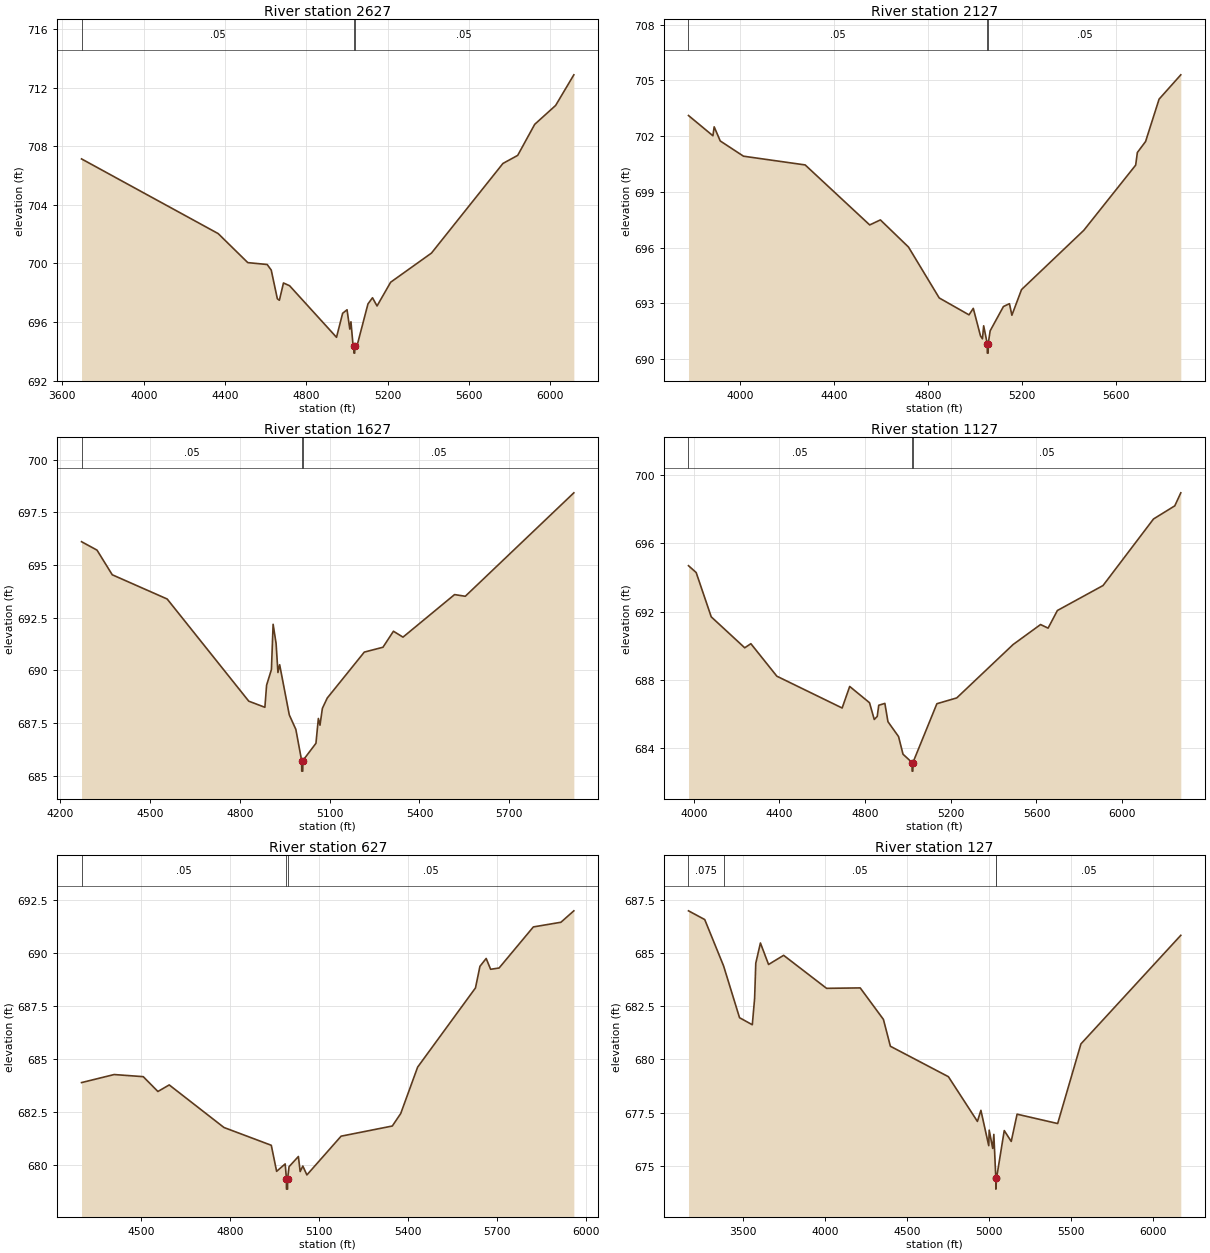
Type RM Length L Ch R = 1,2627,500,500,500
BEGIN DESCRIPTION:
Unnamed Tr to Walnut Cr 2C 10.0
END DESCRIPTION:
XS GIS Cut Line= 3
      2328929.00      7045709.97      2328825.18      7044408.40
      2327829.03      7044909.98
#Sta/Elev= 30
  3694.3  707.14  4366.4  702.04  4511.8  700.06  4607.2  699.93  4627.2  699.55
  4657.3  697.59  4667.3  697.49  4687.4  698.67  4717.5  698.48  4948.2  694.96
  4978.3  696.60  5000.0  696.84  5013.6  695.52  5019.2  696.02  5029.3  694.45
  5033.9  694.38  5034.2  693.88  5037.7  693.88  5037.9  694.38  5051.7  694.52
  5102.9  697.24  5125.2  697.66  5147.5  697.10  5214.4  698.72  5415.2  700.71
  5766.7  706.83  5839.2  707.38  5922.9  709.50  6025.8  710.79  6115.3  712.88
#Mann=3,-1,0
  3694.3    0.05       0  5033.9   0.033       0  5037.9    0.05       0
Bank Sta=5033.9,5037.9
Exp/Cntr=0.3,0.1

Type RM Length L Ch R = 1,2127,500,500,500
BEGIN DESCRIPTION:
Unnamed Tr to Walnut Cr 2C 9.0
END DESCRIPTION:
XS GIS Cut Line= 3
      2329479.00      7045160.01      2329082.67      7044006.71
      2328229.04      7044209.99
#Sta/Elev= 30
  3780.5  703.11  3884.6  702.02  3889.9  702.50  3915.8  701.74  4014.8  700.92
  4277.5  700.45  4552.4  697.22  4597.9  697.49  4717.6  696.03  4848.5  693.29
  4975.4  692.38  4993.6  692.73  5024.3  691.25  5032.6  691.09  5037.8  691.79
  5053.2  690.82  5053.4  690.32  5056.9  690.32  5057.2  690.82  5065.4  691.52
  5122.1  692.83  5147.7  692.98  5158.0  692.36  5199.1  693.74  5464.3  696.93
  5685.3  700.44  5692.5  701.12  5727.5  701.71  5785.0  703.99  5877.5  705.30
#Mann=3,-1,0
  3780.5    0.05       0  5053.2   0.033       0  5057.2    0.05       0
Bank Sta=5053.2,5057.2
Exp/Cntr=0.3,0.1

Type RM Length L Ch R = 1,1627,500,500,500
BEGIN DESCRIPTION:
Unnamed Tr to Walnut Cr 2C 8.0
END DESCRIPTION:
XS GIS Cut Line= 3
      2329629.00      7044210.00      2329279.42      7043570.86
      2328429.04      7043909.98
#Sta/Elev= 30
  4271.5  696.10  4323.2  695.70  4374.1  694.53  4557.5  693.38  4830.0  688.53
  4883.8  688.24  4889.5  689.29  4905.6  690.03  4911.3  692.18  4921.2  691.27
  4927.4  689.89  4933.1  690.26  4965.3  687.88  4987.2  687.19  5006.5  685.71
  5006.8  685.21  5010.3  685.21  5010.5  685.71  5054.3  686.53  5062.4  687.71
  5067.8  687.39  5075.8  688.19  5092.1  688.68  5215.8  690.86  5278.1  691.09
  5313.1  691.85  5345.0  691.57  5517.2  693.59  5553.0  693.51  5915.5  698.42
#Mann=3,-1,0
  4271.5    0.05       0  5006.5   0.033       0  5010.5    0.05       0
Bank Sta=5006.5,5010.5
Exp/Cntr=0.3,0.1

Type RM Length L Ch R = 1,1127,500,500,500
BEGIN DESCRIPTION:
Unnamed Tr to Walnut Cr 2C 7.0
END DESCRIPTION:
XS GIS Cut Line= 3
      2330029.00      7043910.01      2329377.63      7043119.37
      2328379.02      7043909.99
#Sta/Elev= 30
  3975.6  694.68  4011.5  694.28  4081.8  691.69  4238.2  689.88  4266.8  690.12
  4388.1  688.22  4692.9  686.36  4728.1  687.62  4820.6  686.67  4842.8  685.69
  4856.7  685.87  4863.7  686.52  4892.3  686.63  4906.7  685.56  4956.2  684.69
  4977.0  683.66  5019.3  683.17  5019.5  682.67  5023.0  682.67  5023.3  683.17
  5135.1  686.61  5227.8  686.95  5490.8  690.07  5619.1  691.24  5654.3  691.03
  5697.6  692.06  5910.7  693.52  6146.2  697.41  6245.7  698.18  6273.7  698.94
#Mann=3,-1,0
  3975.6    0.05       0  5019.3    0.04       0  5023.3    0.05       0
Bank Sta=5019.3,5023.3
Exp/Cntr=0.3,0.1

Type RM Length L Ch R = 1,627,500,500,500
BEGIN DESCRIPTION:
Unnamed Tr to Walnut Cr 2C 6.0
END DESCRIPTION:
XS GIS Cut Line= 4
      2329882.70      7042926.21      2329331.93      7042630.42
      2329261.36      7042661.03      2328728.99      7043460.02
#Sta/Elev= 30
  4297.9  683.88  4408.0  684.26  4506.3  684.16  4555.8  683.46  4594.0  683.77
  4778.8  681.76  4938.6  680.92  4956.6  679.69  4985.5  680.04  4989.7  679.35
  4989.9  678.85  4993.4  678.85  4993.7  679.35  4998.6  679.91  5030.1  680.39
  5036.1  679.68  5045.1  679.94  5058.8  679.52  5174.3  681.35  5347.2  681.83
  5375.6  682.42  5432.7  684.61  5628.0  688.35  5643.1  689.37  5664.1  689.74
  5679.1  689.23  5707.7  689.29  5823.4  691.23  5916.5  691.45  5960.1  691.99
#Mann=3,-1,0
  4297.9    0.05       0  4989.7   0.033       0  4993.7    0.05       0
Bank Sta=4989.7,4993.7
Exp/Cntr=0.3,0.1

Type RM Length L Ch R = 1,127,0,0,0
BEGIN DESCRIPTION:
Unnamed Tr to Walnut Cr 2C 5.0
END DESCRIPTION:
XS GIS Cut Line= 3
      2330528.99      7043509.99      2329236.42      7042214.27
      2328378.97      7043010.03
#Sta/Elev= 30
  3169.8  686.98  3268.8  686.57  3383.8  684.39  3480.9  681.96  3558.7  681.63
  3572.8  682.87  3579.9  684.52  3608.2  685.47  3657.7  684.46  3749.6  684.89
  4011.2  683.34  4216.3  683.36  4357.7  681.88  4400.1  680.62  4753.7  679.19
  4930.5  677.09  4951.7  677.61  4999.5  675.95  5002.2  676.68  5023.7  675.82
  5030.5  676.48  5042.7  674.41  5042.9  673.91  5046.7  674.41  5094.0  676.66
  5136.5  676.15  5172.2  677.43  5419.5  676.99  5561.2  680.73  6169.8  685.83
#Mann=4,-1,0
  3169.8   0.075       0  3383.8    0.05       0  5042.7    0.04       0
  5046.7    0.05       0
Bank Sta=5042.7,5046.7
Exp/Cntr=0.3,0.1

Chan Stop Cuts=-1