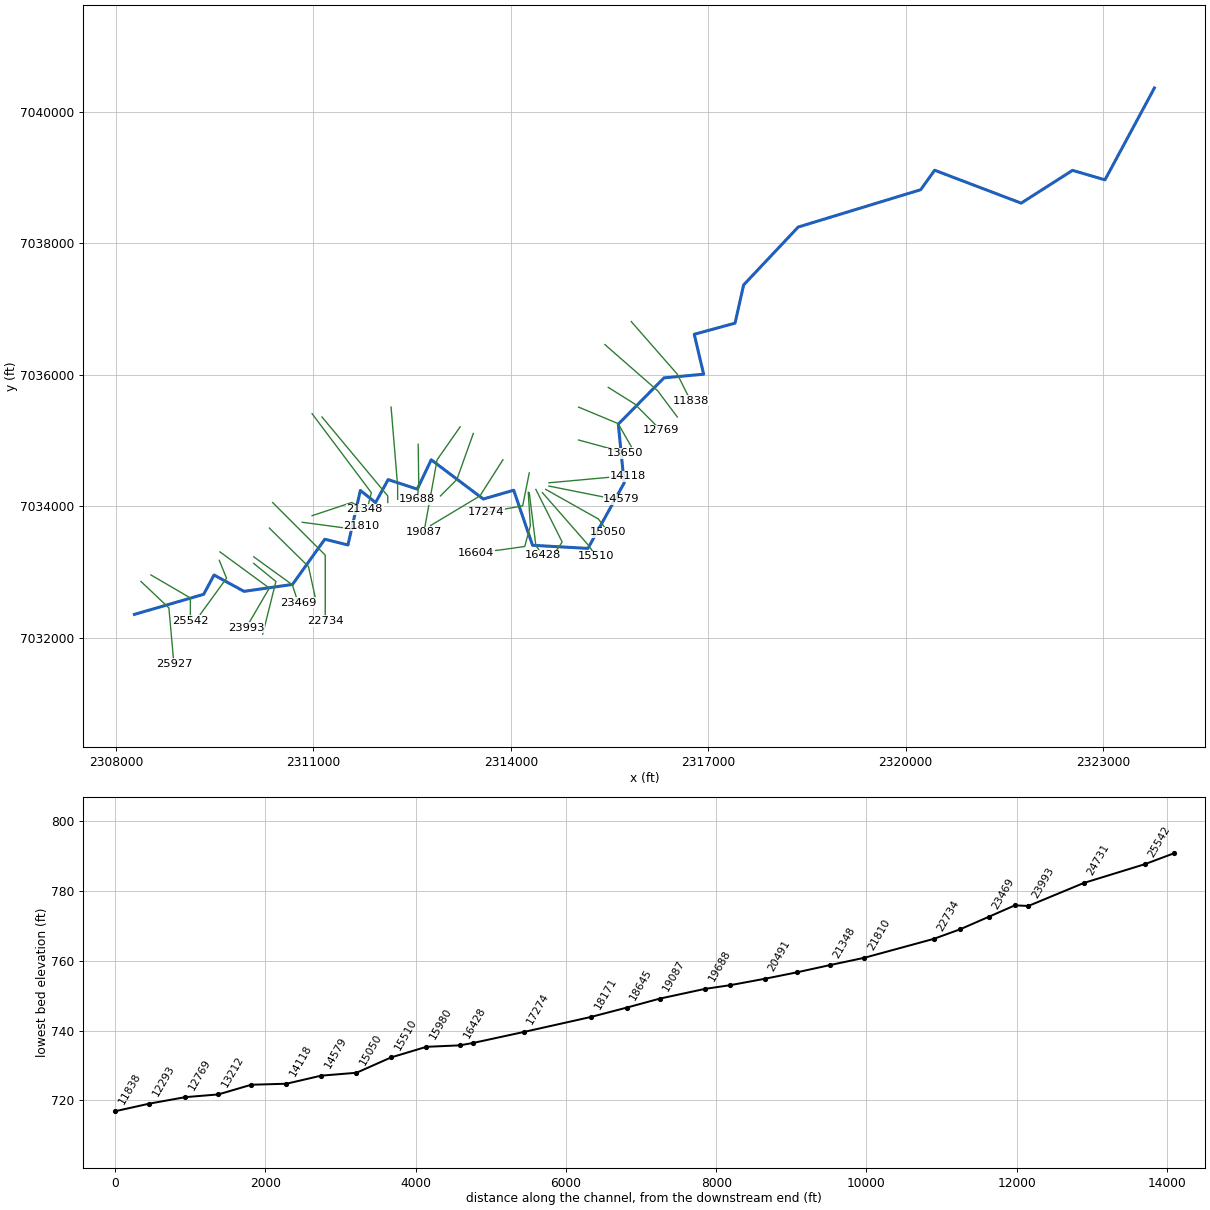
--- Stream HEN-2.prj (project) ---

Proj Title=Stream HEN-2 Base Level Engineering
Current Plan=p01
Default Exp/Contr=0.3,0.1
English Units
Geom File=g01
Flow File=f01
Plan File=p01
Y Axis Title=Elevation
X Axis Title(PF)=Main Channel Distance
X Axis Title(XS)=Station
BEGIN DESCRIPTION:
Stream HEN-2
END DESCRIPTION:
DSS File=dss
DSS Export Rating Curves= 0
DSS Export Rating Curve Sorted= 0
DSS Export Volume Flow Curves= 0
DXF OffsetX= 0
DXF OffsetY= 0
DXF ScaleX= 1
DXF ScaleY= 10

--- Stream HEN-2.p01 (plan) ---

Plan Title=Multiple Run
Program Version=4.10
Geom File=g01
Flow File=f01
Subcritical Flow
K Sum by GR= 0
Std Step Tol= 0.01
Critical Tol= 0.01
Num of Std Step Trials= 20
Max Error Tol= 0.3
Flow Tol Ratio= 0.001
Split Flow NTrial= 30
Split Flow Tol= 0.02
Split Flow Ratio= 0.02
Log Output Level= 0
Friction Slope Method= 0
Unsteady Friction Slope Method= 2
Unsteady Bridges Friction Slope Method= 1
Parabolic Critical Depth
Global Vel Dist= 1 , 1 , 1
Global Log Level= 0
CheckData=True
Encroach Param=-1 ,0,0, 0
BEGIN DESCRIPTION:
Multiple Run
END DESCRIPTION:
Computation Interval=1HOUR
Output Interval=1HOUR
Run HTab= 0
Run UNet= 0
Run PostProcess= 0
Run WQNet= 0
UNET Theta= 1
UNET Theta Warmup= 1
UNET ZTol= 0.02
UNET ZSATol= 0.05
UNET MxIter= 20
UNET MaxInSteps= 0
UNET DtIC= 0
UNET DtMin= 0
UNET MaxCRTS= 20
UNET WFStab= 2
UNET SFStab= 1
UNET WFX= 1
UNET SFX= 1
UNET DSS MLevel= 4
UNET DZMax Abort= 100
UNET Convert EG Bridges= 0
UNET Use Existing IB Tables=-1
UNET Froude Reduction=False
UNET Froude Limit= 1
UNET Froude Power= 10
UNET Time Slicing=0,0, 5
UNET Junction Losses=0
Instantaneous Interval=1HOUR
DSS File=dss
Write IC File= 0
Write IC File at Sim End=0
Echo Input=False
Echo Parameters=False
Echo Output=False
Write Detailed= 0
WQ AD Non Conservative
WQ ULTIMATE=-1
WQ Max Comp Step=1HOUR
WQ Output Interval=15MIN
WQ Output Selected Increments= 0
WQ Output face flow=0
WQ Output face velocity=0
WQ Output face area=0
WQ Output face dispersion=0
WQ Output cell volume=0
WQ Output cell surface area=0
WQ Output cell continuity=0
WQ Output cumulative cell continuity=0
WQ Output face conc=0
WQ Output face dconc_dx=0
WQ Output face courant=0
WQ Output face peclet=0
WQ Output face adv mass=0
WQ Output face disp mass=0
WQ Output cell mass=0
WQ Output cell source sink temp=0
WQ Output cell source sink nsm=0
WQ Output MaxMinRange=-1
WQ Daily Max Min Mean=-1
WQ Daily Range=0
WQ Daily Time=0
WQ Create Restart=0
WQ Fixed Restart=0
WQ System Summary=0
WQ Use Fixed Temperature=0
Sorting and Armoring Iterations= 10
XS Update Threshold= 0.02
Hydraulics Update Threshold= 0.02
Energy Slope Method= 1
Volume Change Method= 0
XS Weighting Method= 0
Number of US Weighted Cross Sections= 1
Number of DS Weighted Cross Sections= 1
Upstream XS Weight=0.25
Main XS Weight=0.5
Downstream XS Weight=0.25
Number of DS XS's Weighted with US Boundary= 1
Upstream Boundary Weight= 1
Weight of XSs Associated with US Boundary= 0
Number of US XS's Weighted with DS Boundary= 1
Downstream Boundary Weight= 0.5
Weight of XSs Associated with DS Boundary= 0.5
Sediment Output Level= 4
Mass or Volume Output= 0
Output Increment Type= 1
Profile and TS Output Increment= 10
XS Output Flag= 0
XS Output Increment= 10
Disregard all LS=0
Disregard all Conn=0
Disregard all Breaches=0
Disregard all Pumps=0

--- Stream HEN-2.f01 (steady flow) ---

Flow Title=Multiple
Number of Profiles=7
Profile Names=10-year,25-year,50-year,1pct_min,100-year,1pct_plu,500-year
River Rch & RM= Stream HEN-2,Reach-1,25927
     442     593     714     427     853    1700    1210
River Rch & RM= Stream HEN-2,Reach-1,23086
     753    1040    1270     771    1540    3070    2260
River Rch & RM= Stream HEN-2,Reach-1,22734
     909    1260    1560     950    1890    3780    2810
River Rch & RM= Stream HEN-2,Reach-1,16604
     962    1340    1660    1010    2020    4030    3000
River Rch & RM= Stream HEN-2,Reach-1,16428
    1640    2340    2940    1830    3640    7270    5590
River Rch & RM= Stream HEN-2,Reach-1,13212
    1700    2430    3060    1900    3790    7560    5820
River Rch & RM= Stream HEN-2,Reach-1,11404
    1760    2520    3180    1970    3930    7850    6050
River Rch & RM= Stream HEN-2,Reach-1,9623
    1800    2580    3240    2010    4010    8010    6170
River Rch & RM= Stream HEN-2,Reach-1,6839
    2520    3660    4640    2910    5800   11600    9060
River Rch & RM= Stream HEN-2,Reach-1,3948
    2950    4300    5490    3450    6880   13700   10800
River Rch & RM= Stream HEN-2,Reach-1,3453
    3010    4400    5610    3520    7030   14000   11100
River Rch & RM= Stream HEN-2,Reach-1,31
    5030    7490    9670    6150   12300   24500   19800
Boundary for River Rch & Prof#=Stream HEN-2,Reach-1,1
Up Type=0
Dn Type=3
Dn Slope=0.005
Boundary for River Rch & Prof#=Stream HEN-2,Reach-1,2
Up Type=0
Dn Type=3
Dn Slope=0.005
Boundary for River Rch & Prof#=Stream HEN-2,Reach-1,3
Up Type=0
Dn Type=3
Dn Slope=0.005
Boundary for River Rch & Prof#=Stream HEN-2,Reach-1,4
Up Type=0
Dn Type=3
Dn Slope=0.005
Boundary for River Rch & Prof#=Stream HEN-2,Reach-1,5
Up Type=0
Dn Type=3
Dn Slope=0.005
Boundary for River Rch & Prof#=Stream HEN-2,Reach-1,6
Up Type=0
Dn Type=3
Dn Slope=0.005
Boundary for River Rch & Prof#=Stream HEN-2,Reach-1,7
Up Type=0
Dn Type=3
Dn Slope=0.005

--- Stream HEN-2.g01 (geometry) ---

Geom Title=Existing Conditions

River Reach=Stream HEN-2,Reach-1
Reach XY= 30
      2308279.00      7032360.00      2309331.44      7032665.52
      2309489.11      7032958.97      2309944.22      7032710.25
      2310681.45      7032815.46      2311172.49      7033502.38
      2311523.96      7033414.93      2311712.25      7034243.60
      2311943.76      7034059.15      2312134.84      7034408.51
      2312577.52      7034263.45      2312789.31      7034709.14
      2313580.50      7034113.47      2314042.73      7034246.81
      2314329.00      7033410.00      2315170.70      7033363.06
      2315720.98      7034356.65      2315632.46      7035251.52
      2316326.53      7035954.54      2316929.00      7036010.00
      2316786.33      7036616.38      2317406.14      7036786.16
      2317536.67      7037366.52      2318365.78      7038246.38
      2320227.55      7038813.53      2320439.47      7039109.47
      2321753.89      7038609.72      2322534.93      7039107.77
      2323027.75      7038963.51      2323779.00      7040360.00

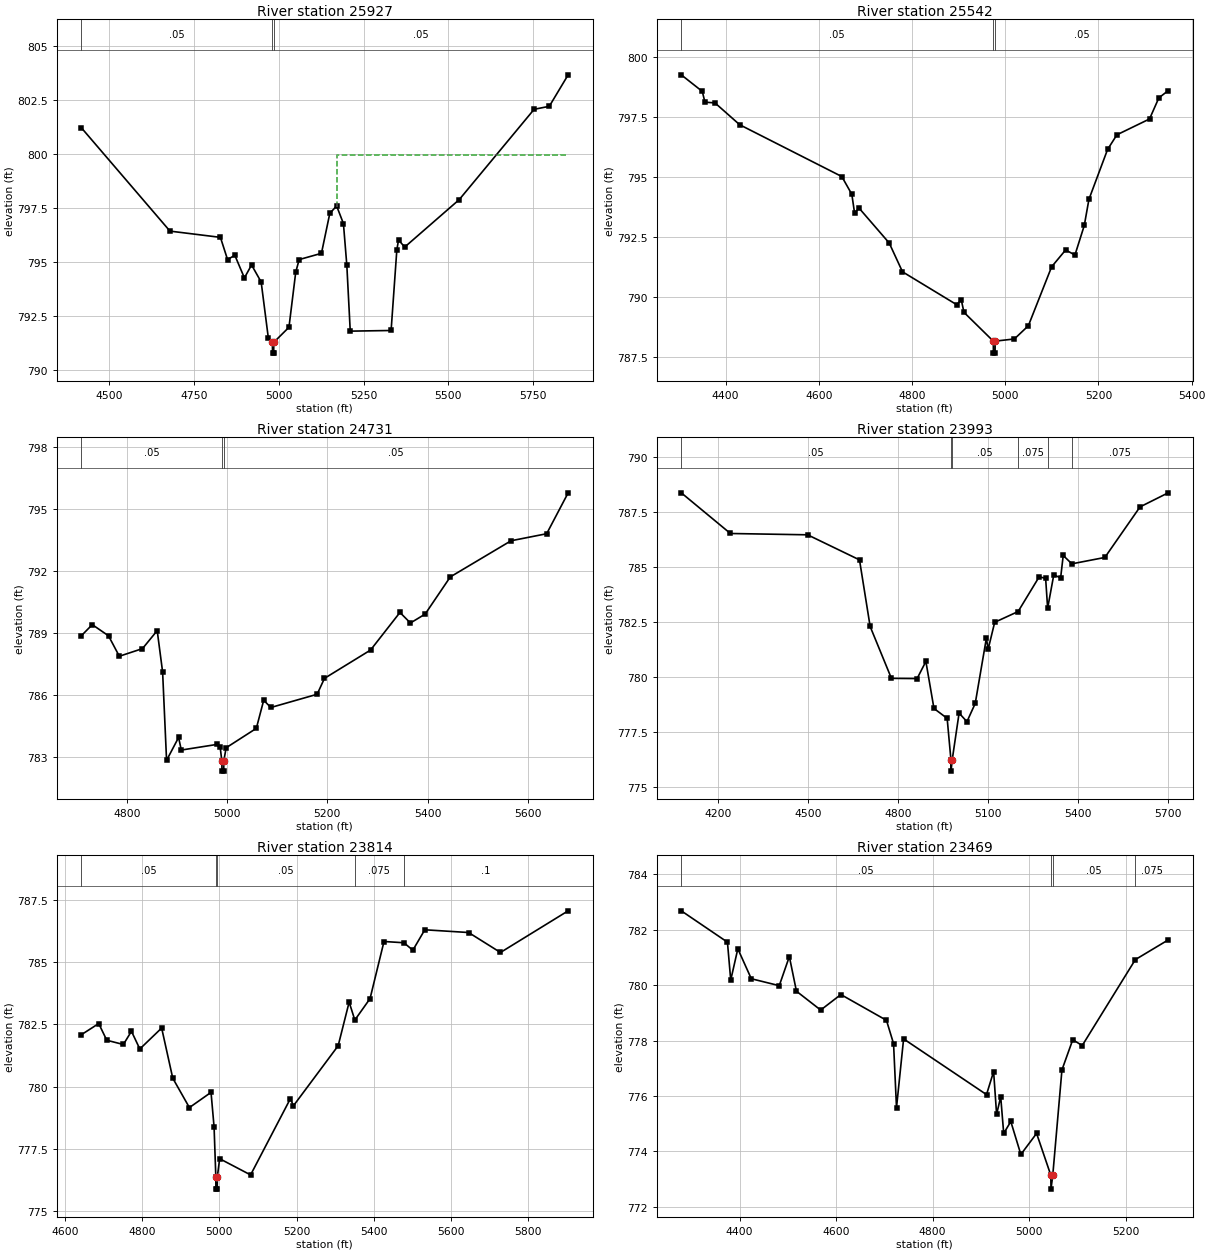
Type RM Length L Ch R = 1,25927,385,385,385
BEGIN DESCRIPTION:
Stream HEN-2 47.0
END DESCRIPTION:
XS GIS Cut Line= 3
      2308379.02      7032859.98      2308802.81      7032458.76
      2308879.00      7031609.96
#Sta/Elev= 30
  4417.7  801.23  4679.3  796.43  4828.1  796.14  4849.1  795.11  4870.5  795.31
  4898.8  794.26  4919.9  794.86  4948.2  794.07  4969.3  791.48  4981.4  791.27
  4981.7  790.77  4985.2  790.77  4985.4  791.27  5030.2  791.97  5050.2  794.53
  5060.3  795.11  5126.0  795.40  5150.6  797.25  5170.7  797.60  5190.8  796.78
  5200.8  794.85  5210.9  791.79  5331.4  791.82  5348.3  795.56  5353.3  796.02
  5371.5  795.69  5532.2  797.89  5753.1  802.08  5797.9  802.22  5853.5  803.68
#Mann=3,-1,0
  4417.7    0.05       0  4981.4    0.04       0  4985.4    0.05       0
#XS Ineff=2,0
       0                 5172.50    0.00  799.95
Permanent Ineff=
       F       F
Bank Sta=4981.4,4985.4
Exp/Cntr=0.3,0.1

Type RM Length L Ch R = 1,25542,811,811,811
BEGIN DESCRIPTION:
Stream HEN-2 46.0
END DESCRIPTION:
XS GIS Cut Line= 3
      2308529.02      7032959.99      2309129.00      7032610.00
      2309129.00      7032260.00
#Sta/Elev= 30
  4305.0  799.27  4350.0  798.58  4355.8  798.13  4377.3  798.10  4430.3  797.19
  4649.4  795.03  4670.9  794.29  4676.7  793.52  4686.6  793.71  4751.1  792.26
  4779.6  791.06  4895.8  789.69  4905.7  789.89  4911.5  789.37  4974.4  788.17
  4974.7  787.67  4978.2  787.67  4978.4  788.17  5019.6  788.26  5049.6  788.81
  5099.6  791.27  5129.6  791.97  5149.6  791.76  5169.6  792.99  5179.6  794.08
  5219.6  796.16  5239.6  796.77  5309.6  797.43  5329.6  798.31  5349.6  798.61
#Mann=3,-1,0
  4305.0    0.05       0  4974.4   0.033       0  4978.4    0.05       0
Bank Sta=4974.4,4978.4
Exp/Cntr=0.3,0.1

Type RM Length L Ch R = 1,24731,738,738,738
BEGIN DESCRIPTION:
Stream HEN-2 45.0
END DESCRIPTION:
XS GIS Cut Line= 3
      2309568.77      7033180.34      2309679.00      7032910.00
      2309279.01      7032360.02
#Sta/Elev= 30
  4708.7  788.85  4730.7  789.39  4763.1  788.85  4784.7  787.86  4830.9  788.23
  4860.3  789.10  4871.1  787.10  4879.0  782.82  4903.0  783.93  4908.4  783.32
  4979.0  783.59  4985.9  783.48  4989.3  782.80  4989.6  782.30  4993.1  782.30
  4993.3  782.80  4997.9  783.43  5058.2  784.37  5072.9  785.73  5087.2  785.38
  5179.6  786.02  5194.2  786.79  5286.2  788.16  5344.9  789.98  5365.8  789.47
  5395.2  789.90  5445.4  791.70  5566.7  793.45  5637.8  793.79  5680.7  795.77
#Mann=3,-1,0
  4708.7    0.05       0  4989.3   0.033       0  4993.3    0.05       0
Bank Sta=4989.3,4993.3
Exp/Cntr=0.3,0.1

Type RM Length L Ch R = 1,23993,179,179,179
BEGIN DESCRIPTION:
Stream HEN-2 44.0
END DESCRIPTION:
XS GIS Cut Line= 3
      2309579.00      7033310.00      2310329.00      7032760.00
      2309978.99      7032159.98
#Sta/Elev= 30
  4077.3  788.37  4241.3  786.52  4498.9  786.46  4672.0  785.32  4707.5  782.29
  4778.5  779.93  4864.2  779.92  4893.5  780.70  4920.5  778.56  4964.5  778.11
  4977.2  776.21  4977.4  775.71  4981.2  776.21  5004.3  778.35  5030.5  777.96
  5058.2  778.79  5095.4  781.76  5101.2  781.25  5123.1  782.48  5201.3  782.97
  5271.6  784.55  5293.1  784.48  5299.8  783.12  5320.3  784.64  5343.1  784.50
  5351.8  785.52  5380.6  785.14  5490.7  785.43  5608.1  787.73  5702.0  788.37
#Mann=6,-1,0
  4077.3    0.05       0  4977.2   0.033       0  4981.2    0.05       0
  5201.3   0.075       0  5299.8     0.1       0  5380.6   0.075       0
Bank Sta=4977.2,4981.2
Exp/Cntr=0.3,0.1

Type RM Length L Ch R = 1,23814,345,345,345
BEGIN DESCRIPTION:
Stream HEN-2 43.0
END DESCRIPTION:
XS GIS Cut Line= 3
      2310091.58      7033135.65      2310429.00      7032860.00
      2310229.01      7032060.02
#Sta/Elev= 30
  4642.6  782.08  4687.8  782.53  4708.6  781.86  4751.6  781.69  4772.5  782.22
  4794.2  781.51  4850.7  782.35  4879.4  780.34  4922.5  779.16  4978.5  779.77
  4986.4  778.38  4990.9  776.39  4991.1  775.89  4994.6  775.89  4994.9  776.39
  5000.8  777.11  5080.9  776.46  5184.0  779.52  5191.7  779.23  5307.6  781.64
  5336.0  783.39  5350.7  782.67  5390.1  783.53  5426.2  785.82  5477.8  785.77
  5500.9  785.47  5531.8  786.29  5645.2  786.18  5727.7  785.38  5902.9  787.05
#Mann=5,-1,0
  4642.6    0.05       0  4990.9    0.04       0  4994.9    0.05       0
  5350.7   0.075       0  5477.8     0.1       0
Bank Sta=4990.9,4994.9
Exp/Cntr=0.3,0.1

Type RM Length L Ch R = 1,23469,383,383,383
BEGIN DESCRIPTION:
Stream HEN-2 42.0
END DESCRIPTION:
XS GIS Cut Line= 3
      2310091.57      7033235.40      2310679.00      7032810.00
      2310765.70      7032540.59
#Sta/Elev= 30
  4279.4  782.68  4375.0  781.55  4381.8  780.18  4396.5  781.31  4424.4  780.23
  4482.3  779.98  4503.2  781.03  4517.9  779.78  4568.1  779.10  4609.9  779.66
  4704.3  778.73  4719.0  777.89  4725.1  775.58  4739.8  778.06  4911.5  776.05
  4926.2  776.88  4932.4  775.34  4940.9  775.97  4947.1  774.65  4961.8  775.08
  4982.6  773.89  5015.2  774.65  5044.7  773.14  5045.0  772.64  5048.7  773.14
  5067.7  776.94  5090.1  778.03  5109.7  777.82  5219.7  780.92  5287.7  781.63
#Mann=4,-1,0
  4279.4    0.05       0  5044.7   0.033       0  5048.7    0.05       0
  5219.7   0.075       0
Bank Sta=5044.7,5048.7
Exp/Cntr=0.3,0.1

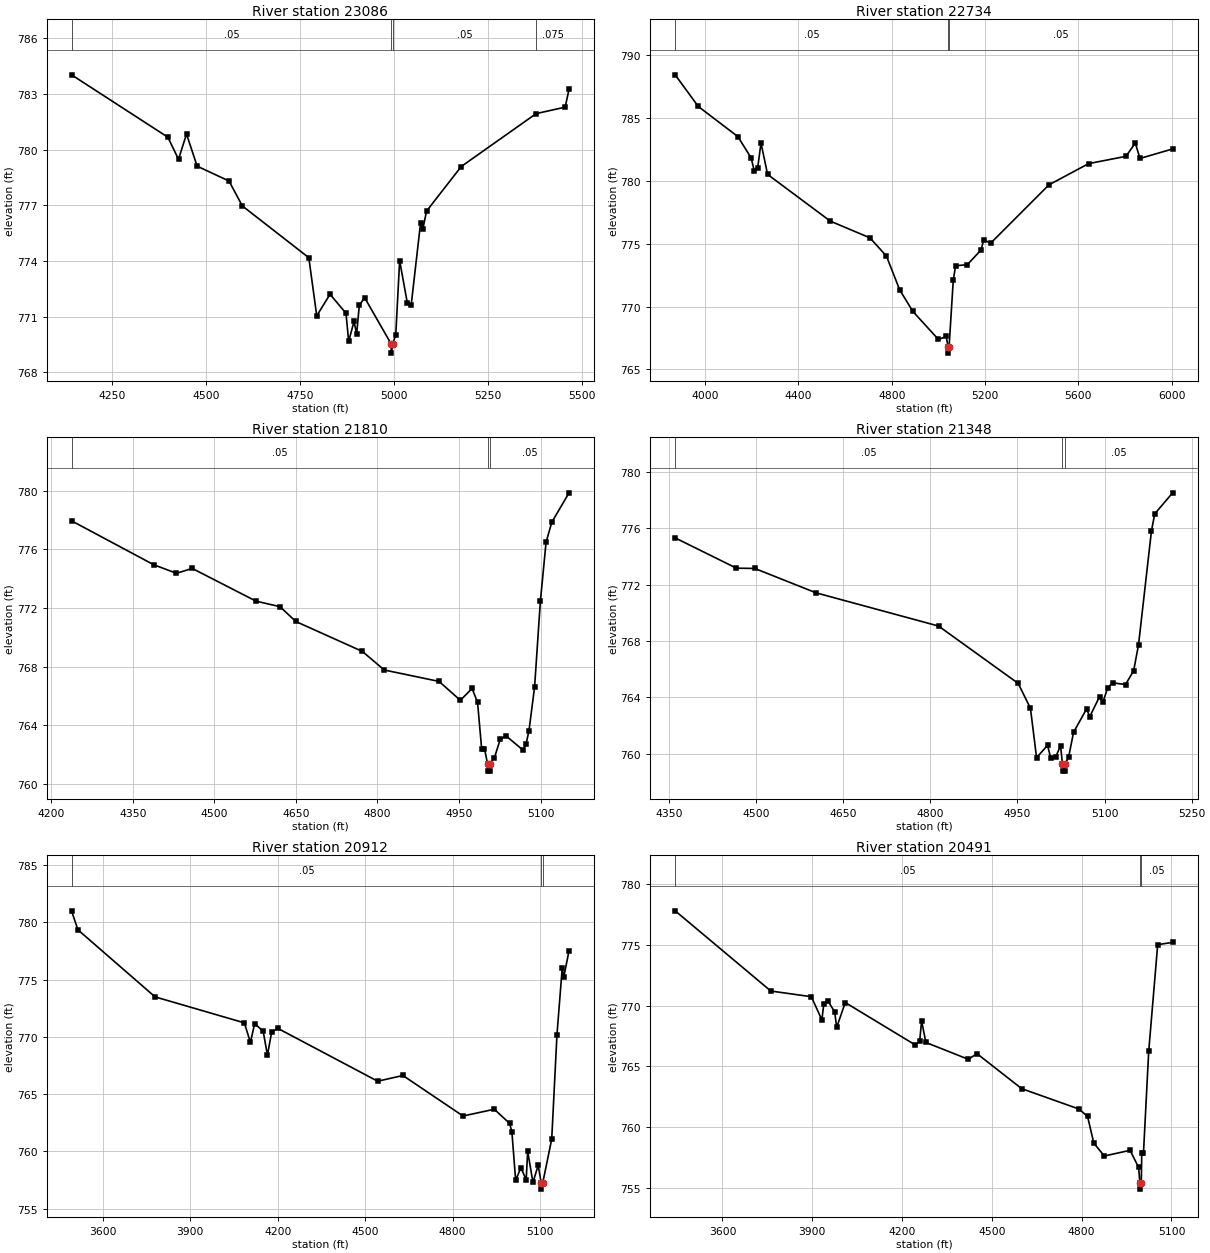
Type RM Length L Ch R = 1,23086,352,352,352
BEGIN DESCRIPTION:
Stream HEN-2 41.0
END DESCRIPTION:
XS GIS Cut Line= 3
      2310328.86      7033672.24      2310923.90      7033087.51
      2311029.00      7032610.00
#Sta/Elev= 30
  4141.4  784.03  4397.6  780.67  4425.9  779.48  4447.2  780.84  4475.5  779.11
  4560.3  778.31  4595.6  776.97  4772.5  774.18  4793.6  771.05  4828.9  772.21
  4871.4  771.19  4878.5  769.67  4892.7  770.75  4899.7  770.07  4906.8  771.61
  4920.9  772.03  4991.4  769.54  4991.8  769.04  4995.8  769.54  5003.8  770.04
  5014.1  774.02  5034.5  771.75  5044.8  771.63  5069.8  776.06  5075.5  775.70
  5085.7  776.69  5177.9  779.09  5377.1  781.94  5454.4  782.29  5464.6  783.25
#Mann=4,-1,0
  4141.4    0.05       0  4991.4   0.033       0  4995.8    0.05       0
  5377.1   0.075       0
Bank Sta=4991.4,4995.8
Exp/Cntr=0.3,0.1

Type RM Length L Ch R = 1,22734,924,924,924
BEGIN DESCRIPTION:
Stream HEN-2 40.0
END DESCRIPTION:
XS GIS Cut Line= 3
      2310378.98      7034060.02      2311179.00      7033260.00
      2311179.00      7032260.00
#Sta/Elev= 30
  3872.3  788.45  3971.3  785.93  4141.0  783.53  4197.6  781.84  4211.7  780.77
  4225.9  781.06  4240.0  783.02  4268.3  780.52  4537.0  776.80  4706.7  775.47
  4777.4  774.02  4834.0  771.34  4890.6  769.61  5000.2  767.38  5033.7  767.62
  5041.5  766.79  5041.9  766.29  5045.9  766.79  5063.7  772.08  5073.7  773.25
  5123.7  773.33  5183.7  774.52  5193.7  775.32  5223.7  775.04  5473.7  779.69
  5643.7  781.38  5803.7  781.96  5843.7  783.02  5863.7  781.79  6003.7  782.55
#Mann=3,-1,0
  3872.3    0.05       0  5041.5   0.033       0  5045.9    0.05       0
Bank Sta=5041.5,5045.9
Exp/Cntr=0.3,0.1

Type RM Length L Ch R = 1,21810,462,462,462
BEGIN DESCRIPTION:
Stream HEN-2 39.0
END DESCRIPTION:
XS GIS Cut Line= 3
      2310828.99      7033760.00      2311579.00      7033660.00
      2311729.04      7033710.01
#Sta/Elev= 30
  4237.4  777.95  4388.7  774.95  4430.4  774.37  4459.4  774.70  4576.6  772.47
  4620.8  772.09  4649.8  771.08  4772.1  769.04  4812.5  767.77  4913.3  766.99
  4952.4  765.70  4973.9  766.51  4984.0  765.57  4991.5  762.41  4996.7  762.41
  5002.4  761.37  5002.8  760.87  5006.4  760.87  5006.8  761.37  5015.1  761.79
  5025.7  763.04  5036.2  763.28  5067.8  762.30  5073.1  762.72  5078.4  763.58
  5088.9  766.61  5099.5  772.45  5110.0  776.49  5120.5  777.85  5152.2  779.86
#Mann=3,-1,0
  4237.4    0.05       0  5002.4   0.033       0  5006.8    0.05       0
Bank Sta=5002.4,5006.8
Exp/Cntr=0.3,0.1

Type RM Length L Ch R = 1,21348,436,436,436
BEGIN DESCRIPTION:
Stream HEN-2 38.0
END DESCRIPTION:
XS GIS Cut Line= 3
      2310979.00      7033860.00      2311579.00      7034060.00
      2311779.04      7033959.98
#Sta/Elev= 30
  4361.1  775.32  4466.5  773.17  4498.1  773.15  4603.5  771.42  4814.4  769.06
  4951.4  764.99  4972.5  763.22  4983.0  759.72  5001.9  760.59  5007.5  759.67
  5015.9  759.76  5024.3  760.56  5027.6  759.26  5028.1  758.76  5031.7  758.76
  5032.1  759.26  5038.3  759.78  5046.7  761.52  5069.0  763.17  5074.6  762.63
  5091.4  764.05  5097.0  763.64  5105.4  764.67  5113.7  765.03  5136.1  764.91
  5150.1  765.89  5158.5  767.74  5180.8  775.84  5186.4  777.03  5217.2  778.52
#Mann=3,-1,0
  4361.1    0.05       0  5027.6   0.033       0  5032.1    0.05       0
Bank Sta=5027.6,5032.1
Exp/Cntr=0.3,0.1

Type RM Length L Ch R = 1,20912,421,421,421
BEGIN DESCRIPTION:
Stream HEN-2 37.0
END DESCRIPTION:
XS GIS Cut Line= 3
      2310979.00      7035410.00      2311879.00      7034210.00
      2311828.99      7034009.96
#Sta/Elev= 30
  3492.9  781.02  3514.8  779.36  3779.4  773.50  4085.6  771.23  4106.4  769.52
  4121.0  771.17  4150.2  770.49  4164.8  768.41  4179.4  770.44  4200.2  770.75
  4542.9  766.13  4629.4  766.63  4835.6  763.09  4942.9  763.68  4995.5  762.44
  5003.2  761.70  5016.1  757.47  5034.1  758.57  5052.2  757.52  5057.3  760.02
  5075.4  757.28  5093.4  758.79  5104.0  757.20  5104.5  756.70  5108.6  757.20
  5139.8  761.08  5157.8  770.21  5175.9  776.05  5181.0  775.21  5199.1  777.53
#Mann=3,-1,0
  3492.9    0.05       0  5104.0   0.033       0  5108.6    0.05       0
Bank Sta=5104,5108.6
Exp/Cntr=0.3,0.1

Type RM Length L Ch R = 1,20491,467,467,467
BEGIN DESCRIPTION:
Stream HEN-2 36.0
END DESCRIPTION:
XS GIS Cut Line= 3
      2311129.03      7035359.97      2312129.00      7034160.00
      2312129.00      7034060.01
#Sta/Elev= 30
  3441.9  777.82  3761.4  771.21  3896.8  770.74  3932.0  768.83  3938.5  770.16
  3952.8  770.36  3974.9  769.49  3981.4  768.21  4010.1  770.26  4244.4  766.76
  4258.7  767.07  4265.2  768.74  4279.5  766.97  4421.4  765.58  4450.0  766.05
  4599.7  763.16  4791.1  761.48  4819.7  760.87  4840.5  758.67  4875.7  757.61
  4961.6  758.08  4990.2  756.67  4994.5  755.38  4995.0  754.88  4999.1  755.38
  5000.7  757.84  5006.4  757.84  5023.9  766.23  5053.9  775.03  5103.9  775.22
#Mann=3,-1,0
  3441.9    0.05       0  4994.5   0.033       0  4999.1    0.05       0
Bank Sta=4994.5,4999.1
Exp/Cntr=0.3,0.1

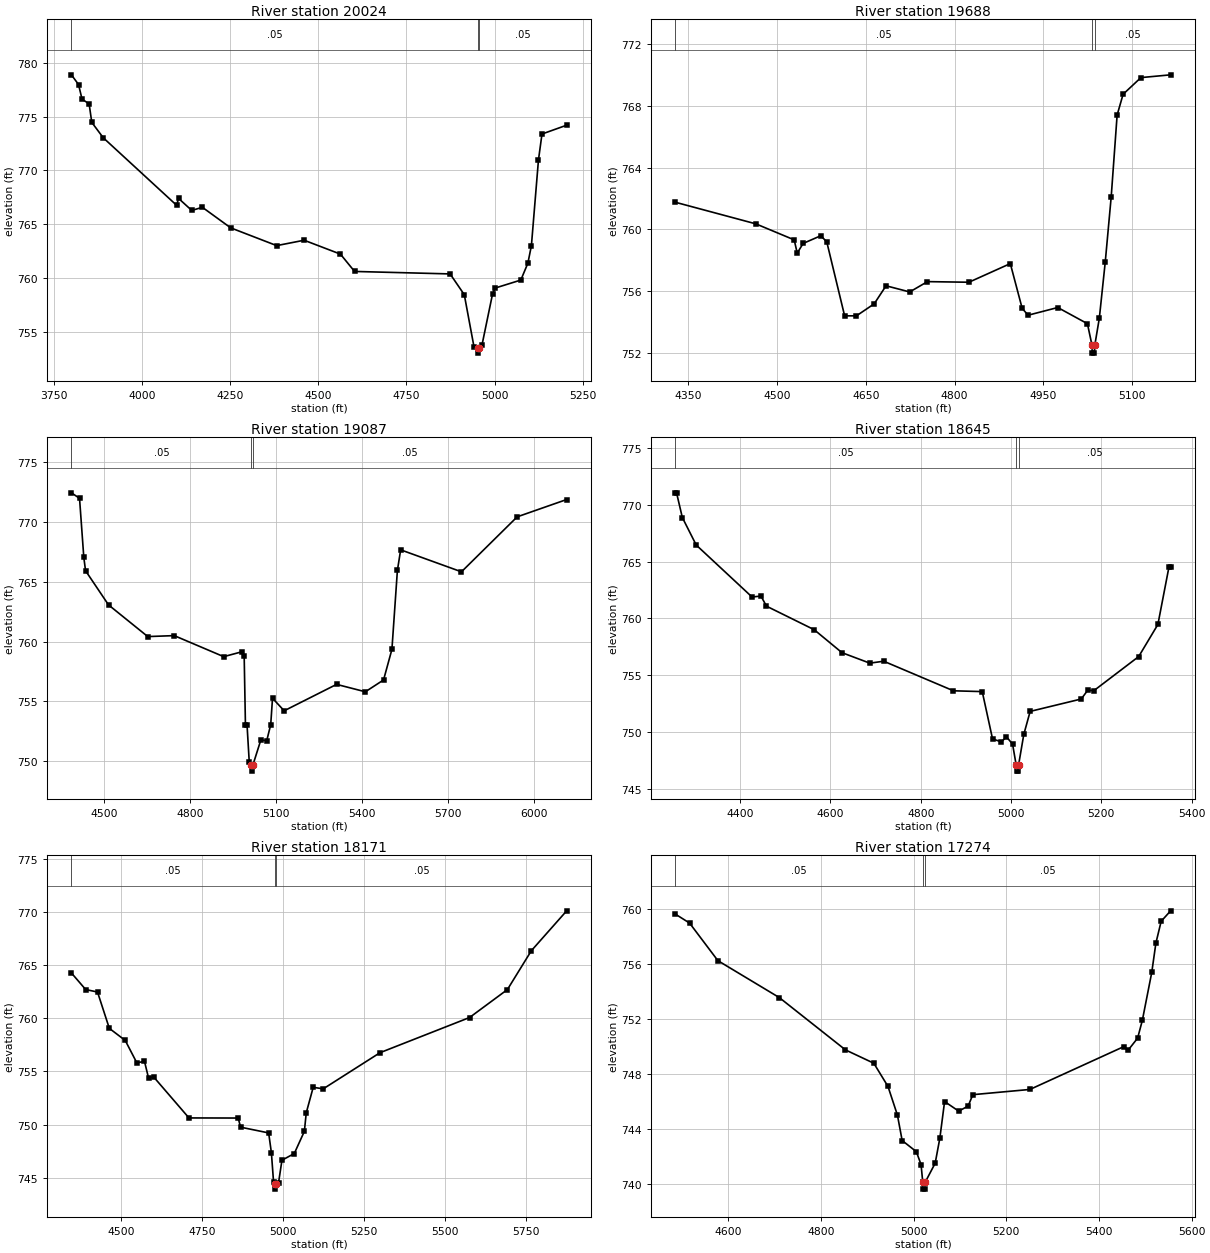
Type RM Length L Ch R = 1,20024,336,336,336
BEGIN DESCRIPTION:
Stream HEN-2 35.0
END DESCRIPTION:
XS GIS Cut Line= 3
      2312179.00      7035510.02      2312279.00      7034310.00
      2312279.00      7034109.98
#Sta/Elev= 30
  3800.3  778.88  3820.4  777.98  3830.4  776.62  3850.5  776.18  3858.0  774.46
  3890.6  773.03  4098.8  766.75  4103.9  767.40  4141.5  766.28  4171.6  766.57
  4251.9  764.66  4382.3  763.01  4460.1  763.51  4563.0  762.22  4603.1  760.61
  4874.0  760.38  4914.2  758.45  4941.8  753.59  4952.0  753.52  4952.5  753.02
  4956.6  753.52  4964.3  753.76  4994.4  758.53  5002.0  759.07  5074.5  759.81
  5094.5  761.38  5104.5  763.01  5124.5  770.97  5134.5  773.38  5204.5  774.20
#Mann=3,-1,0
  3800.3    0.05       0  4952.0   0.033       0  4956.6    0.05       0
Bank Sta=4952,4956.6
Exp/Cntr=0.3,0.1

Type RM Length L Ch R = 1,19688,601,601,601
BEGIN DESCRIPTION:
Stream HEN-2 34.0
END DESCRIPTION:
XS GIS Cut Line= 3
      2312591.19      7034945.92      2312599.63      7034343.90
      2312579.00      7034109.99
#Sta/Elev= 30
  4328.1  761.75  4464.0  760.35  4528.9  759.31  4534.0  758.45  4544.0  759.08
  4574.0  759.58  4584.0  759.17  4614.1  754.38  4634.1  754.38  4664.1  755.16
  4684.1  756.33  4724.1  755.93  4754.1  756.60  4824.1  756.56  4894.1  757.77
  4914.1  754.87  4924.1  754.42  4974.3  754.92  5024.4  753.87  5032.2  752.46
  5032.6  751.96  5036.3  751.96  5036.8  752.46  5044.5  754.22  5054.6  757.90
  5064.6  762.11  5074.6  767.41  5084.7  768.76  5114.8  769.84  5165.0  770.02
#Mann=3,-1,0
  4328.1    0.05       0  5032.2    0.04       0  5036.8    0.05       0
Bank Sta=5032.2,5036.8
Exp/Cntr=0.3,0.1

Type RM Length L Ch R = 1,19087,442,442,442
BEGIN DESCRIPTION:
Stream HEN-2 33.0
END DESCRIPTION:
XS GIS Cut Line= 3
      2313229.01      7035210.01      2312879.00      7034710.00
      2312678.99      7033609.97
#Sta/Elev= 30
  4385.5  772.46  4413.8  772.00  4428.7  767.05  4434.8  765.94  4515.0  763.08
  4651.9  760.43  4744.3  760.51  4916.9  758.75  4982.3  759.17  4988.4  758.80
  4992.8  753.03  4998.4  753.03  5006.0  749.96  5013.7  749.67  5014.3  749.17
  5018.7  749.67  5046.7  751.79  5067.0  751.71  5081.0  753.06  5087.3  755.27
  5128.0  754.22  5310.9  756.43  5411.3  755.81  5474.8  756.80  5504.0  759.36
  5523.1  765.96  5534.5  767.69  5746.7  765.85  5941.1  770.45  6113.9  771.90
#Mann=3,-1,0
  4385.5    0.05       0  5013.7    0.04       0  5018.7    0.05       0
Bank Sta=5013.7,5018.7
Exp/Cntr=0.3,0.1

Type RM Length L Ch R = 1,18645,474,474,474
BEGIN DESCRIPTION:
Stream HEN-2 32.0
END DESCRIPTION:
XS GIS Cut Line= 3
      2313429.00      7035109.99      2313179.00      7034410.00
      2312929.04      7034160.04
#Sta/Elev= 30
  4256.7  771.04  4259.3  771.04  4272.1  768.87  4302.9  766.45  4426.6  761.88
  4446.2  761.97  4458.4  761.08  4564.1  759.01  4625.7  756.99  4687.3  756.07
  4718.1  756.24  4872.6  753.64  4936.3  753.57  4959.1  749.41  4978.8  749.15
  4989.9  749.60  5003.5  748.95  5011.6  747.08  5012.2  746.58  5016.0  746.58
  5016.6  747.08  5028.3  749.80  5042.4  751.83  5155.6  752.92  5169.7  753.68
  5183.8  753.66  5282.8  756.65  5325.3  759.47  5350.0  764.56  5353.5  764.56
#Mann=3,-1,0
  4256.7    0.05       0  5011.6    0.04       0  5016.6    0.05       0
Bank Sta=5011.6,5016.6
Exp/Cntr=0.3,0.1

Type RM Length L Ch R = 1,18171,897,897,897
BEGIN DESCRIPTION:
Stream HEN-2 31.0
END DESCRIPTION:
XS GIS Cut Line= 3
      2313878.98      7034709.97      2313529.00      7034160.00
      2312779.02      7033710.01
#Sta/Elev= 30
  4348.1  764.26  4392.1  762.70  4428.5  762.47  4464.9  759.05  4514.0  757.91
  4549.6  755.81  4573.3  755.94  4586.0  754.35  4601.2  754.49  4710.4  750.62
  4862.0  750.61  4869.6  749.75  4956.0  749.21  4964.4  747.36  4971.2  744.56
  4974.6  744.42  4975.2  743.92  4979.7  744.42  4986.4  744.50  4997.0  746.64
  5035.0  747.27  5066.1  749.36  5071.9  751.10  5093.3  753.50  5124.4  753.36
  5299.3  756.76  5575.3  760.07  5691.9  762.70  5765.8  766.36  5874.6  770.11
#Mann=3,-1,0
  4348.1    0.05       0  4974.6   0.033       0  4979.7    0.05       0
Bank Sta=4974.6,4979.7
Exp/Cntr=0.3,0.1

Type RM Length L Ch R = 1,17274,670,670,670
BEGIN DESCRIPTION:
Stream HEN-2 30.0
END DESCRIPTION:
XS GIS Cut Line= 3
      2314279.01      7034510.03      2314179.00      7034010.00
      2313628.95      7033909.99
#Sta/Elev= 30
  4485.6  759.63  4516.2  758.98  4577.4  756.24  4710.0  753.55  4852.8  749.74
  4913.9  748.77  4944.5  747.08  4964.9  744.99  4975.1  743.14  5005.7  742.33
  5015.9  741.39  5019.6  740.10  5020.3  739.60  5024.1  739.60  5024.8  740.10
  5046.4  741.49  5056.5  743.32  5066.7  745.98  5097.2  745.28  5117.5  745.65
  5127.7  746.48  5250.9  746.86  5452.9  749.97  5463.1  749.73  5483.4  750.60
  5493.6  751.90  5513.9  755.39  5522.8  757.52  5534.2  759.11  5554.6  759.87
#Mann=3,-1,0
  4485.6    0.05       0  5019.6    0.04       0  5024.8    0.05       0
Bank Sta=5019.6,5024.8
Exp/Cntr=0.3,0.1

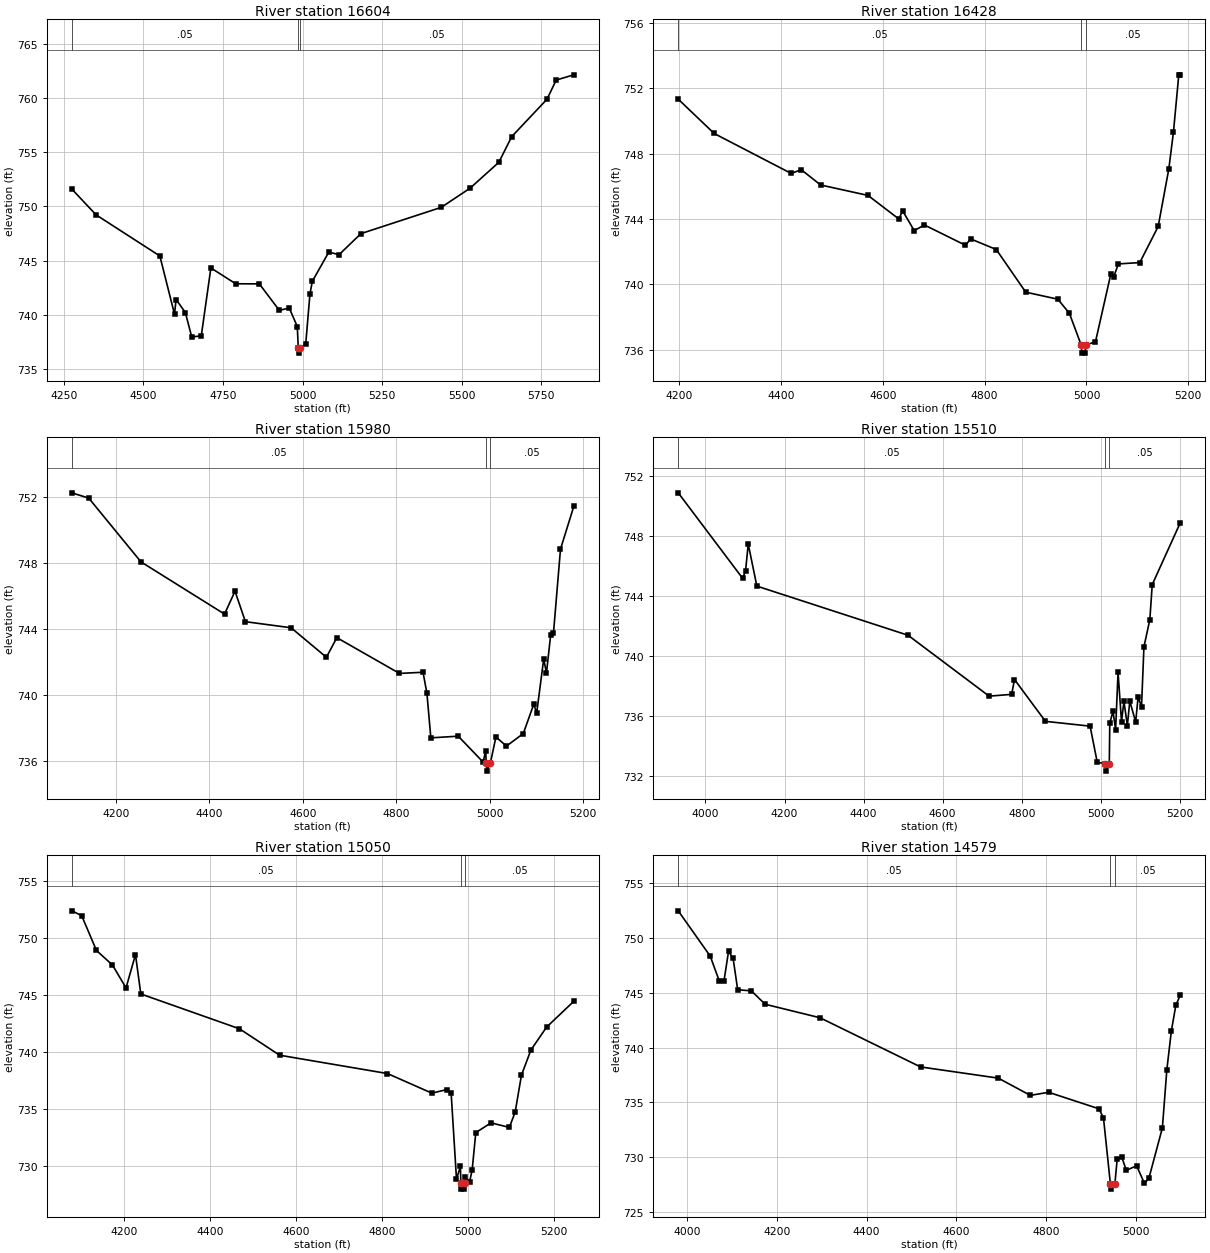
Type RM Length L Ch R = 1,16604,176,176,176
BEGIN DESCRIPTION:
Stream HEN-2 30.5
END DESCRIPTION:
XS GIS Cut Line= 5
      2314263.67      7034216.24      2314295.78      7033706.02
      2314210.15      7033392.02      2313856.90      7033342.07
      2313475.15      7033299.26
#Sta/Elev= 30
  4274.7  751.60  4351.1  749.22  4551.5  745.43  4597.5  740.07  4602.5  741.42
  4631.6  740.22  4651.7  737.96  4681.7  738.08  4711.8  744.33  4789.8  742.87
  4864.1  742.86  4926.9  740.42  4958.0  740.64  4983.3  738.93  4986.4  736.98
  4987.2  736.48  4991.8  736.98  5009.8  737.31  5023.1  741.93  5030.6  743.10
  5082.4  745.79  5114.5  745.55  5183.3  747.49  5435.7  749.91  5526.4  751.68
  5616.6  754.06  5657.2  756.43  5767.9  759.87  5796.9  761.64  5852.3  762.12
#Mann=3,-1,0
  4274.7    0.05       0  4986.4   0.033       0  4991.8    0.05       0
Bank Sta=4986.4,4991.8
Exp/Cntr=0.3,0.1

Type RM Length L Ch R = 1,16428,448,448,448
BEGIN DESCRIPTION:
Stream HEN-2 29.0
END DESCRIPTION:
XS GIS Cut Line= 3
      2314279.00      7034210.03      2314379.00      7033410.00
      2314478.98      7033260.03
#Sta/Elev= 30
  4197.9  751.33  4268.5  749.23  4419.6  746.79  4439.8  747.01  4477.6  746.08
  4570.8  745.44  4631.3  744.00  4638.8  744.50  4661.5  743.29  4681.7  743.63
  4762.3  742.39  4772.4  742.78  4822.8  742.13  4880.7  739.52  4943.7  739.09
  4966.4  738.23  4989.6  736.29  4990.9  735.79  4997.3  735.79  4998.6  736.29
  5017.7  736.48  5047.7  740.61  5053.7  740.47  5062.7  741.25  5104.8  741.33
  5140.9  743.54  5161.9  747.08  5170.9  749.31  5181.4  752.82  5184.4  752.82
#Mann=3,-1,0
  4197.9    0.05       0  4989.6   0.033       0  4998.6    0.05       0
Bank Sta=4989.6,4998.6
Exp/Cntr=0.3,0.1

Type RM Length L Ch R = 1,15980,470,470,470
BEGIN DESCRIPTION:
Stream HEN-2 28.0
END DESCRIPTION:
XS GIS Cut Line= 3
      2314379.01      7034259.98      2314779.00      7033460.00
      2314678.99      7033309.98
#Sta/Elev= 30
  4105.6  752.25  4141.9  751.93  4253.7  748.06  4432.6  744.89  4455.0  746.28
  4477.3  744.43  4575.1  744.06  4650.6  742.27  4673.0  743.46  4807.1  741.29
  4857.5  741.36  4865.8  740.08  4874.2  737.38  4932.9  737.48  4986.0  735.91
  4991.6  736.57  4992.7  735.86  4994.0  735.36  5001.7  735.86  5013.5  737.43
  5036.1  736.88  5072.1  737.64  5094.6  739.43  5100.7  738.87  5115.7  742.15
  5121.7  741.33  5130.7  743.62  5136.7  743.74  5151.7  748.83  5180.3  751.44
#Mann=3,-1,0
  4105.6    0.05       0  4992.7   0.033       0  5001.7    0.05       0
Bank Sta=4992.7,5001.7
Exp/Cntr=0.3,0.1

Type RM Length L Ch R = 1,15510,460,460,460
BEGIN DESCRIPTION:
Stream HEN-2 27.0
END DESCRIPTION:
XS GIS Cut Line= 3
      2314479.01      7034209.99      2315179.00      7033410.00
      2315296.94      7033240.12
#Sta/Elev= 30
  3931.2  750.88  4094.0  745.18  4101.5  745.67  4108.2  747.47  4130.0  744.66
  4512.5  741.38  4717.5  737.32  4774.5  737.44  4781.6  738.43  4859.9  735.64
  4972.8  735.32  4990.9  732.91  5011.5  732.82  5012.9  732.32  5021.4  732.82
  5022.6  735.51  5030.7  736.31  5037.4  735.09  5043.5  738.91  5052.3  735.62
  5058.4  736.97  5067.1  735.36  5073.2  736.99  5088.1  735.60  5094.2  737.25
  5102.9  736.63  5109.0  740.61  5123.9  742.42  5130.0  744.76  5201.0  748.89
#Mann=3,-1,0
  3931.2    0.05       0  5011.5   0.033       0  5021.4    0.05       0
Bank Sta=5011.5,5021.4
Exp/Cntr=0.3,0.1

Type RM Length L Ch R = 1,15050,471,471,471
BEGIN DESCRIPTION:
Stream HEN-2 26.0
END DESCRIPTION:
XS GIS Cut Line= 3
      2314529.00      7034260.00      2315329.00      7033810.00
      2315479.01      7033609.99
#Sta/Elev= 30
  4077.8  752.37  4100.8  751.95  4135.2  748.89  4172.5  747.61  4204.0  745.60
  4226.0  748.53  4238.4  745.07  4467.9  742.01  4561.3  739.69  4812.1  738.08
  4915.4  736.36  4950.1  736.67  4960.3  736.35  4972.7  728.82  4982.0  729.93
  4982.7  728.43  4984.1  727.93  4991.3  727.93  4992.7  728.43  4992.8  728.99
  5003.0  728.53  5009.2  729.62  5017.6  732.89  5053.0  733.75  5095.7  733.35
  5109.2  734.70  5123.8  737.93  5145.7  740.14  5182.1  742.15  5245.7  744.43
#Mann=3,-1,0
  4077.8    0.05       0  4982.7   0.033       0  4992.7    0.05       0
Bank Sta=4982.7,4992.7
Exp/Cntr=0.3,0.1

Type RM Length L Ch R = 1,14579,461,461,461
BEGIN DESCRIPTION:
Stream HEN-2 25.0
END DESCRIPTION:
XS GIS Cut Line= 3
      2314578.97      7034310.01      2315579.00      7034110.00
      2315678.97      7034110.00
#Sta/Elev= 30
  3980.1  752.45  4051.5  748.32  4071.9  746.03  4082.1  746.06  4092.3  748.76
  4102.5  748.12  4112.7  745.26  4143.3  745.16  4173.9  743.94  4296.3  742.71
  4520.6  738.23  4694.0  737.21  4765.4  735.64  4806.2  735.92  4918.3  734.42
  4928.5  733.60  4943.9  727.60  4945.3  727.10  4954.0  727.60  4959.1  729.84
  4969.3  730.02  4979.5  728.81  5002.4  729.23  5019.9  727.62  5029.9  728.10
  5059.9  732.68  5069.9  737.99  5079.9  741.50  5089.9  743.84  5099.9  744.78
#Mann=3,-1,0
  3980.1    0.05       0  4943.9   0.033       0  4954.0    0.05       0
Bank Sta=4943.9,4954
Exp/Cntr=0.3,0.1

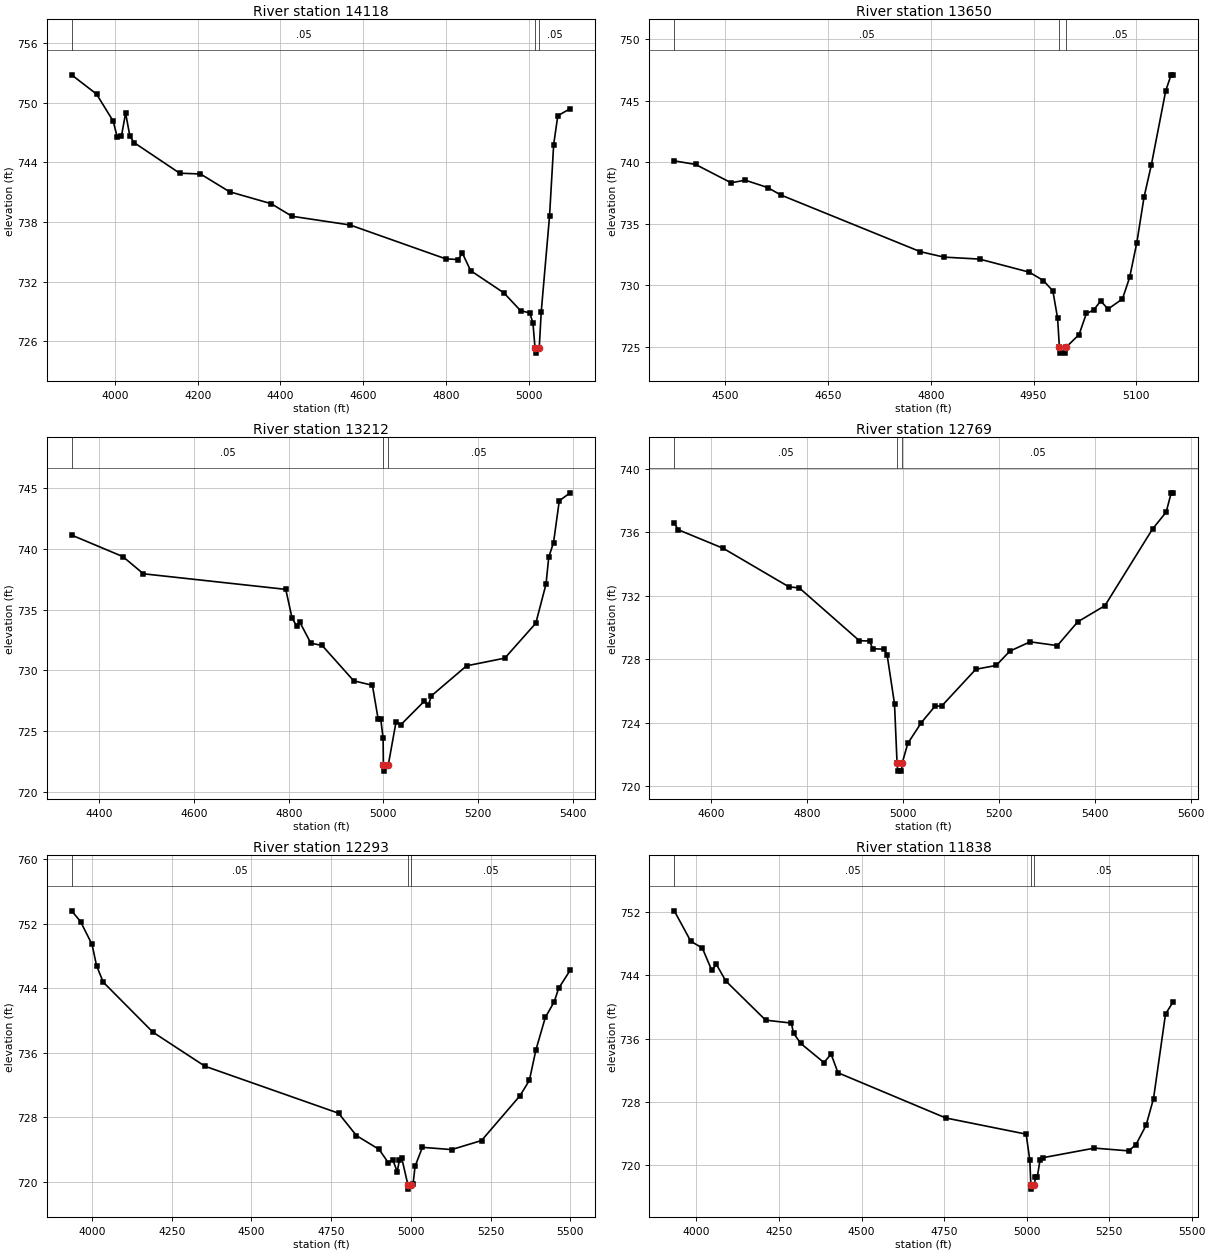
Type RM Length L Ch R = 1,14118,468,468,468
BEGIN DESCRIPTION:
Stream HEN-2 24.0
END DESCRIPTION:
XS GIS Cut Line= 3
      2314579.02      7034360.00      2315679.00      7034460.00
      2315778.99      7034460.00
#Sta/Elev= 30
  3895.4  752.83  3955.6  750.89  3995.8  748.17  4005.8  746.54  4015.9  746.68
  4025.9  748.98  4036.0  746.69  4046.0  746.01  4156.4  742.92  4206.7  742.84
  4276.9  741.05  4377.4  739.85  4427.6  738.58  4568.1  737.70  4799.1  734.29
  4829.2  734.22  4839.3  734.87  4859.3  733.10  4939.7  730.86  4979.8  729.07
  5002.4  728.84  5009.9  727.78  5014.9  725.29  5016.3  724.79  5025.0  725.29
  5029.9  728.98  5049.9  738.58  5059.9  745.81  5069.9  748.71  5099.9  749.42
#Mann=3,-1,0
  3895.4    0.05       0  5014.9   0.033       0  5025.0    0.05       0
Bank Sta=5014.9,5025
Exp/Cntr=0.3,0.1

Type RM Length L Ch R = 1,13650,438,438,438
BEGIN DESCRIPTION:
Stream HEN-2 23.0
END DESCRIPTION:
XS GIS Cut Line= 3
      2315028.95      7035010.01      2315579.00      7034860.00
      2315728.95      7034810.02
#Sta/Elev= 30
  4425.3  740.12  4456.4  739.83  4508.3  738.34  4529.0  738.55  4561.8  737.95
  4580.8  737.35  4784.7  732.74  4819.2  732.30  4871.1  732.14  4943.6  731.08
  4964.3  730.40  4978.2  729.55  4985.1  727.34  4987.7  725.00  4989.2  724.50
  4996.5  724.50  4997.9  725.00  5016.5  726.01  5027.1  727.72  5037.6  727.99
  5048.1  728.74  5058.7  728.08  5079.8  728.90  5090.3  730.65  5100.8  733.47
  5111.4  737.19  5121.9  739.76  5143.0  745.81  5150.9  747.11  5153.5  747.11
#Mann=3,-1,0
  4425.3    0.05       0  4987.7   0.033       0  4997.9    0.05       0
Bank Sta=4987.7,4997.9
Exp/Cntr=0.3,0.1

Type RM Length L Ch R = 1,13212,443,443,443
BEGIN DESCRIPTION:
Stream HEN-2 22.0
END DESCRIPTION:
XS GIS Cut Line= 3
      2315029.03      7035509.99      2315629.00      7035260.00
      2315829.01      7034909.98
#Sta/Elev= 30
  4341.5  741.12  4449.8  739.35  4493.1  737.94  4793.8  736.66  4807.3  734.27
  4817.6  733.62  4823.0  734.00  4846.8  732.24  4870.7  732.05  4937.3  729.15
  4976.8  728.78  4988.8  726.04  4994.3  726.04  4999.4  724.43  5000.0  722.23
  5001.4  721.73  5010.3  722.23  5026.7  725.77  5036.8  725.54  5085.8  727.45
  5095.1  727.19  5101.6  727.92  5175.7  730.38  5256.4  731.01  5321.9  733.88
  5343.5  737.10  5349.2  739.30  5359.3  740.49  5371.5  743.94  5394.6  744.59
#Mann=3,-1,0
  4341.5    0.05       0  5000.0   0.033       0  5010.3    0.05       0
Bank Sta=5000,5010.3
Exp/Cntr=0.3,0.1

Type RM Length L Ch R = 1,12769,476,476,476
BEGIN DESCRIPTION:
Stream HEN-2 21.0
END DESCRIPTION:
XS GIS Cut Line= 3
      2315478.98      7035810.01      2315879.00      7035560.00
      2316279.00      7035160.00
#Sta/Elev= 30
  4524.1  736.59  4531.8  736.16  4626.1  734.98  4762.9  732.55  4784.1  732.49
  4909.1  729.16  4930.4  729.14  4936.9  728.66  4960.4  728.62  4966.9  728.27
  4982.3  725.18  4987.6  721.44  4989.0  720.94  4996.7  720.94  4998.2  721.44
  5010.0  722.69  5038.2  724.00  5066.5  725.03  5080.7  725.05  5151.4  727.36
  5193.8  727.60  5222.1  728.50  5264.5  729.09  5321.1  728.85  5363.5  730.35
  5420.1  731.37  5519.1  736.20  5547.4  737.26  5558.0  738.48  5561.5  738.48
#Mann=3,-1,0
  4524.1    0.05       0  4987.6   0.033       0  4998.2    0.05       0
Bank Sta=4987.6,4998.2
Exp/Cntr=0.3,0.1

Type RM Length L Ch R = 1,12293,455,455,455
BEGIN DESCRIPTION:
Stream HEN-2 20.0
END DESCRIPTION:
XS GIS Cut Line= 3
      2315428.98      7036460.02      2316229.00      7035760.00
      2316528.98      7035360.03
#Sta/Elev= 30
  3936.4  753.58  3964.4  752.25  4000.5  749.41  4014.7  746.77  4035.6  744.74
  4191.3  738.54  4354.5  734.32  4773.1  728.50  4829.1  725.73  4900.3  724.01
  4928.7  722.39  4943.0  722.73  4957.2  721.25  4963.8  722.67  4971.4  722.91
  4990.8  719.59  4992.3  719.09  5001.5  719.59  5006.7  719.70  5013.0  721.91
  5035.9  724.27  5127.6  723.99  5221.3  725.11  5342.1  730.67  5371.3  732.57
  5392.1  736.38  5421.3  740.37  5449.4  742.32  5463.0  743.98  5499.4  746.22
#Mann=3,-1,0
  3936.4    0.05       0  4990.8   0.033       0  5001.5    0.05       0
Bank Sta=4990.8,5001.5
Exp/Cntr=0.3,0.1

Type RM Length L Ch R = 1,11838,434,434,434
BEGIN DESCRIPTION:
Stream HEN-2 19.0
END DESCRIPTION:
XS GIS Cut Line= 3
      2315828.98      7036810.02      2316529.00      7036010.00
      2316729.02      7035609.96
#Sta/Elev= 30
  3932.9  752.19  3982.8  748.34  4017.9  747.47  4046.3  744.66  4060.6  745.39
  4089.1  743.29  4209.6  738.33  4287.4  737.96  4294.1  736.69  4315.9  735.38
  4386.1  732.96  4408.0  734.02  4428.8  731.66  4755.3  725.93  4998.7  723.88
  5009.9  720.55  5012.9  717.41  5014.4  716.91  5023.7  717.41  5026.7  718.43
  5032.3  718.39  5040.7  720.61  5049.0  720.89  5205.6  722.11  5309.0  721.76
  5331.4  722.55  5362.1  725.02  5384.5  728.39  5420.8  739.11  5443.2  740.60
#Mann=3,-1,0
  3932.9    0.05       0  5012.9    0.04       0  5023.7    0.05       0
Bank Sta=5012.9,5023.7
Exp/Cntr=0.3,0.1