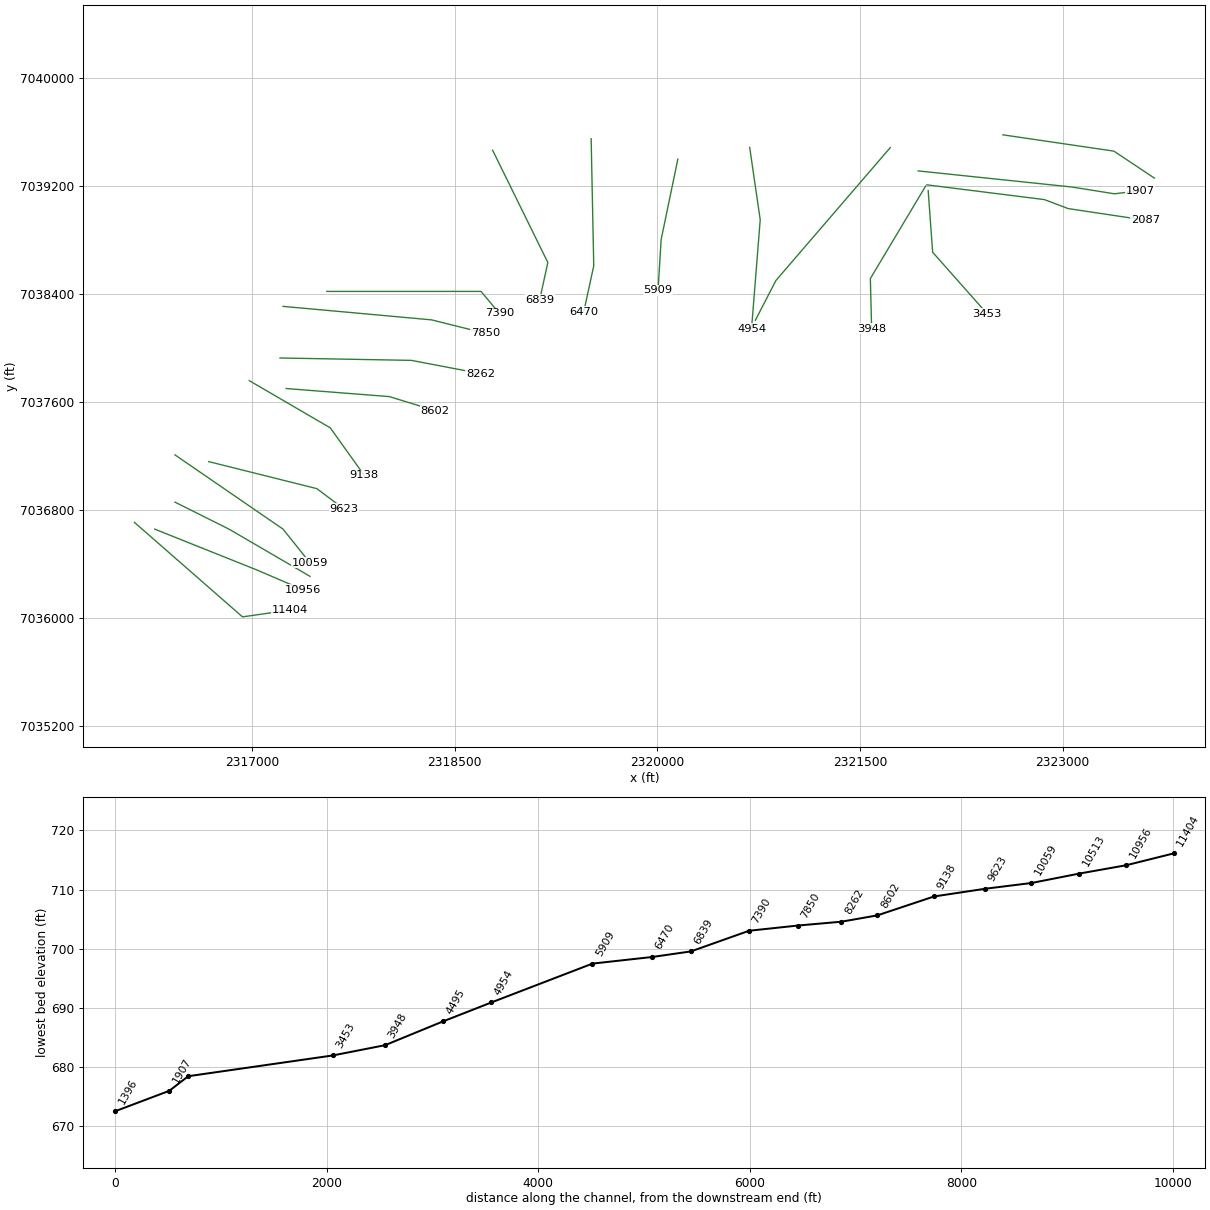
HEC-RAS study Stream HEN-2.prj: Stream HEN-2 Base Level Engineering

--- Stream HEN-2.g01 (geometry) --- (continued)

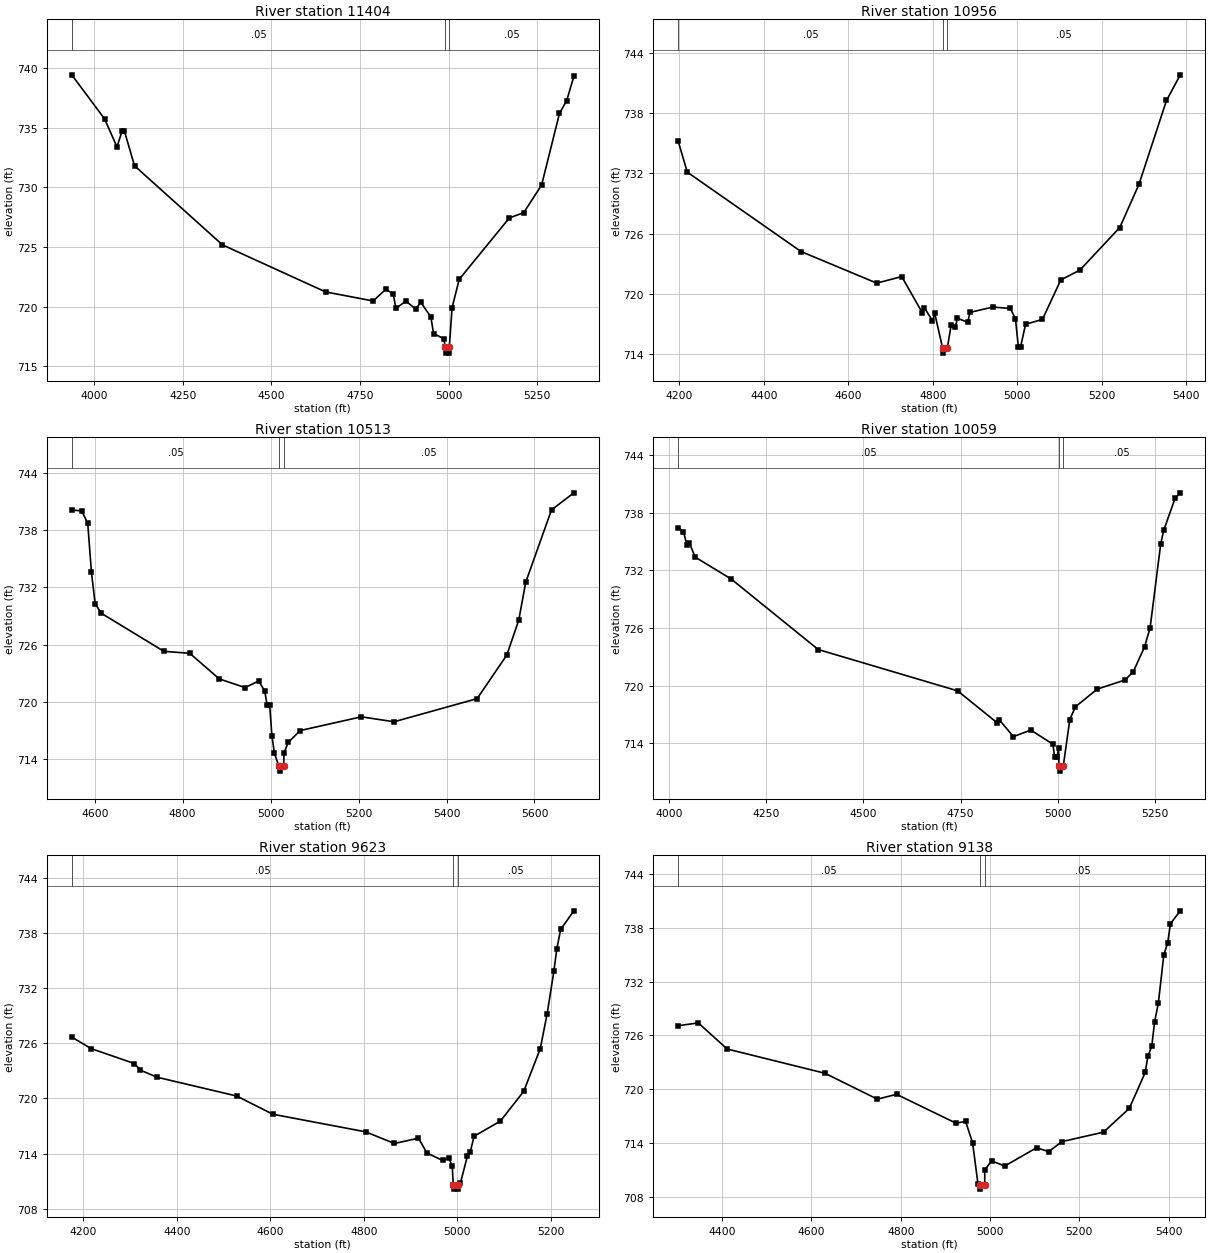
Type RM Length L Ch R = 1,11404,448,448,448
BEGIN DESCRIPTION:
Stream HEN-2 18.0
END DESCRIPTION:
XS GIS Cut Line= 3
      2316129.01      7036709.99      2316929.00      7036010.00
      2317279.05      7036060.01
#Sta/Elev= 30
  3937.0  739.44  4029.5  735.75  4064.6  733.40  4078.9  734.73  4085.5  734.73
  4114.0  731.82  4362.2  725.19  4653.1  721.25  4787.4  720.49  4823.0  721.47
  4843.9  721.08  4851.5  719.87  4879.9  720.48  4907.5  719.81  4921.7  720.38
  4950.2  719.15  4957.8  717.75  4986.2  717.34  4991.1  716.62  4992.6  716.12
  5000.7  716.12  5002.2  716.62  5010.1  719.94  5030.3  722.31  5171.7  727.45
  5212.1  727.89  5262.6  730.20  5313.1  736.21  5333.4  737.28  5353.6  739.31
#Mann=3,-1,0
  3937.0    0.05       0  4991.1   0.033       0  5002.2    0.05       0
Bank Sta=4991.1,5002.2
Exp/Cntr=0.3,0.1

Type RM Length L Ch R = 1,10956,443,443,443
BEGIN DESCRIPTION:
Stream HEN-2 17.0
END DESCRIPTION:
XS GIS Cut Line= 3
      2316279.00      7036660.00      2317029.00      7036360.00
      2317379.03      7036209.99
#Sta/Elev= 30
  4197.2  735.17  4218.7  732.11  4488.0  724.22  4667.1  721.08  4726.3  721.73
  4774.8  718.15  4780.1  718.63  4799.0  717.34  4804.4  718.07  4823.1  714.62
  4824.6  714.12  4834.2  714.62  4843.4  716.95  4852.8  716.68  4858.2  717.58
  4882.5  717.20  4887.9  718.17  4941.7  718.70  4983.4  718.56  4995.6  717.53
  5002.3  714.75  5007.7  714.75  5019.5  716.99  5059.4  717.47  5102.9  721.40
  5148.2  722.38  5242.5  726.61  5287.9  730.90  5353.1  739.24  5385.8  741.79
#Mann=3,-1,0
  4197.2    0.05       0  4823.1   0.033       0  4834.2    0.05       0
Bank Sta=4823.1,4834.2
Exp/Cntr=0.3,0.1

Type RM Length L Ch R = 1,10513,454,454,454
BEGIN DESCRIPTION:
Stream HEN-2 16.0
END DESCRIPTION:
XS GIS Cut Line= 3
      2316429.00      7036860.00      2316829.00      7036660.00
      2317428.97      7036310.02
#Sta/Elev= 30
  4547.8  740.11  4570.2  740.03  4584.1  738.72  4592.5  733.62  4600.9  730.29
  4614.9  729.28  4757.4  725.28  4816.1  725.08  4883.2  722.39  4941.9  721.48
  4972.7  722.17  4986.6  721.13  4992.2  719.62  4997.9  719.62  5002.9  716.43
  5008.7  714.59  5018.8  713.21  5020.3  712.71  5029.9  713.21  5030.2  714.59
  5040.1  715.73  5067.4  716.97  5206.3  718.41  5280.7  717.89  5469.7  720.32
  5537.1  724.89  5564.4  728.57  5580.1  732.53  5638.8  740.13  5689.6  741.92
#Mann=3,-1,0
  4547.8    0.05       0  5018.8   0.033       0  5029.9    0.05       0
Bank Sta=5018.8,5029.9
Exp/Cntr=0.3,0.1

Type RM Length L Ch R = 1,10059,436,436,436
BEGIN DESCRIPTION:
Stream HEN-2 15.0
END DESCRIPTION:
XS GIS Cut Line= 3
      2316429.04      7037209.98      2317229.00      7036660.00
      2317428.98      7036410.03
#Sta/Elev= 30
  4023.9  736.44  4037.4  736.01  4046.2  734.65  4052.3  734.89  4067.2  733.38
  4159.8  731.10  4383.8  723.76  4742.3  719.46  4843.8  716.14  4849.9  716.42
  4885.7  714.70  4930.4  715.38  4987.2  713.91  4991.6  712.58  4997.9  712.58
  5001.9  713.54  5002.7  711.61  5004.2  711.11  5013.8  711.61  5030.7  716.48
  5045.1  717.80  5101.1  719.64  5173.2  720.60  5194.0  721.47  5222.8  724.02
  5237.2  726.04  5264.4  734.74  5272.4  736.19  5301.2  739.47  5314.8  740.06
#Mann=3,-1,0
  4023.9    0.05       0  5002.7   0.033       0  5013.8    0.05       0
Bank Sta=5002.7,5013.8
Exp/Cntr=0.3,0.1

Type RM Length L Ch R = 1,9623,485,485,485
BEGIN DESCRIPTION:
Stream HEN-2 14.0
END DESCRIPTION:
XS GIS Cut Line= 3
      2316679.02      7037160.00      2317479.00      7036960.00
      2317679.00      7036810.00
#Sta/Elev= 30
  4175.0  726.67  4216.2  725.42  4309.0  723.79  4321.9  723.07  4357.9  722.30
  4528.0  720.26  4605.3  718.28  4803.8  716.37  4865.6  715.10  4917.1  715.68
  4935.2  714.06  4968.7  713.26  4981.6  713.53  4989.3  712.67  4991.5  710.64
  4993.0  710.14  5001.1  710.14  5002.6  710.64  5006.9  710.80  5021.5  713.69
  5027.7  714.15  5036.1  715.89  5092.3  717.53  5142.3  720.77  5177.7  725.40
  5192.3  729.16  5206.9  733.83  5213.1  736.25  5221.5  738.38  5249.6  740.39
#Mann=3,-1,0
  4175.0    0.05       0  4991.5   0.033       0  5002.6    0.05       0
Bank Sta=4991.5,5002.6
Exp/Cntr=0.3,0.1

Type RM Length L Ch R = 1,9138,536,536,536
BEGIN DESCRIPTION:
Stream HEN-2 13.0
END DESCRIPTION:
XS GIS Cut Line= 3
      2316979.03      7037759.98      2317579.00      7037410.00
      2317829.00      7037060.00
#Sta/Elev= 30
  4301.6  727.07  4346.6  727.38  4411.1  724.47  4630.3  721.76  4747.7  718.87
  4790.7  719.41  4923.8  716.19  4945.3  716.39  4961.0  713.99  4973.0  709.43
  4976.9  709.33  4978.5  708.83  4988.1  709.33  4988.3  710.99  5003.6  711.97
  5033.1  711.41  5104.3  713.45  5131.4  713.01  5160.9  714.13  5254.3  715.19
  5312.0  717.84  5347.7  721.85  5353.8  723.70  5362.4  724.77  5368.5  727.45
  5377.1  729.59  5389.4  734.99  5398.0  736.30  5404.2  738.46  5426.3  739.89
#Mann=3,-1,0
  4301.6    0.05       0  4976.9   0.033       0  4988.1    0.05       0
Bank Sta=4976.9,4988.1
Exp/Cntr=0.3,0.1

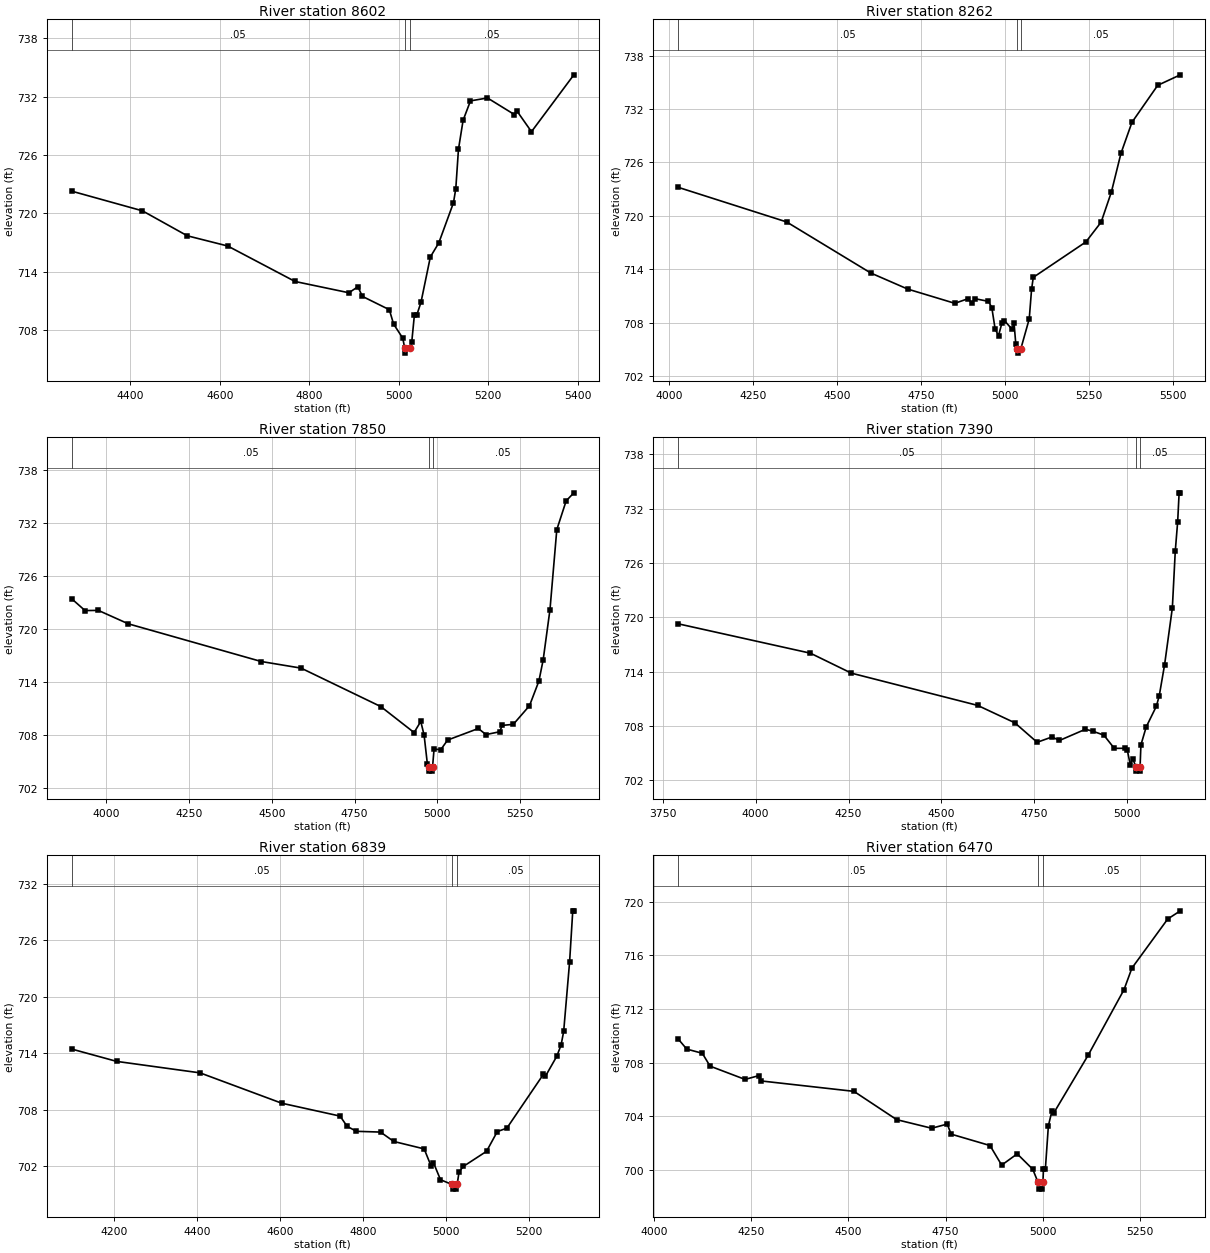
Type RM Length L Ch R = 1,8602,340,340,340
BEGIN DESCRIPTION:
Stream HEN-2 12.0
END DESCRIPTION:
XS GIS Cut Line= 3
      2317251.55      7037701.45      2318015.71      7037641.69
      2318355.64      7037537.58
#Sta/Elev= 30
  4269.4  722.29  4427.3  720.27  4527.6  717.70  4617.9  716.65  4768.4  713.00
  4888.7  711.84  4908.8  712.46  4918.8  711.47  4979.0  710.10  4988.7  708.61
  5009.1  707.17  5013.5  706.13  5015.1  705.63  5024.7  706.13  5029.2  706.79
  5035.0  709.52  5040.2  709.52  5049.8  710.86  5070.7  715.52  5089.6  716.97
  5122.4  721.10  5127.6  722.56  5133.5  726.58  5143.9  729.58  5160.4  731.58
  5198.4  731.88  5258.7  730.17  5263.9  730.56  5296.7  728.41  5391.4  734.26
#Mann=3,-1,0
  4269.4    0.05       0  5013.5   0.033       0  5024.7    0.05       0
Bank Sta=5013.5,5024.7
Exp/Cntr=0.3,0.1

Type RM Length L Ch R = 1,8262,412,412,412
BEGIN DESCRIPTION:
Stream HEN-2 11.0
END DESCRIPTION:
XS GIS Cut Line= 3
      2317206.72      7037927.72      2318179.00      7037910.00
      2318690.24      7037812.45
#Sta/Elev= 30
  4027.8  723.20  4350.1  719.31  4600.2  713.57  4710.2  711.76  4850.2  710.16
  4890.2  710.69  4900.2  710.16  4910.2  710.68  4950.2  710.38  4960.2  709.68
  4970.2  707.24  4980.2  706.54  4990.2  707.93  4997.7  708.22  5020.6  707.23
  5026.3  707.94  5031.4  705.64  5035.4  705.06  5036.9  704.56  5046.6  705.06
  5071.5  708.41  5078.4  711.72  5083.5  713.08  5239.9  717.06  5285.3  719.29
  5315.8  722.68  5344.2  727.02  5376.9  730.51  5453.5  734.67  5520.7  735.85
#Mann=3,-1,0
  4027.8    0.05       0  5035.4   0.033       0  5046.6    0.05       0
Bank Sta=5035.4,5046.6
Exp/Cntr=0.3,0.1

Type RM Length L Ch R = 1,7850,460,460,460
BEGIN DESCRIPTION:
Stream HEN-2 10.0
END DESCRIPTION:
XS GIS Cut Line= 3
      2317229.02      7038310.00      2318329.00      7038210.00
      2318728.97      7038110.01
#Sta/Elev= 30
  3895.8  723.43  3935.9  722.10  3976.1  722.12  4066.5  720.60  4468.1  716.33
  4588.6  715.58  4829.6  711.22  4930.0  708.28  4950.1  709.54  4960.2  708.00
  4970.2  704.68  4974.6  704.41  4976.1  703.91  4984.3  703.91  4985.8  704.41
  4990.3  706.41  5010.6  706.34  5031.2  707.43  5124.0  708.74  5147.2  708.05
  5188.4  708.37  5196.2  709.09  5229.7  709.21  5278.6  711.32  5307.0  714.11
  5319.9  716.51  5340.5  722.21  5361.1  731.27  5389.4  734.53  5412.6  735.44
#Mann=3,-1,0
  3895.8    0.05       0  4974.6   0.033       0  4985.8    0.05       0
Bank Sta=4974.6,4985.8
Exp/Cntr=0.3,0.1

Type RM Length L Ch R = 1,7390,551,551,551
BEGIN DESCRIPTION:
Stream HEN-2 9.0
END DESCRIPTION:
XS GIS Cut Line= 3
      2317553.37      7038420.84      2318694.62      7038420.84
      2318828.98      7038260.03
#Sta/Elev= 30
  3791.9  719.28  4147.5  716.04  4257.5  713.84  4597.5  710.28  4697.5  708.36
  4757.5  706.21  4797.5  706.80  4817.5  706.41  4887.5  707.65  4907.5  707.43
  4937.0  707.00  4965.1  705.54  4993.7  705.55  5000.2  705.32  5008.0  703.75
  5014.6  704.40  5023.2  703.53  5024.8  703.03  5033.0  703.03  5034.5  703.53
  5036.7  705.92  5051.0  707.91  5078.3  710.19  5086.1  711.36  5100.4  714.77
  5121.3  721.04  5129.1  727.28  5135.6  730.55  5139.5  733.73  5142.7  733.73
#Mann=3,-1,0
  3791.9    0.05       0  5023.2   0.033       0  5034.5    0.05       0
Bank Sta=5023.2,5034.5
Exp/Cntr=0.3,0.1

Type RM Length L Ch R = 1,6839,369,369,369
BEGIN DESCRIPTION:
Stream HEN-2 8.0
END DESCRIPTION:
XS GIS Cut Line= 3
      2318780.22      7039467.00      2319189.17      7038634.83
      2319128.99      7038359.96
#Sta/Elev= 30
  4099.2  714.43  4207.3  713.12  4408.0  711.90  4604.7  708.67  4745.1  707.30
  4762.0  706.21  4784.5  705.68  4842.4  705.60  4874.4  704.60  4947.5  703.81
  4964.4  701.96  4969.9  702.34  4986.8  700.53  5014.4  700.03  5016.2  699.53
  5025.2  699.53  5026.9  700.03  5031.5  701.36  5041.6  701.94  5097.6  703.55
  5123.5  705.65  5146.6  706.02  5234.3  711.73  5239.4  711.54  5266.8  713.67
  5277.1  714.87  5283.3  716.31  5297.5  723.66  5305.2  729.14  5307.8  729.14
#Mann=3,-1,0
  4099.2    0.05       0  5014.4   0.033       0  5026.9    0.05       0
Bank Sta=5014.4,5026.9
Exp/Cntr=0.3,0.1

Type RM Length L Ch R = 1,6470,561,561,561
BEGIN DESCRIPTION:
Stream HEN-2 7.0
END DESCRIPTION:
XS GIS Cut Line= 3
      2319509.77      7039551.89      2319529.00      7038610.00
      2319454.76      7038268.36
#Sta/Elev= 30
  4062.4  709.77  4084.3  709.02  4124.3  708.71  4144.3  707.75  4234.3  706.76
  4269.4  707.04  4274.4  706.65  4514.4  705.87  4624.4  703.76  4714.4  703.12
  4754.4  703.43  4764.5  702.68  4864.5  701.83  4894.5  700.37  4934.5  701.21
  4974.5  700.06  4988.2  699.08  4990.0  698.58  4999.0  698.58  5000.7  699.08
  5002.0  700.11  5007.0  700.11  5014.7  703.31  5023.9  704.41  5029.0  704.28
  5117.1  708.57  5209.2  713.45  5229.6  715.06  5321.7  718.72  5354.1  719.33
#Mann=3,-1,0
  4062.4    0.05       0  4988.2   0.033       0  5000.7    0.05       0
Bank Sta=4988.2,5000.7
Exp/Cntr=0.3,0.1

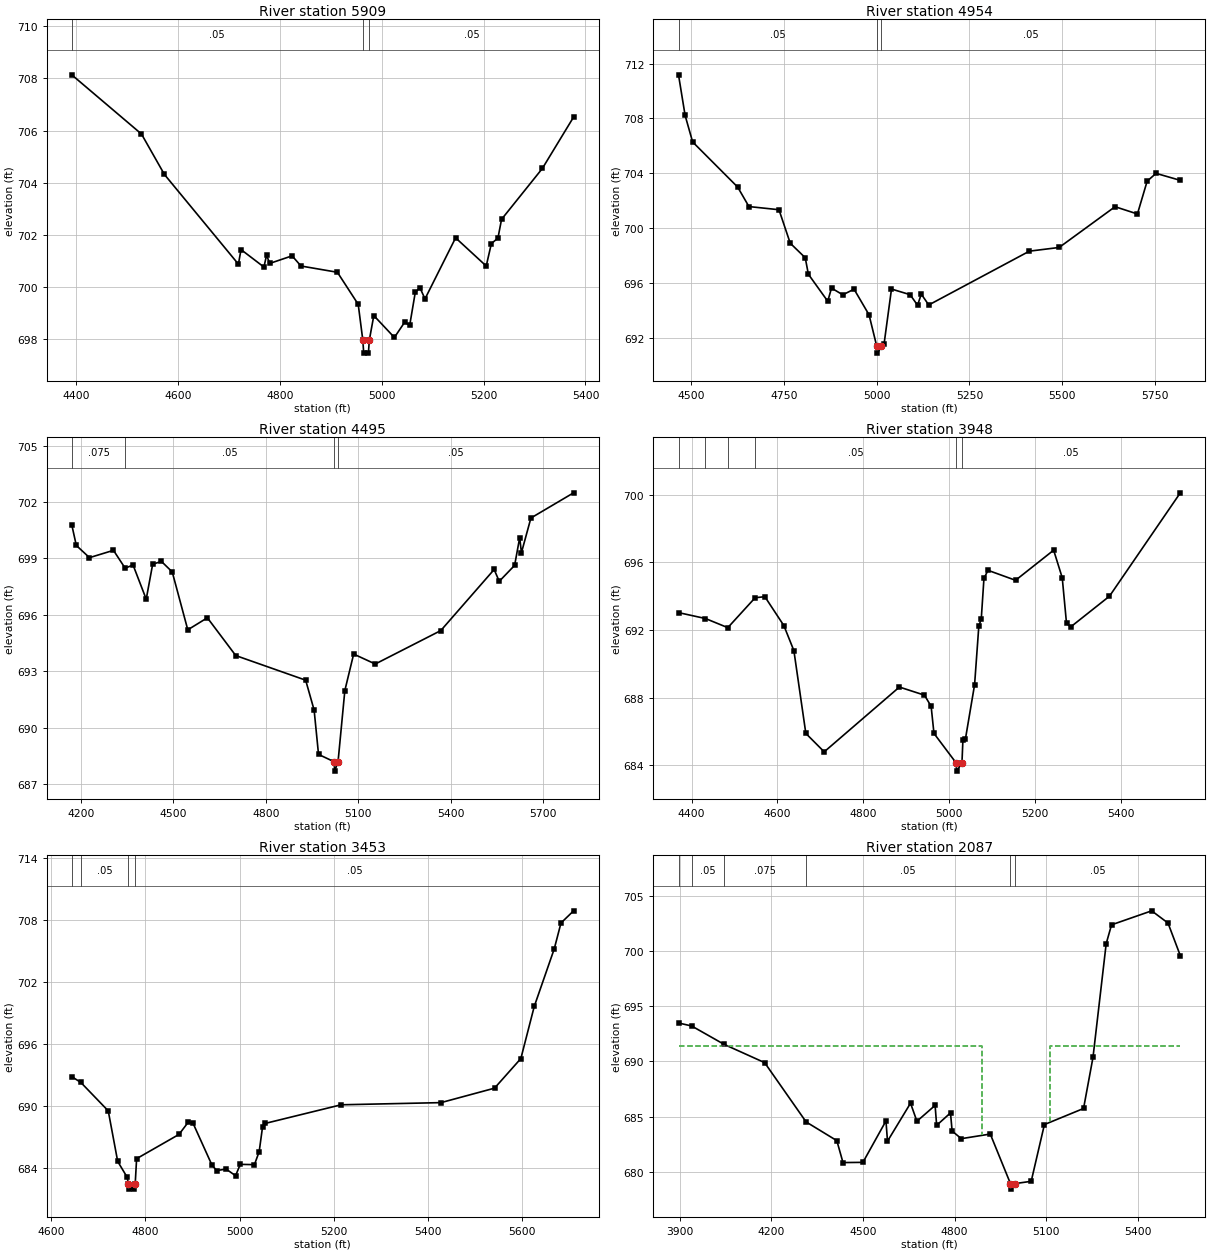
Type RM Length L Ch R = 1,5909,955,955,955
BEGIN DESCRIPTION:
Stream HEN-2 6.0
END DESCRIPTION:
XS GIS Cut Line= 3
      2320151.52      7039400.64      2320027.75      7038804.70
      2320004.83      7038428.86
#Sta/Elev= 30
  4391.5  708.14  4528.4  705.87  4573.4  704.32  4718.7  700.88  4723.8  701.44
  4768.8  700.77  4773.9  701.22  4780.3  700.91  4824.1  701.20  4841.5  700.81
  4913.0  700.57  4953.9  699.34  4962.9  697.97  4964.7  697.47  4973.9  697.47
  4975.7  697.97  4984.5  698.91  5024.9  698.07  5044.9  698.65  5055.0  698.54
  5065.9  699.80  5075.0  699.98  5085.0  699.55  5145.1  701.89  5205.2  700.81
  5215.3  701.67  5228.2  701.88  5235.3  702.60  5315.4  704.55  5376.7  706.52
#Mann=3,-1,0
  4391.5    0.05       0  4962.9   0.033       0  4975.7    0.05       0
Bank Sta=4962.9,4975.7
Exp/Cntr=0.3,0.1

Type RM Length L Ch R = 1,4954,459,459,459
BEGIN DESCRIPTION:
Stream HEN-2 5.0
END DESCRIPTION:
XS GIS Cut Line= 3
      2320683.24      7039487.65      2320761.16      7038951.38
      2320697.00      7038144.83
#Sta/Elev= 30
  4466.6  711.18  4484.4  708.22  4504.6  706.29  4625.9  703.00  4656.2  701.58
  4737.1  701.35  4767.4  698.91  4807.8  697.85  4816.2  696.65  4868.4  694.68
  4878.5  695.64  4908.9  695.15  4939.2  695.56  4979.6  693.69  5000.3  691.40
  5002.1  690.90  5013.1  691.40  5019.9  691.54  5040.0  695.57  5090.1  695.16
  5110.2  694.39  5120.2  695.20  5140.3  694.41  5411.2  698.33  5491.4  698.60
  5641.9  701.57  5702.1  701.04  5728.3  703.43  5752.2  704.00  5817.6  703.49
#Mann=3,-1,0
  4466.6    0.05       0  5000.3   0.033       0  5013.1    0.05       0
Bank Sta=5000.3,5013.1
Exp/Cntr=0.3,0.1

Type RM Length L Ch R = 1,4495,547,547,547
BEGIN DESCRIPTION:
Stream HEC-2 4.5
END DESCRIPTION:
XS GIS Cut Line= 3
      2321723.78      7039486.06      2320877.31      7038501.68
      2320725.12      7038206.81
#Sta/Elev= 30
  4169.7  700.79  4184.5  699.69  4227.3  699.04  4305.2  699.43  4343.1  698.48
  4368.8  698.65  4411.6  696.83  4432.5  698.69  4461.0  698.84  4496.1  698.28
  4546.6  695.20  4610.2  695.84  4702.4  693.83  4929.5  692.52  4957.0  690.93
  4971.3  688.57  5021.9  688.18  5023.7  687.68  5034.7  688.18  5056.8  691.97
  5085.4  693.91  5155.6  693.38  5368.5  695.16  5541.8  698.41  5558.3  697.78
  5608.3  698.63  5624.8  700.11  5630.4  699.30  5661.2  701.15  5799.8  702.49
#Mann=4,-1,0
  4169.7   0.075       0  4343.1    0.05       0  5021.9   0.033       0
  5034.7    0.05       0
Bank Sta=5021.9,5034.7
Exp/Cntr=0.3,0.1

Type RM Length L Ch R = 1,3948,495,495,495
BEGIN DESCRIPTION:
Stream HEC-2 4.4
END DESCRIPTION:
XS GIS Cut Line= 3
      2321985.31      7039200.72      2321576.35      7038515.95
      2321585.86      7038145.06
#Sta/Elev= 30
  4369.6  693.03  4432.4  692.68  4484.4  692.14  4548.1  693.91  4570.7  693.97
  4615.0  692.26  4638.3  690.78  4666.1  685.89  4708.9  684.80  4884.0  688.63
  4942.4  688.15  4957.9  687.49  4964.5  685.89  5015.7  684.16  5017.7  683.66
  5029.7  684.16  5031.9  685.50  5037.7  685.55  5059.1  688.77  5068.9  692.21
  5074.7  692.68  5080.9  695.05  5090.3  695.53  5154.5  694.94  5243.2  696.72
  5263.2  695.09  5273.2  692.39  5283.2  692.19  5373.2  694.00  5538.2  700.11
#Mann=6,-1,0
  4369.6   0.075       0  4432.4    0.05       0  4484.4   0.075       0
  4548.1    0.05       0  5015.7   0.033       0  5029.7    0.05       0
Bank Sta=5015.7,5029.7
Exp/Cntr=0.3,0.1

Type RM Length L Ch R = 1,3453,1366,1366,1366
BEGIN DESCRIPTION:
Stream HEC-2 4.3
END DESCRIPTION:
XS GIS Cut Line= 3
      2322004.33      7039167.40      2322037.61      7038710.91
      2322441.52      7038254.73
#Sta/Elev= 30
  4643.3  692.82  4662.7  692.25  4720.9  689.50  4741.0  684.60  4761.0  683.08
  4763.9  682.42  4765.9  681.92  4776.2  681.92  4778.2  682.42  4781.2  684.87
  4871.3  687.22  4891.4  688.43  4901.4  688.28  4941.5  684.24  4951.5  683.72
  4971.6  683.86  4991.6  683.22  5001.6  684.32  5031.7  684.29  5041.8  685.55
  5049.0  687.96  5054.1  688.28  5216.0  690.09  5428.4  690.30  5542.2  691.70
  5598.2  694.57  5626.7  699.62  5669.3  705.21  5683.5  707.70  5710.3  708.88
#Mann=4,-1,0
  4643.3   0.075       0  4662.7    0.05       0  4763.9   0.033       0
  4778.2    0.05       0
Bank Sta=4763.9,4778.2
Exp/Cntr=0.3,0.1

Type RM Length L Ch R = 1,2087,180,180,180
BEGIN DESCRIPTION:
Stream HEC-2 4.2
END DESCRIPTION:
XS GIS Cut Line= 4
      2321994.85      7039210.22      2322865.04      7039100.85
      2323040.98      7039034.28      2323611.65      7038948.68
#Sta/Elev= 30
  3896.6  693.49  3939.5  693.22  4045.8  691.55  4178.5  689.89  4314.2  684.51
  4414.7  682.81  4434.9  680.82  4500.1  680.84  4575.5  684.60  4580.5  682.76
  4655.9  686.21  4676.8  684.57  4736.3  686.01  4741.4  684.20  4786.7  685.33
  4792.0  683.68  4822.2  682.99  4916.9  683.41  4982.9  678.91  4984.9  678.41
  4997.3  678.91  5050.8  679.12  5094.0  684.27  5222.1  685.73  5253.0  690.37
  5296.2  700.69  5313.7  702.40  5445.1  703.67  5498.5  702.56  5538.8  699.60
#Mann=6,-1,0
  3896.6   0.075       0  3939.5    0.05       0  4045.8   0.075       0
  4314.2    0.05       0  4982.9   0.033       0  4997.3    0.05       0
#XS Ineff=2,0
    0.00 4888.70  691.42 5111.30    0.00  691.42
Permanent Ineff=
       F       F
Bank Sta=4982.9,4997.3
Exp/Cntr=0.3,0.1

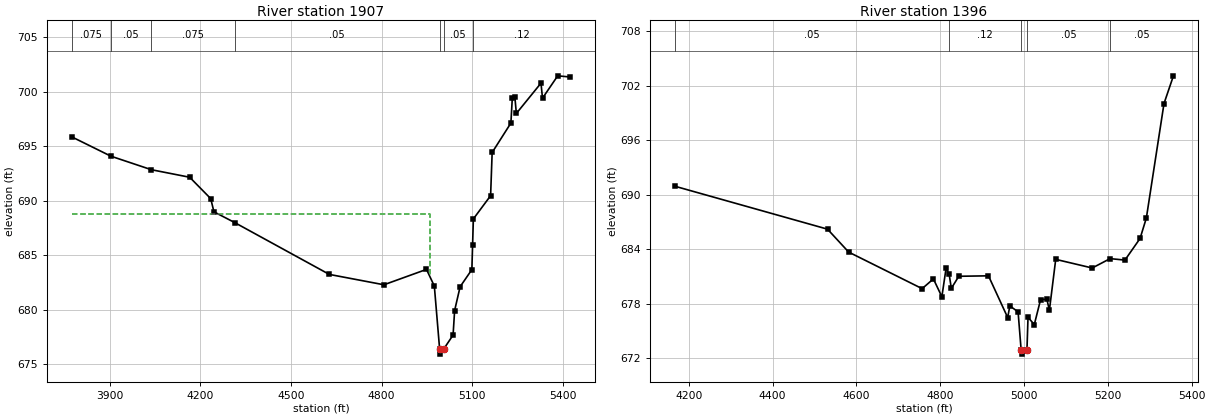
Type RM Length L Ch R = 1,1907,511,511,511
BEGIN DESCRIPTION:
Stream HEN-2 4.0
END DESCRIPTION:
XS GIS Cut Line= 4
      2321930.05      7039313.51      2323066.83      7039194.33
      2323383.12      7039143.91      2323571.03      7039166.82
#Sta/Elev= 30
  3773.4  695.86  3903.7  694.08  4037.8  692.84  4164.5  692.15  4234.2  690.19
  4244.9  688.98  4313.2  688.00  4627.1  683.24  4808.0  682.29  4949.0  683.70
  4975.0  682.17  4992.4  676.43  4994.4  675.93  5006.8  676.43  5037.1  677.68
  5042.2  679.93  5060.4  682.11  5099.3  683.68  5101.7  685.91  5104.3  688.33
  5161.4  690.46  5166.5  694.42  5228.6  697.12  5233.2  699.38  5241.7  699.52
  5246.7  698.00  5328.3  700.78  5333.3  699.40  5383.7  701.45  5426.0  701.34
#Mann=7,-1,0
  3773.4   0.075       0  3903.7    0.05       0  4037.8   0.075       0
  4313.2    0.05       0  4992.4    0.04       0  5006.8    0.05       0
  5101.7    0.12       0
#XS Ineff=2,0
    0.00 4959.00  688.82               0
Permanent Ineff=
       F       F
Bank Sta=4992.4,5006.8
Exp/Cntr=0.3,0.1

Type RM Length L Ch R = 1,1396,438,438,438
BEGIN DESCRIPTION:
Stream HEN-2 3.0
END DESCRIPTION:
XS GIS Cut Line= 3
      2322557.88      7039580.63      2323379.00      7039460.00
      2323679.01      7039259.99
#Sta/Elev= 30
  4166.0  690.95  4531.0  686.22  4581.5  683.70  4756.8  679.68  4783.7  680.75
  4803.9  678.79  4814.0  681.93  4821.4  681.24  4826.5  679.71  4844.3  681.04
  4915.1  681.09  4961.0  676.50  4966.1  677.78  4985.8  677.13  4993.0  672.98
  4995.0  672.48  5007.0  672.98  5009.5  676.53  5024.5  675.73  5039.5  678.48
  5054.5  678.51  5060.5  677.30  5075.6  682.90  5162.7  681.95  5205.4  682.98
  5240.8  682.82  5276.9  685.20  5291.9  687.45  5334.0  700.03  5356.5  703.08
#Mann=5,-1,0
  4166.0    0.05       0  4821.4    0.12       0  4993.0    0.07       0
  5007.0    0.05       0  5205.4    0.05       0
Bank Sta=4993,5007
Exp/Cntr=0.3,0.1