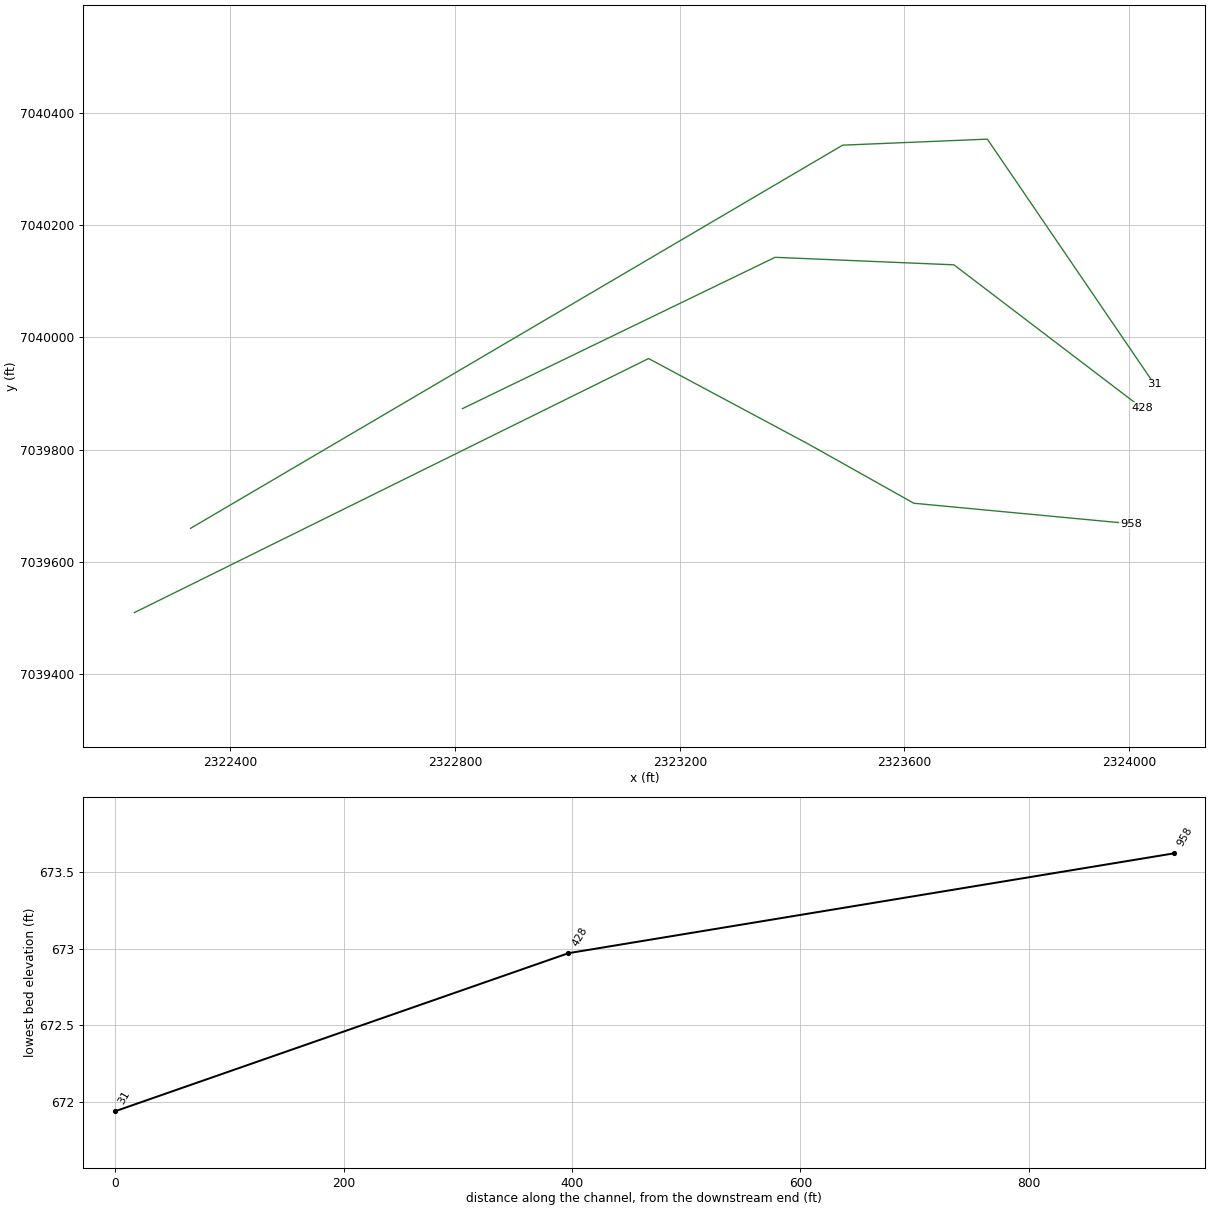
HEC-RAS study Stream HEN-2.prj: Stream HEN-2 Base Level Engineering

--- Stream HEN-2.g01 (geometry) --- (continued)

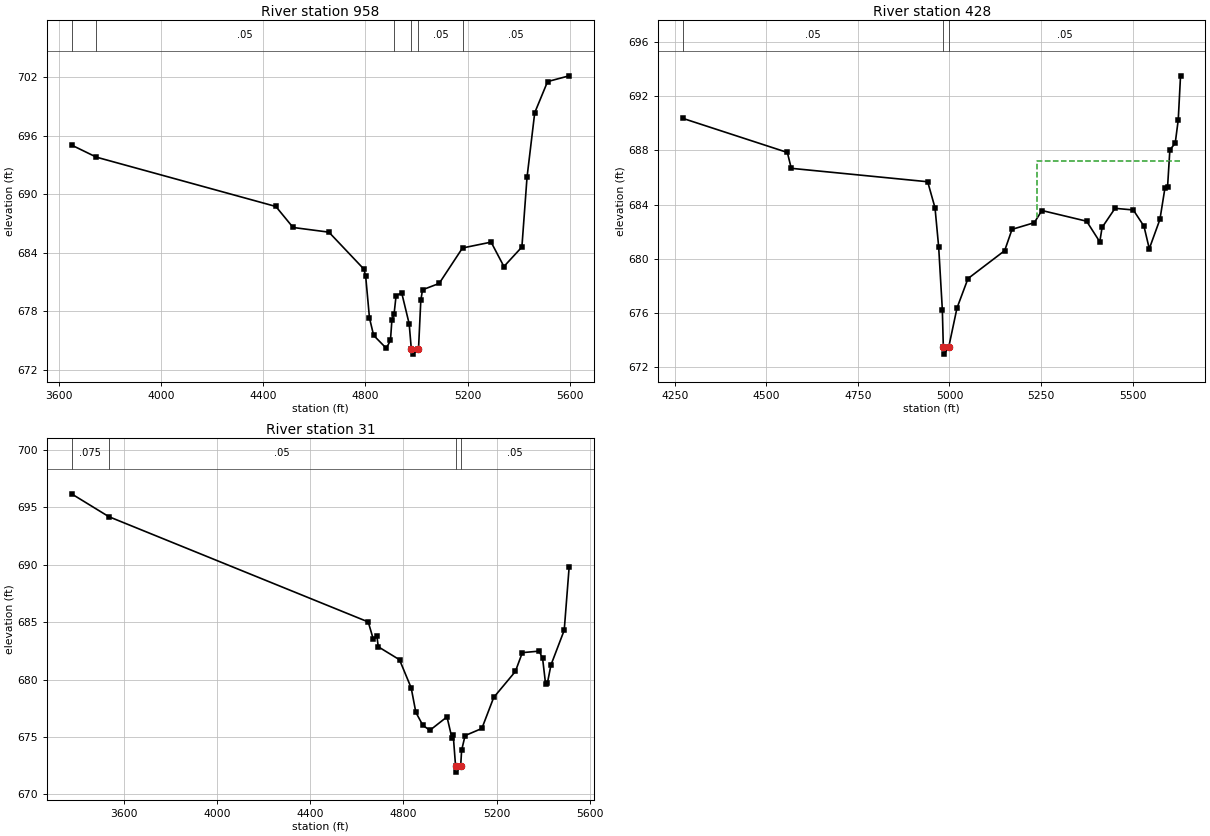
Type RM Length L Ch R = 1,958,530,530,530
BEGIN DESCRIPTION:
Stream HEN-2 2.0
END DESCRIPTION:
XS GIS Cut Line= 5
      2322229.01      7039510.00      2323144.37      7039962.26
      2323429.00      7039810.00      2323616.60      7039704.68
      2324002.95      7039668.19
#Sta/Elev= 30
  3650.4  695.03  3747.8  693.79  4449.9  688.74  4517.2  686.59  4657.4  686.11
  4794.2  682.33  4801.4  681.57  4816.2  677.32  4832.5  675.54  4882.0  674.22
  4898.3  675.03  4904.0  677.13  4912.6  677.76  4920.2  679.59  4942.2  679.90
  4971.5  676.73  4980.0  674.12  4985.0  673.62  5008.0  674.12  5017.1  679.14
  5023.8  680.21  5088.9  680.86  5180.2  684.49  5292.1  685.09  5342.3  682.59
  5412.6  684.59  5432.7  691.73  5462.8  698.34  5513.1  701.53  5597.4  702.12
#Mann=6,-1,0
  3650.4   0.075       0  3747.8    0.05       0  4912.6    0.12       0
  4980.0    0.07       0  5008.0    0.05       0  5180.2    0.05       0
Bank Sta=4980,5008
Exp/Cntr=0.3,0.1

Type RM Length L Ch R = 1,428,397,397,397
BEGIN DESCRIPTION:
Stream HEN-2 1.5
END DESCRIPTION:
XS GIS Cut Line= 4
      2322812.96      7039873.07      2323369.61      7040142.49
      2323688.02      7040129.13      2324022.86      7039874.12
#Sta/Elev= 30
  4272.6  690.35  4557.5  687.84  4568.2  686.67  4940.5  685.68  4960.5  683.76
  4970.5  680.87  4980.5  676.25  4983.2  673.47  4985.2  672.97  4997.8  673.47
  5020.5  676.37  5050.5  678.54  5150.6  680.60  5170.7  682.17  5231.4  682.66
  5252.2  683.56  5374.3  682.77  5410.2  681.25  5416.5  682.31  5451.8  683.72
  5501.7  683.60  5530.8  682.40  5545.3  680.74  5574.4  682.91  5588.0  685.21
  5595.2  685.30  5601.5  688.04  5616.0  688.51  5624.3  690.23  5630.6  693.49
#Mann=3,-1,0
  4272.6    0.05       0  4983.2    0.04       0  4997.8    0.05       0
#XS Ineff=2,0
       0                 5239.20    0.00  687.19
Permanent Ineff=
       F       F
Bank Sta=4983.2,4997.8
Exp/Cntr=0.3,0.1

Type RM Length L Ch R = 1,31,0,0,0
BEGIN DESCRIPTION:
Stream HEN-2 1.0
END DESCRIPTION:
XS GIS Cut Line= 4
      2322328.97      7039659.98      2323489.96      7040342.19
      2323747.54      7040352.92      2324044.97      7039916.42
#Sta/Elev= 30
  3377.3  696.16  3537.3  694.17  4648.9  685.01  4670.4  683.52  4686.1  683.76
  4691.9  682.85  4783.0  681.72  4833.0  679.27  4853.0  677.14  4883.1  676.01
  4913.1  675.58  4986.5  676.75  5007.2  674.94  5013.2  675.15  5023.3  672.44
  5025.5  671.94  5045.0  672.44  5049.1  673.83  5064.0  675.12  5135.9  675.74
  5186.7  678.44  5279.5  680.70  5309.4  682.34  5381.2  682.47  5396.1  681.86
  5408.8  679.65  5417.1  679.72  5432.0  681.26  5488.9  684.29  5509.9  689.76
#Mann=4,-1,0
  3377.3   0.075       0  3537.3    0.05       0  5023.3   0.033       0
  5045.0    0.05       0
Bank Sta=5023.3,5045
Exp/Cntr=0.3,0.1

Chan Stop Cuts=-1