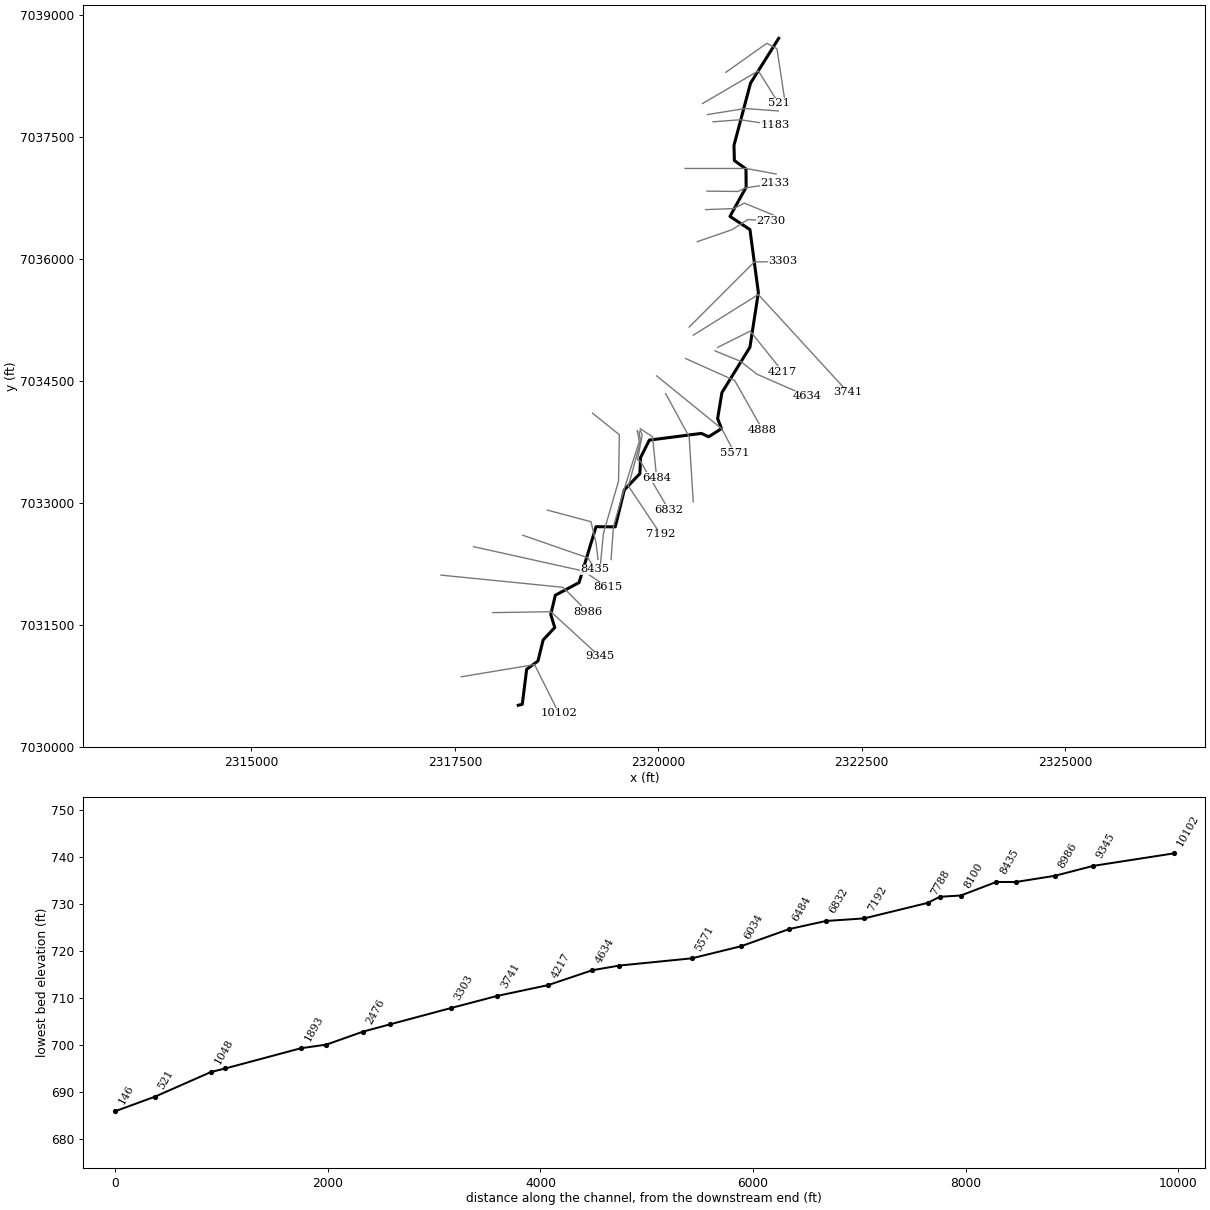
--- Stream HEN-2A.prj (project) ---

Proj Title=Stream HEN-2A Base Level Engineering
Current Plan=p01
Default Exp/Contr=0.3,0.1
English Units
Geom File=g01
Flow File=f01
Plan File=p01
BEGIN DESCRIPTION:
Stream HEN-2A
END DESCRIPTION:

--- Stream HEN-2A.p01 (plan) ---

Plan Title=Multiple Run
Short Identifier=Multiple
Geom File=g01
Flow File=f01
Subcritical Flow
K Sum by GR= 0
Std Step Tol= 0.01
Critical Tol= 0.01
Num of Std Step Trials= 20
Max Error Tol= 0.3
Flow Tol Ratio= 0.001
Split Flow NTrial= 30
Split Flow Tol= 0.02
Split Flow Ratio= 0.02
Log Output Level= 0
Friction Slope Method= 0
Unsteady Friction Slope Method= 2
Unsteady Bridges Friction Slope Method= 1
Parabolic Critical Depth
Global Vel Dist=  1 , 1 , 1
Global Log Level= 0
CheckData=True
Encroach Param= -1, 0, 0, 0
BEGIN DESCRIPTION:
Multiple Run
END DESCRIPTION:

--- Stream HEN-2A.f01 (steady flow) ---

Flow Title=Multiple
Number of Profiles=7
Profile Names=10-year,25-year,50-year,1pct_min,100-year,1pct_plu,500-year
River Rch & RM= Stream HEN-2A,Reach-1,10102
     570     784     961     585    1170    2330    1720
River Rch & RM= Stream HEN-2A,Reach-1,8986
     850    1190    1480     914    1820    3640    2760
River Rch & RM= Stream HEN-2A,Reach-1,6034
     894    1260    1560     963    1920    3830    2910
River Rch & RM= Stream HEN-2A,Reach-1,4634
    1100    1560    1950    1210    2410    4800    3660
Boundary for River Rch & Prof#=Stream HEN-2A,Reach-1,1
Up Type=0
Dn Type=3
Dn Slope=0.001
Boundary for River Rch & Prof#=Stream HEN-2A,Reach-1,2
Up Type=0
Dn Type=3
Dn Slope=0.001
Boundary for River Rch & Prof#=Stream HEN-2A,Reach-1,3
Up Type=0
Dn Type=3
Dn Slope=0.001
Boundary for River Rch & Prof#=Stream HEN-2A,Reach-1,4
Up Type=0
Dn Type=3
Dn Slope=0.001
Boundary for River Rch & Prof#=Stream HEN-2A,Reach-1,5
Up Type=0
Dn Type=3
Dn Slope=0.001
Boundary for River Rch & Prof#=Stream HEN-2A,Reach-1,6
Up Type=0
Dn Type=3
Dn Slope=0.001
Boundary for River Rch & Prof#=Stream HEN-2A,Reach-1,7
Up Type=0
Dn Type=3
Dn Slope=0.001

--- Stream HEN-2A.g01 (geometry) ---

Geom Title=Existing Conditions

River Reach=Stream HEN-2A,Reach-1
Reach XY= 30
      2318279.00      7030510.00      2318328.22      7030521.76
      2318382.16      7030951.66      2318521.14      7031053.81
      2318584.52      7031312.43      2318727.38      7031466.03
      2318678.29      7031625.06      2318734.46      7031862.46
      2319025.97      7032018.01      2319234.58      7032705.24
      2319471.00      7032703.61      2319582.54      7033158.53
      2319773.54      7033357.55      2319781.24      7033554.07
      2319889.61      7033770.06      2320529.01      7033852.41
      2320618.30      7033810.80      2320775.96      7033911.42
      2320728.61      7034035.00      2320781.24      7034354.07
      2321125.25      7034911.55      2321229.20      7035584.92
      2321125.49      7036358.75      2320879.92      7036520.48
      2321078.94      7036880.03      2321077.02      7037104.33
      2320934.36      7037207.30      2320929.52      7037394.78
      2321132.83      7038158.42      2321479.00      7038710.00

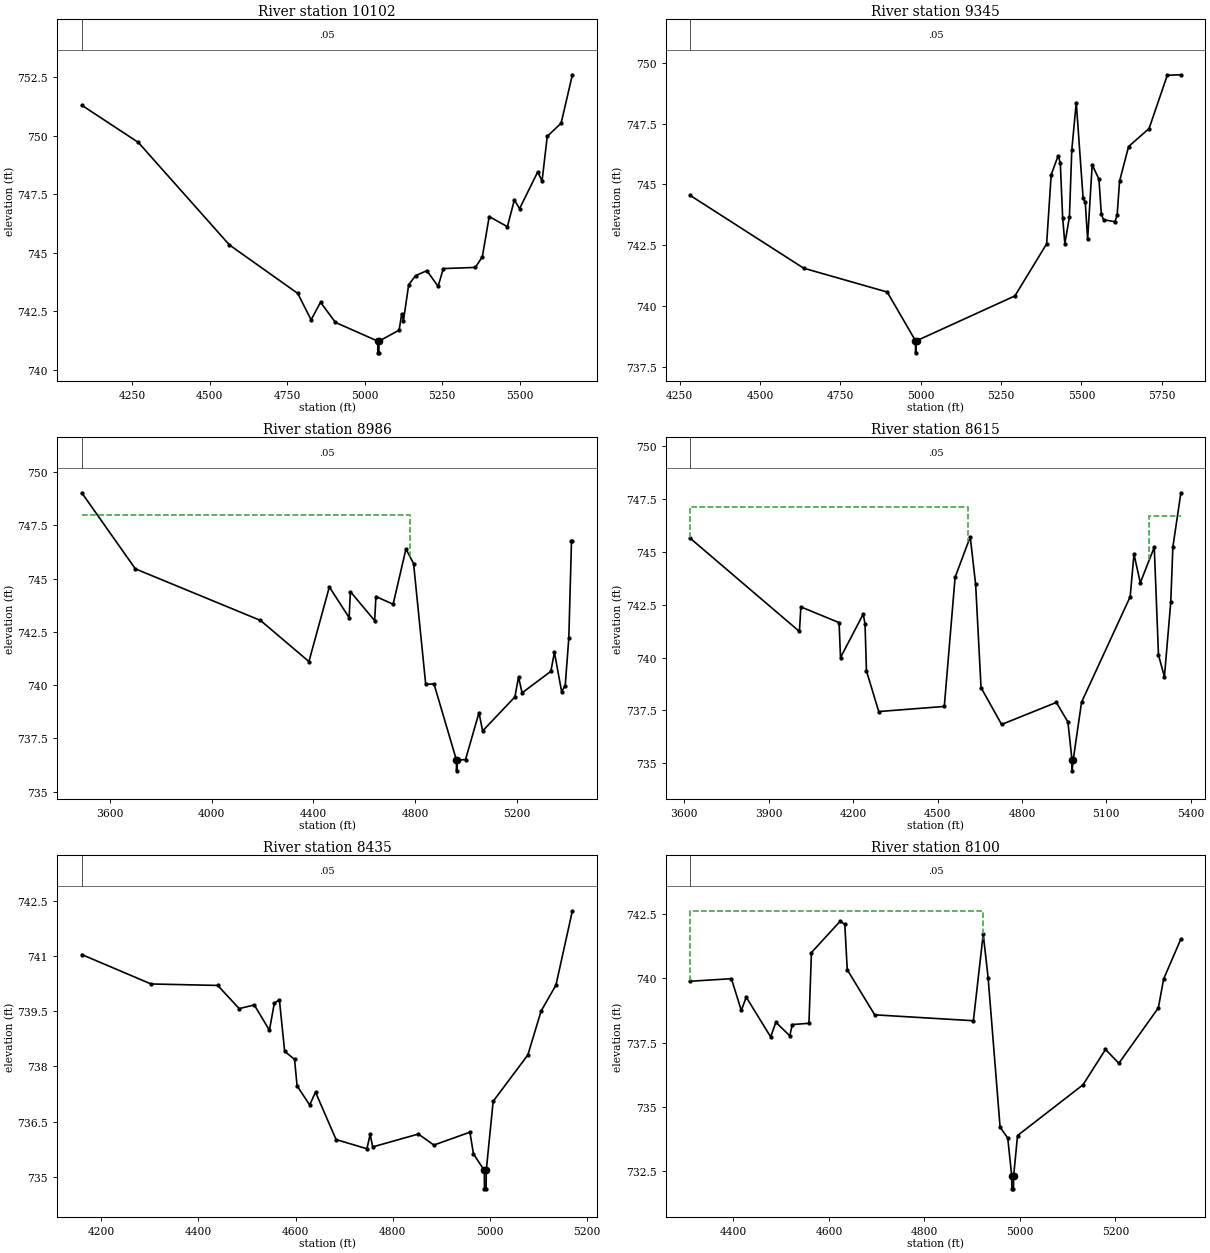
Type RM Length L Ch R = 1,10102,757,757,757
BEGIN DESCRIPTION:
Stream HEN-2A 22.0
END DESCRIPTION:
XS GIS Cut Line= 3
      2317578.97      7030860.00      2318479.00      7031010.00
      2318779.02      7030409.96
#Sta/Elev= 30
  4087.1  751.31  4269.6  749.72  4563.6  745.34  4784.1  743.27  4827.2  742.14
  4857.6  742.89  4905.8  742.03  5042.3  741.23  5042.5  740.73  5046.0  740.73
  5046.3  741.23  5111.3  741.70  5119.7  742.40  5125.3  742.11  5142.1  743.64
  5164.5  744.03  5200.8  744.24  5237.1  743.57  5253.9  744.33  5357.3  744.38
  5379.7  744.83  5402.0  746.55  5460.7  746.12  5483.1  747.26  5499.9  746.89
  5558.6  748.46  5572.5  748.07  5589.3  749.98  5634.0  750.54  5670.4  752.61
#Mann=1,-1,0
  4087.1    0.05       0
Bank Sta=5042.3,5046.3
Exp/Cntr=0.3,0.1

Type RM Length L Ch R = 1,9345,359,359,359
BEGIN DESCRIPTION:
Stream HEN-2A 21.0
END DESCRIPTION:
XS GIS Cut Line= 3
      2317966.27      7031648.63      2318679.00      7031660.00
      2319279.03      7031109.97
#Sta/Elev= 30
  4282.8  744.55  4635.6  741.56  4895.6  740.58  4983.6  738.58  4983.9  738.08
  4987.6  738.58  5293.1  740.42  5391.8  742.56  5406.0  745.40  5427.6  746.18
  5434.3  745.90  5441.7  743.63  5448.5  742.57  5462.7  743.66  5470.1  746.42
  5484.0  748.37  5505.3  744.44  5512.0  744.27  5519.4  742.74  5533.6  745.81
  5554.6  745.22  5562.0  743.79  5568.8  743.55  5604.5  743.47  5611.3  743.75
  5618.7  745.13  5646.8  746.56  5710.6  747.30  5767.3  749.49  5809.6  749.51
#Mann=1,-1,0
  4282.8    0.05       0
Bank Sta=4983.6,4987.6
Exp/Cntr=0.3,0.1

Type RM Length L Ch R = 1,8986,371,371,371
BEGIN DESCRIPTION:
Stream HEN-2A 20.0
END DESCRIPTION:
XS GIS Cut Line= 3
      2317329.04      7032110.00      2318829.00      7031960.00
      2319129.00      7031660.00
#Sta/Elev= 30
  3487.8  749.03  3698.8  745.46  4191.3  743.04  4382.2  741.11  4462.6  744.61
  4540.5  743.17  4545.5  744.39  4641.0  743.03  4646.0  744.16  4713.8  743.80
  4764.1  746.39  4794.2  745.71  4842.0  740.04  4874.6  740.06  4963.1  736.48
  4963.3  735.98  4967.1  736.48  4998.8  736.51  5051.8  738.71  5066.0  737.85
  5193.2  739.45  5207.4  740.38  5221.5  739.64  5334.7  740.65  5348.8  741.54
  5377.1  739.70  5391.2  739.97  5405.4  742.21  5416.0  746.75  5419.5  746.75
#Mann=1,-1,0
  3487.8    0.05       0
#XS Ineff=2,0
    0.00 4780.30  747.97               0
Permanent Ineff=
       F       F
Bank Sta=4963.1,4967.1
Exp/Cntr=0.3,0.1

Type RM Length L Ch R = 1,8615,180,180,180
BEGIN DESCRIPTION:
Stream HEN-2A 19.0
END DESCRIPTION:
XS GIS Cut Line= 3
      2317729.04      7032459.99      2319079.00      7032160.00
      2319378.97      7031960.02
#Sta/Elev= 30
  3621.4  745.63  4009.3  741.23  4014.5  742.39  4150.2  741.65  4155.3  740.00
  4236.0  742.05  4242.4  741.59  4247.5  739.37  4291.1  737.45  4524.1  737.69
  4562.5  743.79  4616.3  745.70  4635.5  743.45  4654.7  738.58  4727.7  736.84
  4922.3  737.88  4963.3  736.96  4978.0  735.15  4978.2  734.65  4982.0  735.15
  5011.8  737.89  5184.6  742.87  5198.1  744.88  5220.6  743.53  5270.2  745.21
  5285.2  740.12  5306.3  739.09  5328.8  742.61  5336.3  745.22  5364.8  747.78
#Mann=1,-1,0
  3621.4    0.05       0
#XS Ineff=2,0
    0.00 4609.20  747.10 5252.50    0.00  746.70
Permanent Ineff=
       F       F
Bank Sta=4978,4982
Exp/Cntr=0.3,0.1

Type RM Length L Ch R = 1,8435,335,335,335
BEGIN DESCRIPTION:
Stream HEN-2A 18.5
END DESCRIPTION:
XS GIS Cut Line= 3
      2318334.74      7032600.12      2319134.64      7032322.26
      2319220.45      7032184.13
#Sta/Elev= 30
  4160.0  741.04  4302.5  740.24  4439.8  740.20  4483.9  739.57  4515.0  739.67
  4546.1  738.98  4556.2  739.72  4566.6  739.81  4577.4  738.41  4597.8  738.19
  4603.0  737.47  4628.9  736.95  4640.9  737.30  4683.2  736.01  4746.7  735.76
  4753.3  736.15  4758.6  735.81  4852.6  736.16  4884.4  735.86  4958.5  736.21
  4965.9  735.62  4988.2  735.17  4988.5  734.67  4992.0  734.67  4992.2  735.17
  5006.4  737.05  5077.8  738.31  5104.9  739.50  5135.6  740.21  5169.4  742.23
#Mann=1,-1,0
  4160.0    0.05       0
Bank Sta=4988.2,4992.2
Exp/Cntr=0.3,0.1

Type RM Length L Ch R = 1,8100,197,197,197
BEGIN DESCRIPTION:
Stream HEN-2A 18.2
END DESCRIPTION:
XS GIS Cut Line= 4
      2318635.71      7032909.58      2319172.53      7032766.43
      2319235.68      7032501.19      2319258.61      7032303.15
#Sta/Elev= 30
  4309.5  739.89  4395.7  739.99  4416.4  738.75  4426.7  739.27  4477.9  737.72
  4488.8  738.29  4518.0  737.76  4523.2  738.20  4558.1  738.25  4563.3  741.01
  4623.4  742.23  4633.2  742.11  4638.3  740.34  4695.8  738.58  4902.5  738.35
  4923.1  741.73  4933.4  740.02  4958.4  734.20  4974.5  733.77  4982.8  732.29
  4983.0  731.79  4986.5  731.79  4986.8  732.29  4995.0  733.87  5132.1  735.85
  5179.2  737.23  5207.2  736.69  5289.9  738.85  5301.0  739.98  5337.1  741.54
#Mann=1,-1,0
  4309.5    0.05       0
#XS Ineff=2,0
    0.00 4921.60  742.64               0
Permanent Ineff=
       F       F
Bank Sta=4982.8,4986.8
Exp/Cntr=0.3,0.1

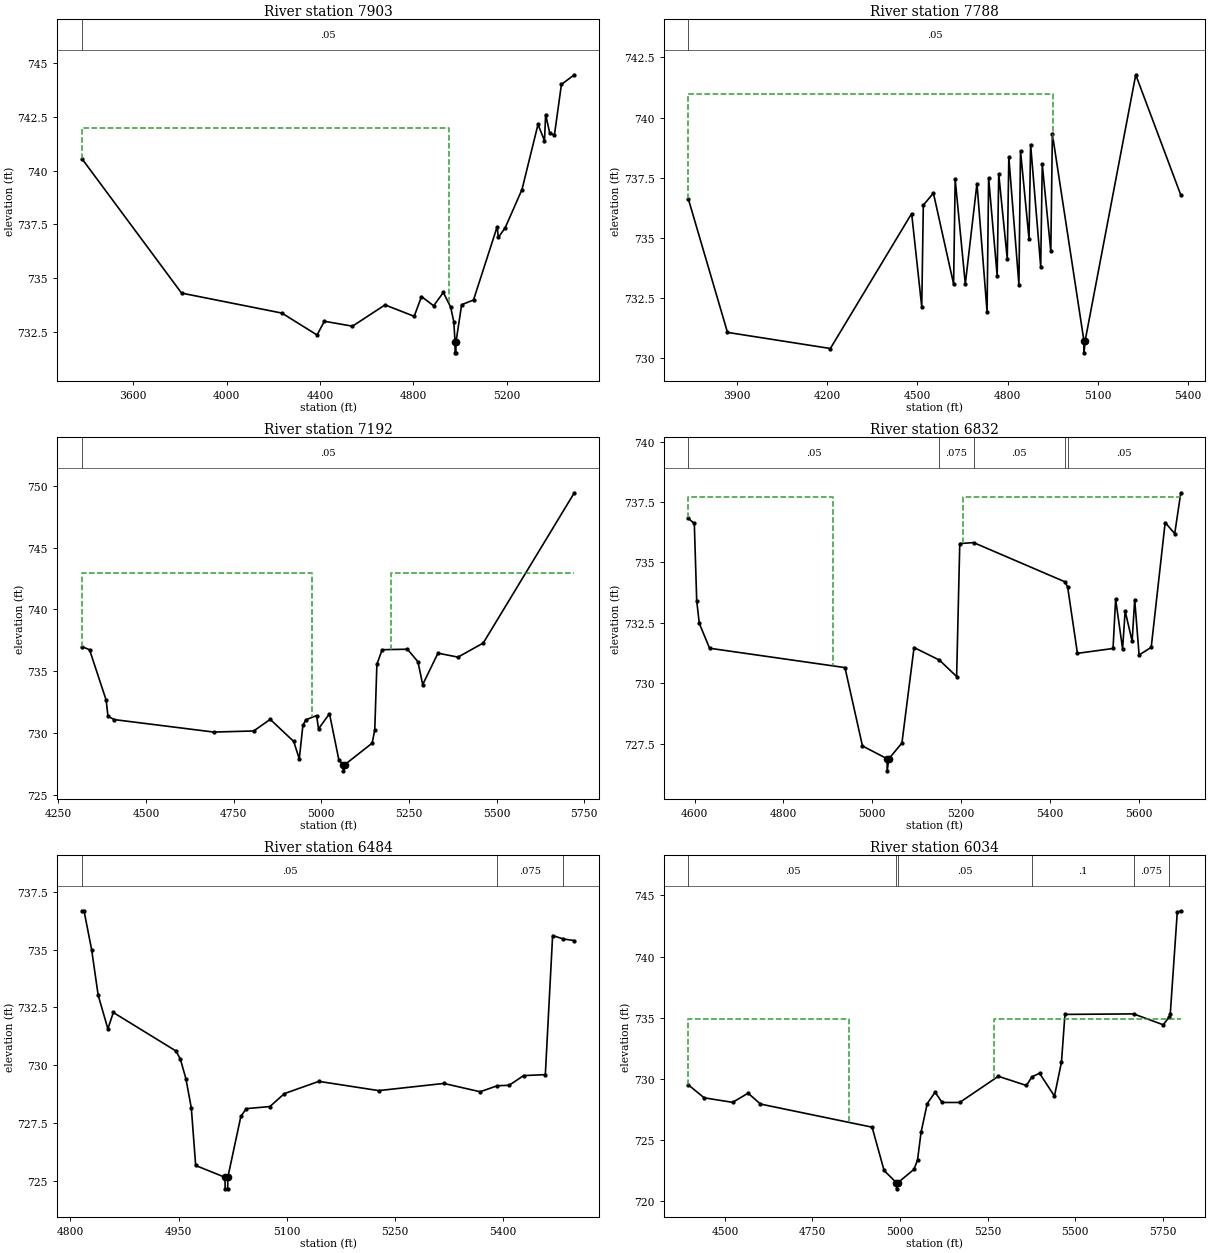
Type RM Length L Ch R = 1,7903,115,115,115
BEGIN DESCRIPTION:
Stream HEN-2A 18.0
END DESCRIPTION:
XS GIS Cut Line= 5
      2319192.68      7034100.29      2319520.85      7033836.03
      2319511.45      7033267.45      2319326.20      7032627.50
      2319281.76      7032175.00
#Sta/Elev= 30
  3379.6  740.56  3807.0  734.30  4237.0  733.37  4387.8  732.35  4419.0  732.99
  4539.5  732.76  4679.1  733.75  4804.2  733.22  4835.4  734.14  4887.5  733.71
  4929.1  734.33  4960.3  733.65  4973.9  732.97  4979.2  732.02  4979.4  731.52
  4982.9  731.52  4983.2  732.02  5007.5  733.76  5058.4  733.98  5159.8  737.39
  5164.8  736.89  5194.1  737.34  5266.2  739.12  5334.8  742.15  5362.6  741.39
  5367.6  742.61  5385.0  741.75  5405.1  741.65  5435.2  744.01  5490.5  744.46
#Mann=1,-1,0
  3379.6    0.05       0
#XS Ineff=2,0
    0.00 4951.60  742.00               0
Permanent Ineff=
       F       F
Bank Sta=4979.2,4983.2
Exp/Cntr=0.3,0.1

Type RM Length L Ch R = 1,7788,596,596,596
BEGIN DESCRIPTION:
Stream HEN-2A 17.0
END DESCRIPTION:
XS GIS Cut Line= 5
      2319740.91      7033888.46      2319766.17      7033755.83
      2319595.66      7033216.92      2319447.80      7032705.49
      2319419.45      7032300.51
#Sta/Elev= 30
  3737.7  736.62  3868.0  731.07  4210.3  730.40  4480.8  736.01  4514.4  732.13
  4519.6  736.36  4553.2  736.86  4620.4  733.08  4625.6  737.43  4659.3  733.08
  4698.1  737.26  4731.7  731.93  4736.9  737.49  4765.3  733.43  4770.5  737.66
  4798.9  734.13  4804.1  738.35  4837.7  733.05  4843.0  738.61  4871.4  734.95
  4876.6  738.88  4910.2  733.80  4915.4  738.05  4943.8  734.44  4949.0  739.32
  5054.0  730.72  5054.3  730.22  5058.0  730.72  5226.4  741.78  5376.3  736.78
#Mann=1,-1,0
  3737.7    0.05       0
#XS Ineff=2,0
    0.00 4952.60  740.97               0
Permanent Ineff=
       F       F
Bank Sta=5054,5058
Exp/Cntr=0.3,0.1

Type RM Length L Ch R = 1,7192,360,360,360
BEGIN DESCRIPTION:
Stream HEN-2A 16.0
END DESCRIPTION:
XS GIS Cut Line= 5
      2319764.06      7033871.65      2319780.90      7033751.62
      2319639.86      7033233.77      2319629.00      7033210.00
      2320029.02      7032609.97
#Sta/Elev= 30
  4316.7  736.99  4338.6  736.74  4386.1  732.65  4391.2  731.35  4409.2  731.08
  4693.0  730.07  4807.1  730.16  4854.2  731.10  4921.2  729.31  4937.1  727.90
  4947.4  730.61  4955.7  731.06  4986.5  731.41  4992.0  730.33  5023.3  731.56
  5050.3  727.78  5062.9  727.43  5063.2  726.93  5066.9  727.43  5145.0  729.17
  5152.5  730.24  5158.5  735.55  5173.5  736.74  5245.6  736.78  5275.7  735.77
  5289.2  733.91  5332.8  736.46  5389.9  736.14  5462.0  737.28  5721.9  749.45
#Mann=1,-1,0
  4316.7    0.05       0
#XS Ineff=2,0
    0.00 4973.70  742.95 5197.40    0.00  742.95
Permanent Ineff=
       F       F
Bank Sta=5062.9,5066.9
Exp/Cntr=0.3,0.1

Type RM Length L Ch R = 1,6832,348,348,348
BEGIN DESCRIPTION:
Stream HEN-2A 15.0
END DESCRIPTION:
XS GIS Cut Line= 5
      2319776.68      7033892.70      2319801.95      7033833.72
      2319744.50      7033527.25      2319779.00      7033510.00
      2320129.01      7032909.98
#Sta/Elev= 30
  4585.9  736.82  4599.4  736.61  4604.8  733.41  4610.6  732.48  4633.8  731.45
  4938.7  730.65  4978.1  727.41  5033.6  726.88  5033.8  726.38  5037.6  726.88
  5067.0  727.53  5094.3  731.48  5151.5  730.96  5190.2  730.28  5197.3  735.78
  5228.4  735.82  5433.9  734.20  5440.2  733.99  5462.3  731.24  5542.5  731.44
  5548.3  733.48  5564.0  731.43  5569.8  732.99  5585.5  731.74  5591.3  733.46
  5601.2  731.17  5628.5  731.49  5659.9  736.65  5681.4  736.19  5695.1  737.88
#Mann=5,-1,0
  4585.9    0.05       0  5151.5   0.075       0  5228.4    0.05       0
  5433.9   0.075       0  5440.2    0.05       0
#XS Ineff=2,0
    0.00 4911.30  737.70 5203.70    0.00  737.70
Permanent Ineff=
       F       F
Bank Sta=5033.6,5037.6
Exp/Cntr=0.3,0.1

Type RM Length L Ch R = 1,6484,450,450,450
BEGIN DESCRIPTION:
Stream HEN-2A 14.0
END DESCRIPTION:
XS GIS Cut Line= 3
      2319778.97      7033910.02      2319929.00      7033810.00
      2319979.00      7033310.01
#Sta/Elev= 30
  4815.8  736.68  4818.8  736.68  4829.4  734.99  4838.4  733.03  4851.9  731.57
  4859.4  732.28  4946.5  730.61  4952.5  730.25  4960.1  729.41  4967.6  728.14
  4973.6  725.66  5014.2  725.15  5014.5  724.65  5018.0  724.65  5018.2  725.15
  5036.3  727.79  5043.9  728.12  5076.5  728.21  5096.6  728.77  5144.4  729.30
  5227.3  728.90  5317.7  729.21  5368.0  728.85  5391.7  729.11  5408.2  729.13
  5428.3  729.55  5458.4  729.59  5468.5  735.61  5483.3  735.46  5498.6  735.39
#Mann=3,-1,0
  4815.8    0.05       0  5391.7   0.075       0  5483.3    0.05       0
Bank Sta=5014.2,5018.2
Exp/Cntr=0.3,0.1

Type RM Length L Ch R = 1,6034,463,463,463
BEGIN DESCRIPTION:
Stream HEN-2A 13.0
END DESCRIPTION:
XS GIS Cut Line= 3
      2320090.36      7034341.03      2320379.00      7033810.00
      2320429.00      7033009.97
#Sta/Elev= 30
  4395.5  729.52  4440.8  728.46  4521.9  728.09  4566.2  728.84  4601.5  727.95
  4920.2  726.06  4954.4  722.52  4989.7  721.52  4990.1  721.02  4993.9  721.52
  5040.0  722.62  5050.0  723.40  5060.0  725.65  5077.6  727.99  5100.1  728.92
  5120.1  728.08  5170.2  728.08  5280.5  730.22  5360.6  729.47  5376.9  730.18
  5398.2  730.47  5440.8  728.60  5460.8  731.38  5470.8  735.28  5666.9  735.32
  5751.4  734.43  5768.4  735.07  5771.4  735.29  5791.4  743.62  5801.5  743.75
#Mann=6,-1,0
  4395.5    0.05       0  4989.7    0.05       0  4993.9    0.05       0
  5376.9     0.1       0  5666.9   0.075       0  5768.4    0.05       0
#XS Ineff=2,0
    0.00 4853.50  734.87 5269.00    0.00  734.87
Permanent Ineff=
       F       F
Bank Sta=4989.7,4993.9
Exp/Cntr=0.3,0.1

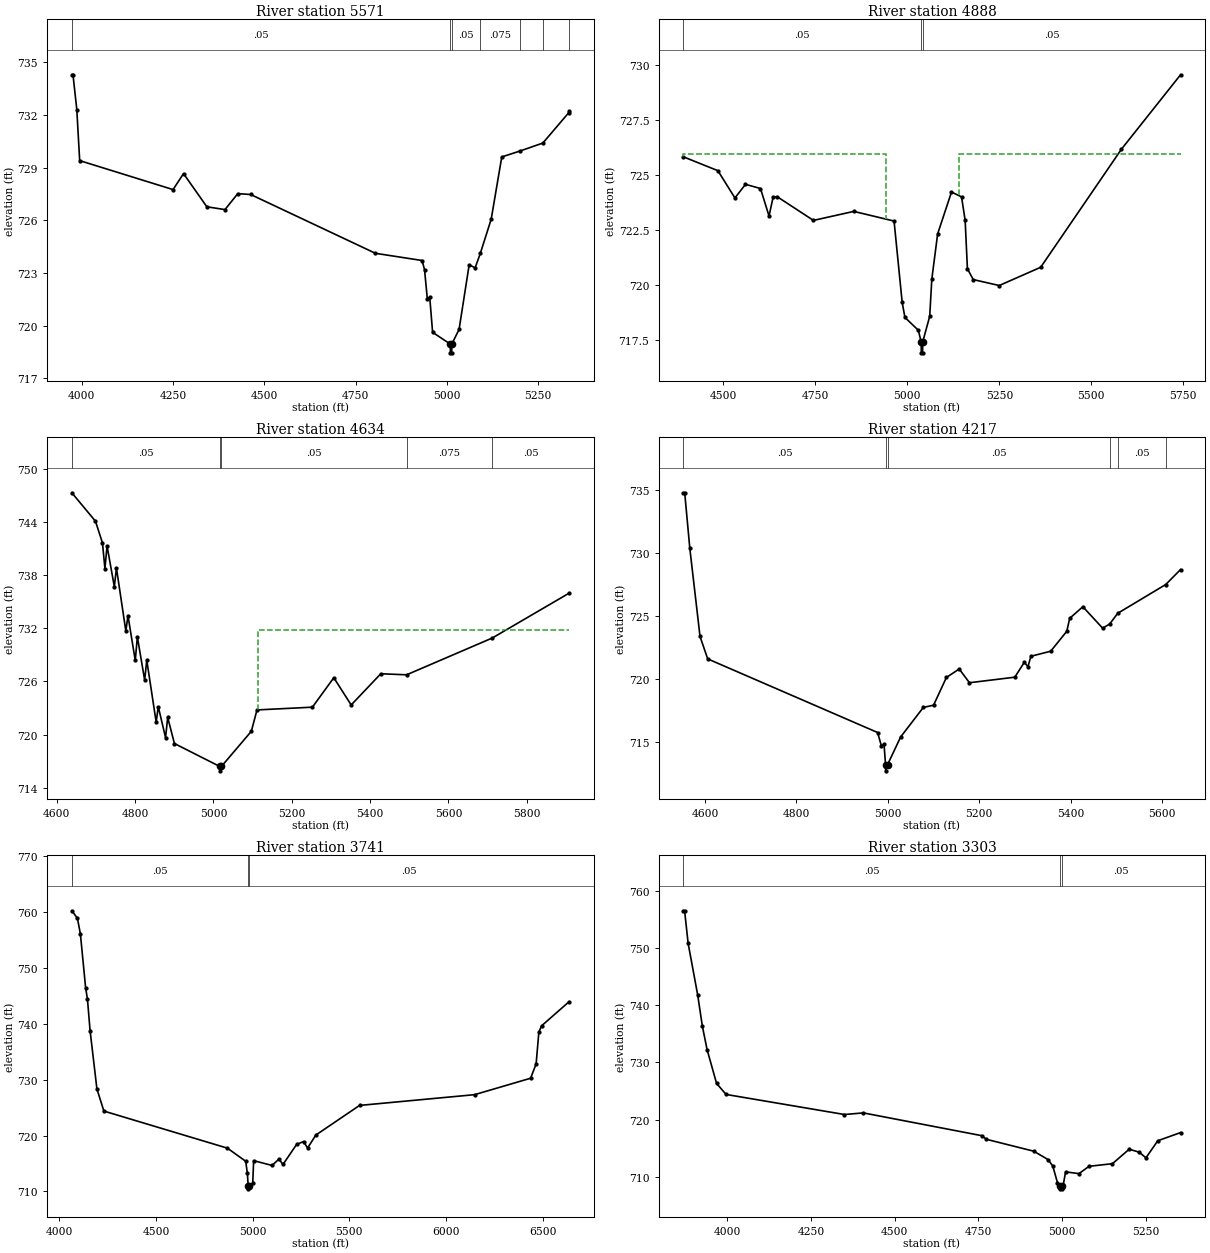
Type RM Length L Ch R = 1,5571,683,683,683
BEGIN DESCRIPTION:
Stream HEN-2A 12.0
END DESCRIPTION:
XS GIS Cut Line= 3
      2319979.01      7034559.99      2320779.00      7033910.00
      2320934.24      7033617.39
#Sta/Elev= 30
  3972.8  734.29  3976.0  734.29  3986.4  732.31  3994.3  729.40  4250.1  727.75
  4278.8  728.66  4342.7  726.77  4392.3  726.61  4427.5  727.52  4462.7  727.47
  4804.6  724.12  4932.4  723.71  4939.1  723.19  4946.8  721.51  4953.3  721.63
  4961.2  719.62  5009.6  718.95  5010.0  718.45  5013.5  718.45  5013.8  718.95
  5033.7  719.78  5061.4  723.47  5077.7  723.29  5092.0  724.12  5121.7  726.06
  5150.7  729.61  5199.6  729.94  5263.2  730.40  5334.2  732.13  5334.8  732.21
#Mann=7,-1,0
  3972.8    0.05       0  5009.6    0.05       0  5013.8    0.05       0
  5092.0   0.075       0  5199.6    0.05       0  5263.2   0.075       0
  5334.2    0.05       0
Bank Sta=5009.6,5013.8
Exp/Cntr=0.3,0.1

Type RM Length L Ch R = 1,4888,254,254,254
BEGIN DESCRIPTION:
Stream HEN-2A 11.0
END DESCRIPTION:
XS GIS Cut Line= 3
      2320336.67      7034772.58      2320938.64      7034502.09
      2321279.04      7033900.23
#Sta/Elev= 30
  4391.3  725.82  4485.0  725.19  4531.3  723.95  4560.0  724.57  4600.8  724.38
  4624.0  723.13  4635.0  723.98  4646.0  724.01  4744.7  722.93  4854.4  723.34
  4963.9  722.90  4985.9  719.21  4993.4  718.52  5029.7  717.94  5037.6  717.41
  5037.9  716.91  5041.5  716.91  5041.8  717.41  5060.8  718.57  5066.5  720.26
  5082.4  722.32  5120.0  724.22  5147.3  724.00  5157.1  722.94  5163.3  720.73
  5179.2  720.24  5249.8  719.97  5362.5  720.80  5582.1  726.17  5742.7  729.55
#Mann=3,-1,0
  4391.3    0.05       0  5037.6   0.033       0  5041.8    0.05       0
#XS Ineff=2,0
    0.00 4940.80  725.95 5139.50    0.00  725.95
Permanent Ineff=
       F       F
Bank Sta=5037.6,5041.8
Exp/Cntr=0.3,0.1

Type RM Length L Ch R = 1,4634,417,417,417
BEGIN DESCRIPTION:
Stream HEN-2A 10.0
END DESCRIPTION:
XS GIS Cut Line= 4
      2320696.63      7034867.32      2321010.28      7034738.91
      2321210.27      7034581.03      2321829.00      7034310.00
#Sta/Elev= 30
  4638.5  747.28  4698.9  744.07  4716.7  741.62  4723.0  738.73  4728.4  741.29
  4747.0  736.69  4752.4  738.79  4776.4  731.68  4781.8  733.43  4800.4  728.37
  4805.8  731.03  4824.4  726.16  4829.8  728.39  4853.8  721.42  4859.2  723.15
  4877.8  719.66  4883.2  721.95  4900.4  719.00  5015.9  716.42  5016.4  715.92
  5020.5  716.42  5096.8  720.38  5111.2  722.79  5252.7  723.10  5307.3  726.42
  5351.7  723.35  5427.3  726.87  5493.2  726.75  5711.9  730.90  5907.7  735.95
#Mann=5,-1,0
  4638.5    0.05       0  5015.9   0.033       0  5020.5    0.05       0
  5493.2   0.075       0  5711.9    0.05       0
#XS Ineff=2,0
       0                 5112.70    0.00  731.83
Permanent Ineff=
       F       F
Bank Sta=5015.9,5020.5
Exp/Cntr=0.3,0.1

Type RM Length L Ch R = 1,4217,476,476,476
BEGIN DESCRIPTION:
Stream HEN-2A 9.0
END DESCRIPTION:
XS GIS Cut Line= 3
      2320729.02      7034910.01      2321129.00      7035110.00
      2321529.00      7034610.01
#Sta/Elev= 30
  4552.9  734.81  4555.7  734.81  4566.9  730.39  4589.2  723.41  4606.0  721.63
  4977.7  715.79  4986.1  714.71  4991.7  714.88  4995.0  713.25  4995.4  712.75
  4999.6  713.25  5028.1  715.44  5077.7  717.78  5100.1  717.96  5128.2  720.16
  5156.2  720.83  5178.6  719.74  5277.8  720.18  5298.6  721.36  5306.6  721.01
  5313.0  721.84  5356.3  722.24  5391.5  723.82  5397.9  724.85  5426.7  725.77
  5469.9  724.07  5485.1  724.39  5503.0  725.25  5607.9  727.53  5640.4  728.72
#Mann=6,-1,0
  4552.9    0.05       0  4995.0   0.033       0  4999.6    0.05       0
  5485.1   0.075       0  5503.0    0.05       0  5607.9   0.075       0
Bank Sta=4995,4999.6
Exp/Cntr=0.3,0.1

Type RM Length L Ch R = 1,3741,438,438,438
BEGIN DESCRIPTION:
Stream HEN-2A 8.0
END DESCRIPTION:
XS GIS Cut Line= 3
      2320429.02      7035060.01      2321229.00      7035560.00
      2322329.03      7034359.97
#Sta/Elev= 30
  4065.0  760.17  4093.9  758.83  4109.2  756.05  4136.3  746.40  4145.8  744.37
  4159.3  738.77  4194.7  728.33  4230.7  724.37  4869.8  717.74  4964.2  715.40
  4973.0  713.24  4977.2  710.97  4977.6  710.47  4981.8  710.97  5000.7  711.53
  5005.4  715.51  5100.6  714.65  5135.7  715.77  5157.3  714.84  5227.6  718.41
  5263.3  718.92  5284.3  717.76  5326.9  720.08  5553.2  725.38  6147.9  727.30
  6438.0  730.24  6466.4  732.81  6480.6  738.49  6494.7  739.61  6636.3  743.90
#Mann=3,-1,0
  4065.0    0.05       0  4977.2   0.033       0  4981.8    0.05       0
Bank Sta=4977.2,4981.8
Exp/Cntr=0.3,0.1

Type RM Length L Ch R = 1,3303,573,573,573
BEGIN DESCRIPTION:
Stream HEN-2A 7.0
END DESCRIPTION:
XS GIS Cut Line= 3
      2320379.01      7035160.01      2321179.00      7035960.00
      2321532.39      7035966.18
#Sta/Elev= 30
  3868.7  756.51  3872.2  756.51  3882.8  750.80  3911.1  741.85  3925.3  736.31
  3939.4  732.22  3967.7  726.32  3996.0  724.39  4349.5  720.88  4406.1  721.16
  4759.6  717.18  4773.8  716.54  4915.2  714.46  4957.6  713.00  4971.8  711.88
  4985.9  708.95  4994.2  708.38  4994.7  707.88  4998.4  707.88  4998.9  708.38
  5002.6  708.38  5010.1  710.85  5050.1  710.54  5080.1  711.82  5150.1  712.28
  5200.1  714.81  5230.1  714.29  5250.1  713.30  5285.5  716.29  5353.5  717.72
#Mann=3,-1,0
  3868.7    0.05       0  4994.2   0.033       0  4998.9    0.05       0
Bank Sta=4994.2,4998.9
Exp/Cntr=0.3,0.1

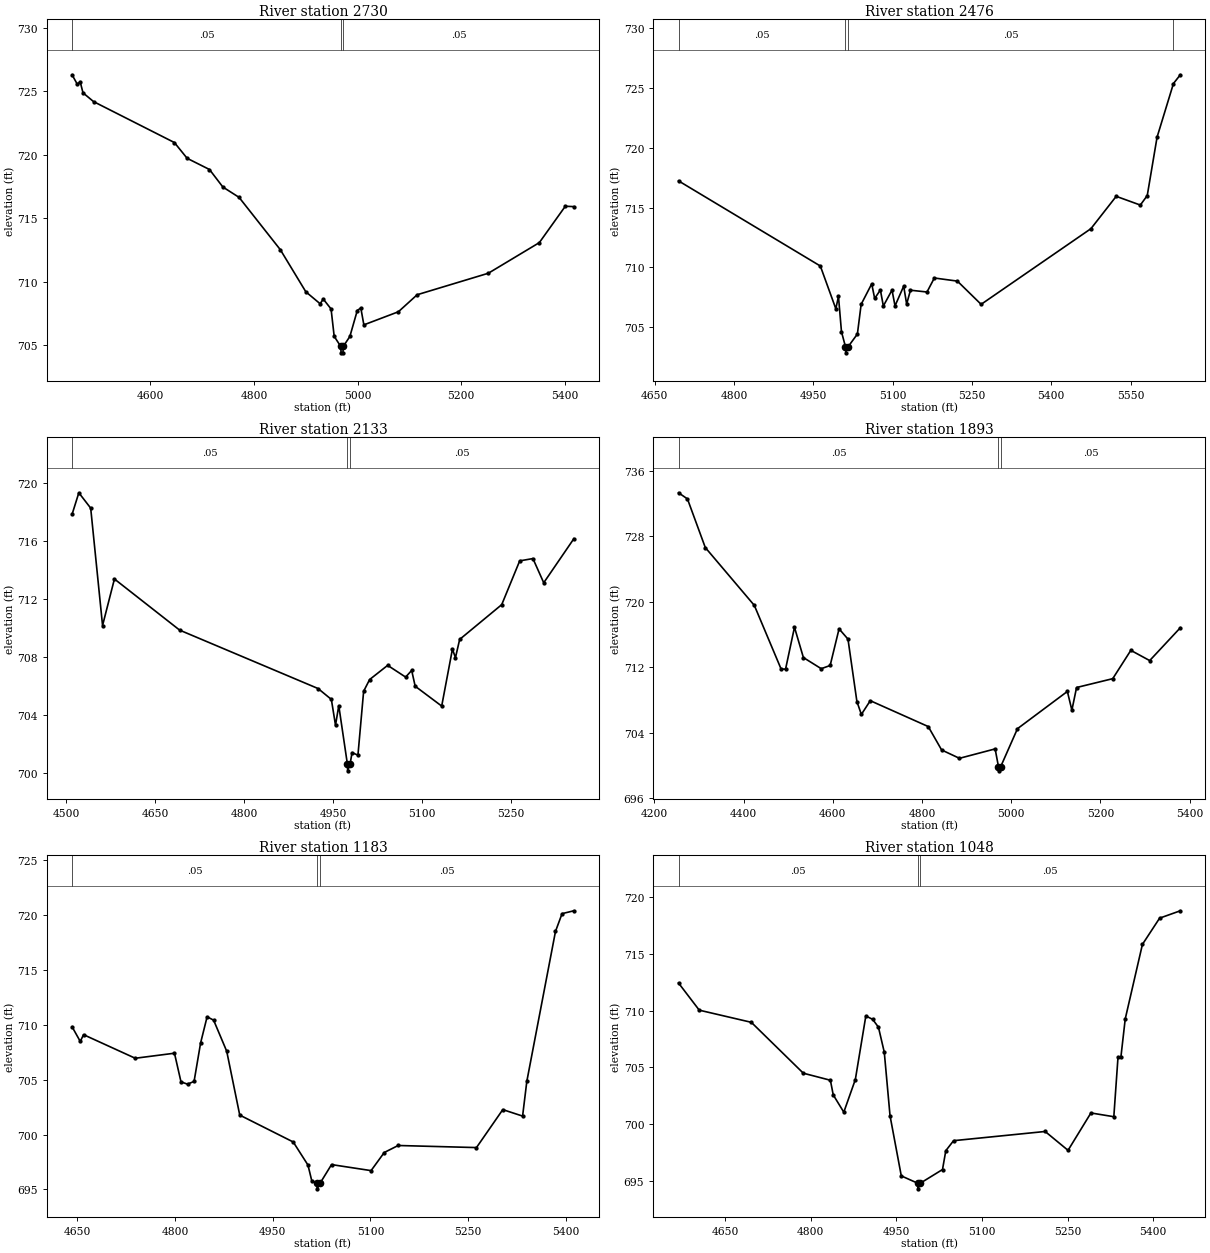
Type RM Length L Ch R = 1,2730,254,254,254
BEGIN DESCRIPTION:
Stream HEN-2A 6.0
END DESCRIPTION:
XS GIS Cut Line= 4
      2320479.01      7036210.00      2320907.13      7036357.73
      2321098.70      7036481.93      2321385.51      7036465.18
#Sta/Elev= 30
  4448.9  726.29  4459.2  725.53  4464.5  725.75  4470.0  724.87  4490.4  724.18
  4646.4  720.96  4671.0  719.72  4714.1  718.84  4740.0  717.46  4771.2  716.65
  4850.9  712.53  4900.1  709.22  4927.7  708.28  4933.7  708.65  4948.8  707.87
  4954.8  705.72  4967.5  704.92  4968.1  704.42  4971.8  704.42  4972.3  704.92
  4985.1  705.71  4999.4  707.75  5006.2  707.95  5012.1  706.62  5078.7  707.65
  5115.0  708.99  5252.3  710.68  5350.8  713.09  5400.9  715.95  5417.4  715.92
#Mann=3,-1,0
  4448.9    0.05       0  4967.5   0.033       0  4972.3    0.05       0
Bank Sta=4967.5,4972.3
Exp/Cntr=0.3,0.1

Type RM Length L Ch R = 1,2476,343,343,343
BEGIN DESCRIPTION:
Stream HEN-2A 5.0
END DESCRIPTION:
XS GIS Cut Line= 4
      2320580.86      7036604.03      2320928.18      7036616.66
      2321056.59      7036684.02      2321479.00      7036510.00
#Sta/Elev= 30
  4694.8  717.23  4963.1  710.12  4992.4  706.55  4997.4  707.58  5003.1  704.63
  5010.7  703.37  5011.3  702.87  5015.5  703.37  5033.2  704.44  5040.3  706.92
  5060.3  708.63  5065.9  707.41  5076.7  708.12  5082.3  706.78  5098.7  708.11
  5104.4  706.79  5120.8  708.44  5126.4  706.94  5133.6  708.10  5164.9  707.95
  5178.8  709.12  5222.4  708.86  5267.3  706.92  5475.1  713.24  5522.9  715.94
  5568.5  715.21  5581.6  716.00  5600.2  720.88  5631.2  725.36  5644.2  726.09
#Mann=4,-1,0
  4694.8    0.05       0  5010.7   0.033       0  5015.5    0.05       0
  5631.2   0.075       0
Bank Sta=5010.7,5015.5
Exp/Cntr=0.3,0.1

Type RM Length L Ch R = 1,2133,240,240,240
BEGIN DESCRIPTION:
Stream HEN-2A 4.5
END DESCRIPTION:
XS GIS Cut Line= 4
      2320597.63      7036831.38      2320980.81      7036827.17
      2321065.01      7036869.27      2321429.16      7036926.10
#Sta/Elev= 30
  4509.6  717.82  4521.0  719.31  4541.0  718.25  4561.0  710.15  4581.0  713.36
  4691.0  709.83  4924.3  705.80  4946.7  705.05  4953.7  703.27  4959.2  704.62
  4973.6  700.62  4974.2  700.12  4978.4  700.62  4981.6  701.38  4991.5  701.20
  5001.1  705.61  5011.2  706.42  5041.6  707.40  5071.9  706.59  5082.1  707.05
  5088.0  705.96  5132.7  704.59  5150.8  708.52  5155.9  707.93  5163.0  709.19
  5233.9  711.59  5264.2  714.61  5286.5  714.77  5304.7  713.10  5355.5  716.14
#Mann=3,-1,0
  4509.6    0.05       0  4973.6   0.033       0  4978.4    0.05       0
Bank Sta=4973.6,4978.4
Exp/Cntr=0.3,0.1

Type RM Length L Ch R = 1,1893,710,710,710
BEGIN DESCRIPTION:
Stream HEN-2A 4.0
END DESCRIPTION:
XS GIS Cut Line= 3
      2320329.05      7037110.00      2321079.00      7037110.00
      2321448.12      7037041.89
#Sta/Elev= 30
  4254.1  733.32  4274.1  732.57  4314.1  726.63  4424.1  719.56  4484.1  711.79
  4494.1  711.77  4514.1  716.89  4534.1  713.19  4574.1  711.83  4594.1  712.22
  4614.1  716.70  4634.1  715.44  4654.1  707.82  4664.1  706.24  4684.1  707.92
  4814.1  704.76  4844.1  701.90  4884.1  700.88  4964.1  702.03  4971.6  699.85
  4972.2  699.35  4976.5  699.85  5014.2  704.50  5126.1  709.05  5136.2  706.76
  5146.7  709.53  5227.8  710.61  5268.4  714.07  5310.7  712.82  5379.4  716.83
#Mann=3,-1,0
  4254.1    0.05       0  4971.6   0.033       0  4976.5    0.05       0
Bank Sta=4971.6,4976.5
Exp/Cntr=0.3,0.1

Type RM Length L Ch R = 1,1183,135,135,135
BEGIN DESCRIPTION:
Stream HEN-2A 3.0
END DESCRIPTION:
XS GIS Cut Line= 3
      2320672.24      7037684.02      2321007.71      7037708.68
      2321436.87      7037644.56
#Sta/Elev= 30
  4642.0  709.83  4654.6  708.49  4659.6  709.11  4739.0  706.96  4799.2  707.42
  4809.2  704.81  4819.2  704.60  4829.3  704.85  4839.3  708.35  4849.3  710.74
  4859.3  710.43  4879.4  707.60  4899.4  701.78  4981.5  699.33  5004.1  697.23
  5010.0  695.79  5017.7  695.56  5018.3  695.06  5022.6  695.56  5040.3  697.27
  5101.0  696.72  5121.2  698.37  5142.6  699.01  5262.8  698.82  5303.2  702.28
  5333.6  701.69  5340.1  704.86  5384.1  718.52  5394.2  720.14  5412.3  720.40
#Mann=3,-1,0
  4642.0    0.05       0  5017.7   0.033       0  5022.6    0.05       0
Bank Sta=5017.7,5022.6
Exp/Cntr=0.3,0.1

Type RM Length L Ch R = 1,1048,527,527,527
BEGIN DESCRIPTION:
Stream HEN-2A 2.0
END DESCRIPTION:
XS GIS Cut Line= 3
      2320603.14      7037772.81      2321066.90      7037846.81
      2321475.21      7037817.30
#Sta/Elev= 30
  4568.6  712.43  4604.9  710.04  4696.1  708.97  4787.2  704.49  4834.6  703.87
  4839.6  702.58  4858.1  701.06  4878.3  703.93  4896.7  709.53  4908.7  709.23
  4918.8  708.54  4929.0  706.34  4939.1  700.74  4958.8  695.45  4987.3  694.81
  4987.9  694.31  4992.2  694.81  5031.0  696.01  5036.8  697.67  5050.4  698.55
  5210.8  699.36  5250.9  697.70  5291.0  700.99  5331.1  700.66  5338.4  705.88
  5343.5  705.91  5351.1  709.27  5381.2  715.83  5411.3  718.14  5447.6  718.79
#Mann=3,-1,0
  4568.6    0.05       0  4987.3   0.033       0  4992.2    0.05       0
Bank Sta=4987.3,4992.2
Exp/Cntr=0.3,0.1

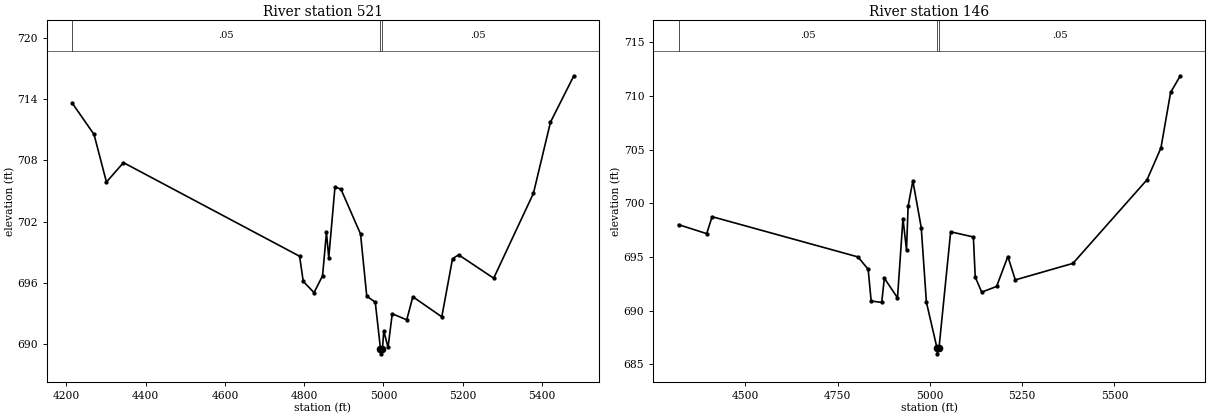
Type RM Length L Ch R = 1,521,375,375,375
BEGIN DESCRIPTION:
Stream HEN-2A 1.0
END DESCRIPTION:
XS GIS Cut Line= 3
      2320543.67      7037908.53      2321229.00      7038310.00
      2321479.02      7037909.97
#Sta/Elev= 30
  4214.4  713.63  4269.8  710.54  4301.1  705.88  4344.1  707.78  4788.5  698.62
  4797.6  696.16  4824.9  695.06  4846.4  696.71  4856.2  700.95  4862.0  698.47
  4877.7  705.40  4892.8  705.18  4942.2  700.80  4957.9  694.71  4979.3  694.13
  4992.5  689.57  4993.2  689.07  4997.5  689.57  5000.8  691.32  5011.6  689.70
  5022.2  692.99  5058.8  692.40  5074.1  694.66  5147.2  692.69  5174.3  698.38
  5189.7  698.76  5278.1  696.47  5378.4  704.78  5421.4  711.74  5480.4  716.28
#Mann=3,-1,0
  4214.4    0.05       0  4992.5   0.033       0  4997.5    0.05       0
Bank Sta=4992.5,4997.5
Exp/Cntr=0.3,0.1

Type RM Length L Ch R = 1,146,0,0,0
BEGIN DESCRIPTION:
Stream HEC-2A 0.5
END DESCRIPTION:
XS GIS Cut Line= 4
      2320829.75      7038292.44      2321333.82      7038649.10
      2321457.46      7038582.52      2321547.82      7037988.06
#Sta/Elev= 30
  4319.4  698.01  4395.6  697.17  4410.4  698.75  4805.5  695.00  4833.0  693.85
  4841.2  690.89  4869.7  690.76  4876.9  693.02  4912.5  691.19  4927.3  698.58
  4936.9  695.65  4941.3  699.74  4954.1  702.09  4976.8  697.74  4990.8  690.78
  5019.8  686.47  5020.4  685.97  5024.8  686.47  5056.5  697.34  5118.0  696.86
  5123.1  693.12  5140.6  691.72  5181.0  692.25  5211.4  695.04  5231.6  692.86
  5387.7  694.40  5588.6  702.20  5626.1  705.16  5652.3  710.33  5678.6  711.88
#Mann=3,-1,0
  4319.4    0.05       0  5019.8    0.05       0  5024.8    0.05       0
Bank Sta=5019.8,5024.8
Exp/Cntr=0.3,0.1

Chan Stop Cuts=-1