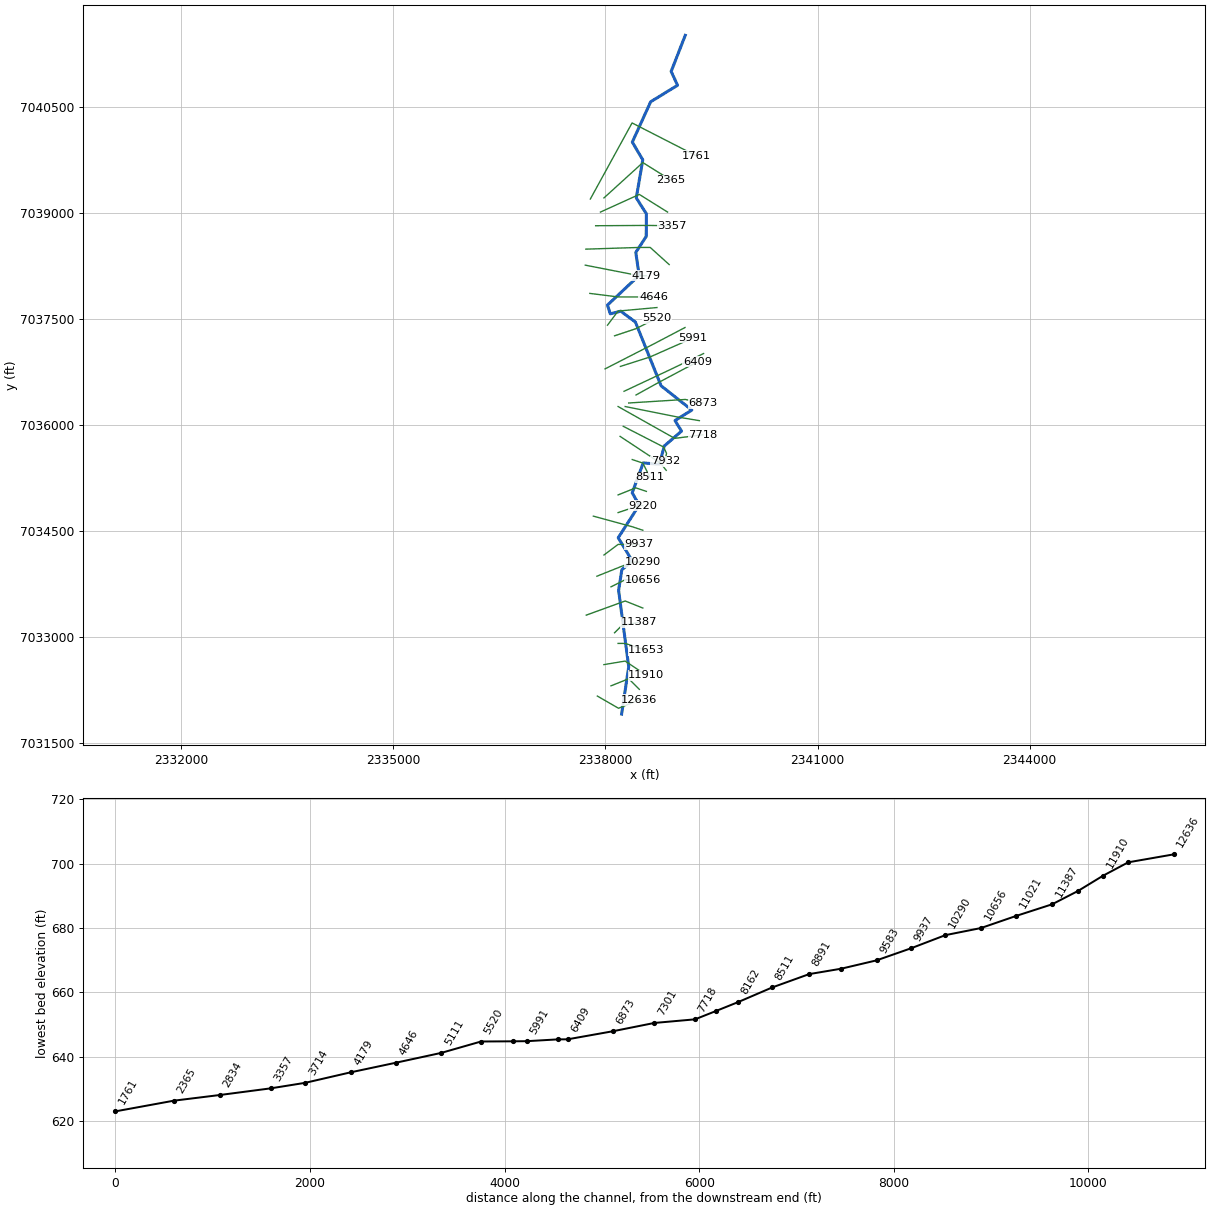
--- Stream HEN-5.prj (project) ---

Proj Title=Stream HEN-5 Base Level Engineering
Current Plan=p01
Default Exp/Contr=0.3,0.1
English Units
Geom File=g01
Flow File=f01
Plan File=p01
BEGIN DESCRIPTION:
Stream HEN-5
END DESCRIPTION:

--- Stream HEN-5.p01 (plan) ---

Plan Title=Multiple Run
Short Identifier=Multiple
Geom File=g01
Flow File=f01
Subcritical Flow
K Sum by GR= 0
Std Step Tol= 0.01
Critical Tol= 0.01
Num of Std Step Trials= 20
Max Error Tol= 0.3
Flow Tol Ratio= 0.001
Split Flow NTrial= 30
Split Flow Tol= 0.02
Split Flow Ratio= 0.02
Log Output Level= 0
Friction Slope Method= 0
Unsteady Friction Slope Method= 2
Unsteady Bridges Friction Slope Method= 1
Parabolic Critical Depth
Global Vel Dist=  1 , 1 , 1
Global Log Level= 0
CheckData=True
Encroach Param= -1, 0, 0, 0
BEGIN DESCRIPTION:
Multiple Run
END DESCRIPTION:

--- Stream HEN-5.f01 (steady flow) ---

Flow Title=Multiple
Number of Profiles=7
Profile Names=10-year,25-year,50-year,1pct_min,100-year,1pct_plu,500-year
River Rch & RM= Stream HEN-5,Reach-1,12636
     463     621     747     447     891    1780    1270
River Rch & RM= Stream HEN-5,Reach-1,11021
     585     795     967     583    1160    2320    1680
River Rch & RM= Stream HEN-5,Reach-1,7718
    1250    1770    2220    1370    2740    5470    4180
River Rch & RM= Stream HEN-5,Reach-1,3357
    1390    1980    2480    1540    3070    6130    4710
Boundary for River Rch & Prof#=Stream HEN-5,Reach-1,1
Up Type=0
Dn Type=3
Dn Slope=0.005
Boundary for River Rch & Prof#=Stream HEN-5,Reach-1,2
Up Type=0
Dn Type=3
Dn Slope=0.005
Boundary for River Rch & Prof#=Stream HEN-5,Reach-1,3
Up Type=0
Dn Type=3
Dn Slope=0.005
Boundary for River Rch & Prof#=Stream HEN-5,Reach-1,4
Up Type=0
Dn Type=3
Dn Slope=0.005
Boundary for River Rch & Prof#=Stream HEN-5,Reach-1,5
Up Type=0
Dn Type=3
Dn Slope=0.005
Boundary for River Rch & Prof#=Stream HEN-5,Reach-1,6
Up Type=0
Dn Type=3
Dn Slope=0.005
Boundary for River Rch & Prof#=Stream HEN-5,Reach-1,7
Up Type=0
Dn Type=3
Dn Slope=0.005

--- Stream HEN-5.g01 (geometry) ---

Geom Title=Existing Conditions

River Reach=Stream HEN-5,Reach-1
Reach XY= 30
      2338229.00      7031910.00      2338329.36      7032580.15
      2338186.30      7033660.08      2338231.97      7033951.68
      2338379.92      7034074.88      2338180.97      7034404.32
      2338477.43      7034866.09      2338378.72      7035039.79
      2338534.39      7035462.79      2338762.72      7035442.68
      2338832.43      7035701.66      2339076.06      7035912.01
      2338984.05      7036062.28      2339221.82      7036209.67
      2338786.81      7036553.79      2338423.89      7037454.89
      2338217.12      7037608.48      2338068.56      7037570.95
      2338029.23      7037694.78      2338477.03      7038115.68
      2338429.26      7038439.72      2338576.85      7038665.97
      2338579.24      7038985.09      2338436.52      7039209.96
      2338527.95      7039749.57      2338380.10      7039999.45
      2338639.52      7040569.79      2339019.90      7040803.25
      2338929.60      7040999.37      2339129.00      7041510.00

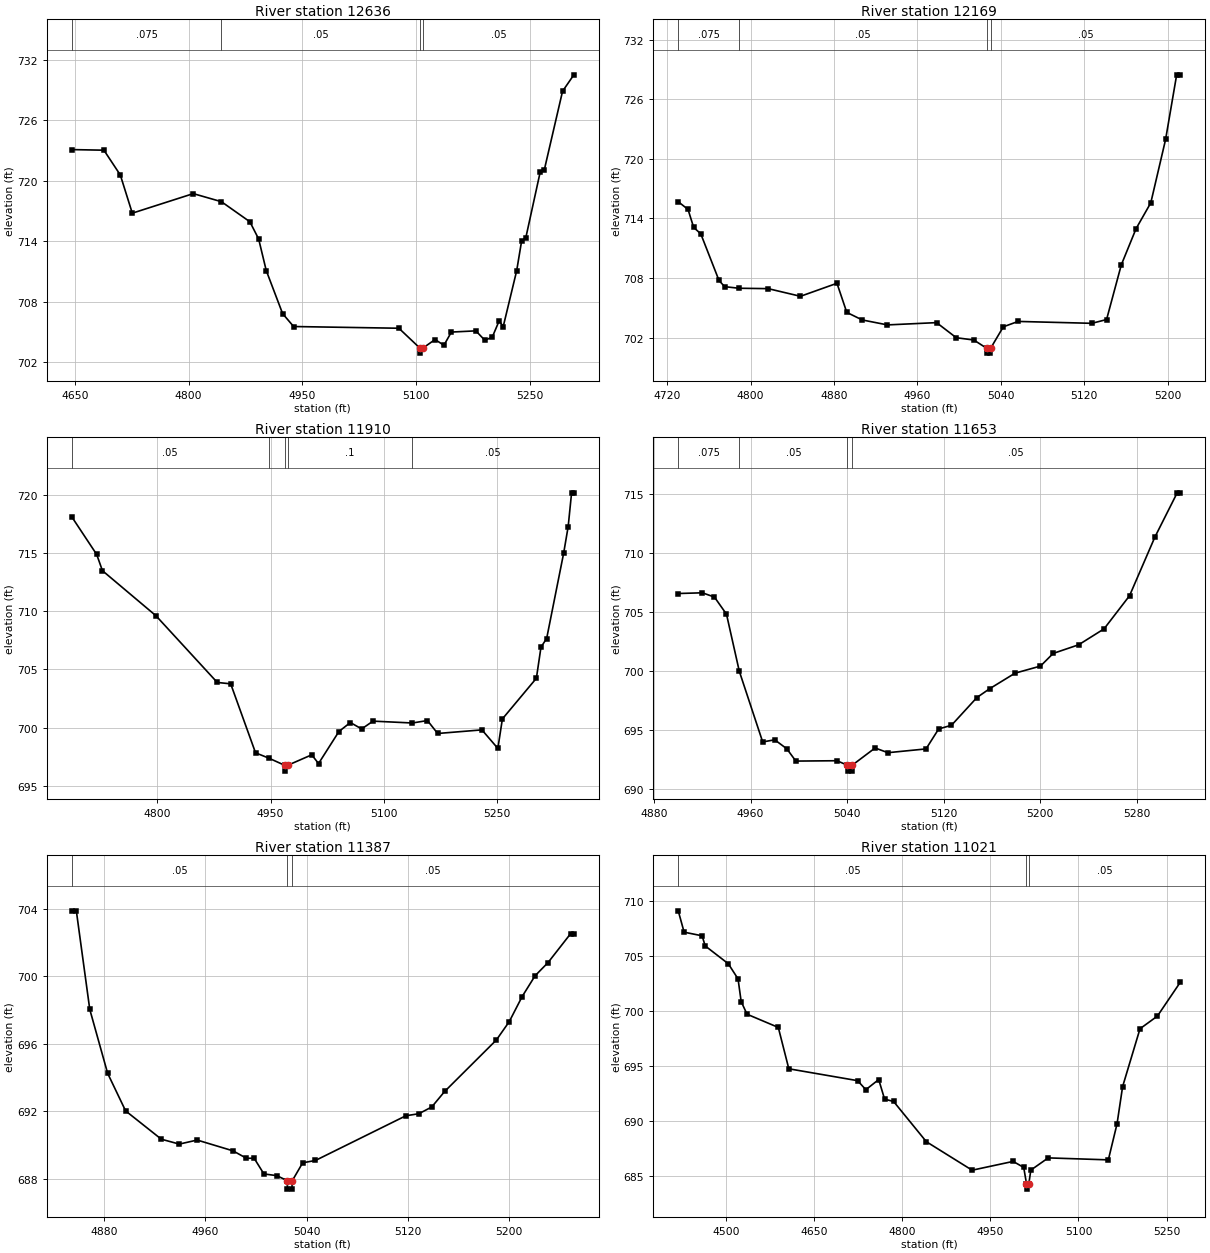
Type RM Length L Ch R = 1,12636,467,467,467
BEGIN DESCRIPTION:
Stream HEN-5 27.0
END DESCRIPTION:
XS GIS Cut Line= 3
      2337885.61      7032165.25      2338184.57      7031992.86
      2338479.02      7032110.01
#Sta/Elev= 30
  4645.9  723.11  4688.3  723.05  4709.9  720.59  4725.7  716.80  4806.1  718.74
  4843.2  717.94  4880.7  715.95  4892.3  714.24  4902.3  711.11  4923.9  706.83
  4938.4  705.55  5077.2  705.38  5104.9  703.41  5105.1  702.91  5108.9  703.41
  5124.9  704.26  5136.6  703.69  5146.4  705.00  5178.7  705.12  5190.5  704.19
  5200.3  704.49  5209.4  706.11  5214.8  705.55  5232.5  711.08  5239.1  714.07
  5244.5  714.34  5263.4  720.84  5268.8  721.05  5293.0  728.90  5307.9  730.53
#Mann=4,-1,0
  4645.9   0.075       0  4843.2    0.05       0  5104.9    0.05       0
  5108.9    0.05       0
Bank Sta=5104.9,5108.9
Exp/Cntr=0.3,0.1

Type RM Length L Ch R = 1,12169,259,259,259
BEGIN DESCRIPTION:
Stream HEN-5 26.0
END DESCRIPTION:
XS GIS Cut Line= 3
      2338078.98      7032309.99      2338329.00      7032410.00
      2338478.99      7032260.01
#Sta/Elev= 30
  4730.7  715.68  4740.1  714.90  4745.5  713.09  4752.3  712.45  4769.8  707.75
  4775.2  707.13  4788.8  706.97  4816.9  706.93  4847.9  706.16  4882.9  707.47
  4892.3  704.54  4907.1  703.78  4931.3  703.28  4978.4  703.51  4997.3  701.99
  5014.1  701.76  5026.3  700.94  5026.5  700.44  5030.0  700.44  5030.3  700.94
  5042.4  703.09  5056.6  703.63  5127.3  703.44  5141.4  703.82  5155.5  709.32
  5169.7  712.97  5183.8  715.57  5198.0  721.95  5208.6  728.45  5212.1  728.45
#Mann=4,-1,0
  4730.7   0.075       0  4788.8    0.05       0  5026.3    0.05       0
  5030.3    0.05       0
Bank Sta=5026.3,5030.3
Exp/Cntr=0.3,0.1

Type RM Length L Ch R = 1,11910,257,257,257
BEGIN DESCRIPTION:
Stream HEN-5 25.0
END DESCRIPTION:
XS GIS Cut Line= 3
      2337978.97      7032610.00      2338279.00      7032660.00
      2338578.98      7032460.01
#Sta/Elev= 30
  4686.9  718.09  4719.9  714.86  4727.5  713.47  4798.4  709.60  4879.5  703.88
  4897.3  703.76  4930.2  697.84  4947.6  697.39  4968.8  696.77  4969.0  696.27
  4972.8  696.77  5004.6  697.67  5013.6  696.92  5040.6  699.67  5055.7  700.44
  5070.7  699.89  5085.7  700.56  5137.8  700.40  5157.8  700.61  5171.3  699.50
  5229.9  699.81  5251.0  698.22  5257.0  700.75  5302.0  704.24  5308.1  706.91
  5315.6  707.65  5338.1  714.97  5344.1  717.26  5348.6  720.15  5351.6  720.15
#Mann=5,-1,0
  4686.9    0.05       0  4947.6     0.1       0  4968.8    0.07       0
  4972.8     0.1       0  5137.8    0.05       0
Bank Sta=4968.8,4972.8
Exp/Cntr=0.3,0.1

Type RM Length L Ch R = 1,11653,266,266,266
BEGIN DESCRIPTION:
Stream HEN-5 24.0
END DESCRIPTION:
XS GIS Cut Line= 3
      2338179.00      7032910.00      2338279.00      7032910.00
      2338578.98      7032810.01
#Sta/Elev= 30
  4900.0  706.56  4920.0  706.62  4930.0  706.26  4940.0  704.81  4950.6  699.99
  4970.0  694.00  4980.0  694.18  4990.0  693.42  4997.5  692.38  5031.6  692.41
  5040.2  692.03  5040.4  691.53  5043.9  691.53  5044.2  692.03  5063.2  693.49
  5073.8  693.09  5105.4  693.41  5115.9  695.10  5126.5  695.41  5147.6  697.76
  5158.1  698.50  5179.2  699.82  5200.3  700.42  5210.8  701.49  5231.9  702.22
  5253.0  703.57  5274.1  706.37  5295.1  711.33  5313.6  715.08  5316.2  715.08
#Mann=4,-1,0
  4900.0   0.075       0  4950.6    0.05       0  5040.2    0.05       0
  5044.2    0.05       0
Bank Sta=5040.2,5044.2
Exp/Cntr=0.3,0.1

Type RM Length L Ch R = 1,11387,366,366,366
BEGIN DESCRIPTION:
Stream HEN-5 23.0
END DESCRIPTION:
XS GIS Cut Line= 3
      2338128.97      7033059.97      2338229.00      7033160.00
      2338478.99      7033210.00
#Sta/Elev= 30
  4854.6  703.89  4858.2  703.89  4868.8  698.05  4882.9  694.26  4897.1  692.03
  4925.3  690.35  4939.5  690.06  4953.6  690.30  4981.9  689.66  4992.5  689.22
  4998.6  689.22  5006.3  688.29  5016.5  688.19  5024.7  687.89  5024.9  687.39
  5028.4  687.39  5028.7  687.89  5036.9  688.95  5047.0  689.09  5118.4  691.74
  5128.6  691.86  5138.8  692.26  5149.0  693.18  5189.8  696.23  5200.0  697.32
  5210.2  698.81  5220.4  700.04  5230.6  700.82  5248.5  702.54  5251.0  702.54
#Mann=3,-1,0
  4854.6    0.05       0  5024.7   0.033       0  5028.7    0.05       0
Bank Sta=5024.7,5028.7
Exp/Cntr=0.3,0.1

Type RM Length L Ch R = 1,11021,365,365,365
BEGIN DESCRIPTION:
Stream HEN-5 22.0
END DESCRIPTION:
XS GIS Cut Line= 3
      2337728.96      7033309.99      2338279.00      7033510.00
      2338528.97      7033410.01
#Sta/Elev= 30
  4418.8  709.11  4428.8  707.17  4459.4  706.84  4464.7  705.92  4504.0  704.30
  4520.6  702.92  4525.9  700.86  4535.9  699.71  4589.1  698.51  4607.0  694.75
  4724.1  693.67  4738.1  692.85  4760.0  693.77  4770.0  691.99  4785.3  691.78
  4841.1  688.12  4919.0  685.53  4988.8  686.33  5006.8  685.78  5011.5  684.31
  5011.8  683.81  5015.5  684.31  5018.9  685.54  5048.5  686.65  5150.8  686.47
  5165.6  689.74  5175.1  693.13  5204.7  698.39  5234.3  699.54  5273.3  702.62
#Mann=3,-1,0
  4418.8    0.05       0  5011.5   0.033       0  5015.5    0.05       0
Bank Sta=5011.5,5015.5
Exp/Cntr=0.3,0.1

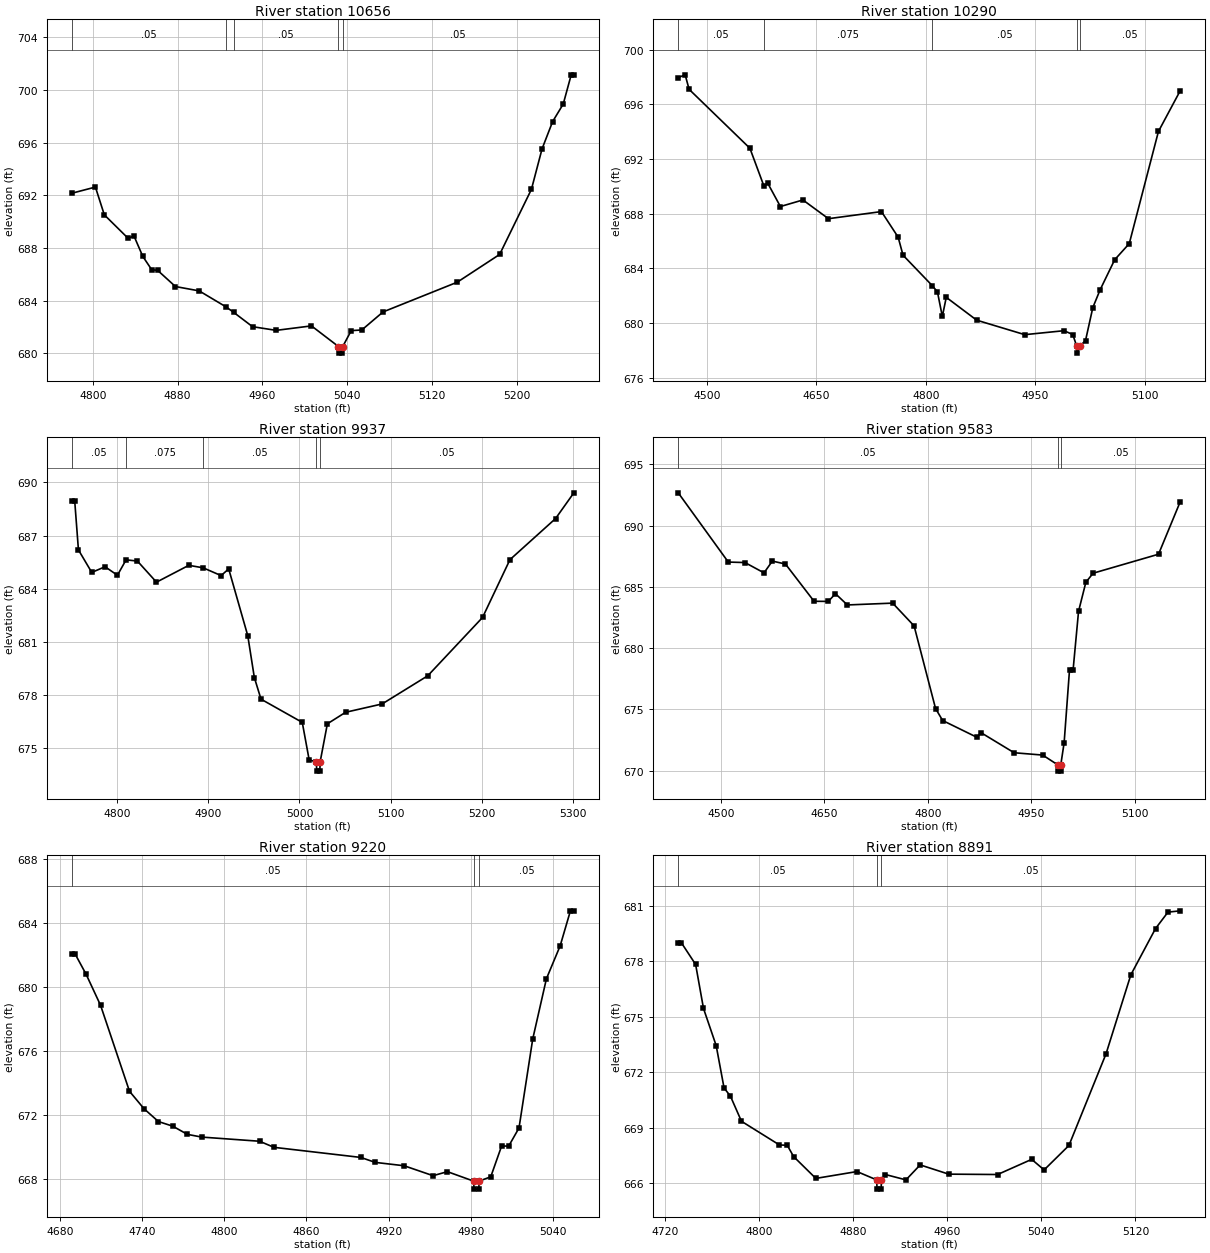
Type RM Length L Ch R = 1,10656,366,366,366
BEGIN DESCRIPTION:
Stream HEN-5 21.0
END DESCRIPTION:
XS GIS Cut Line= 3
      2338079.03      7033710.01      2338279.00      7033810.00
      2338529.03      7033810.00
#Sta/Elev= 30
  4780.2  692.16  4802.5  692.63  4810.9  690.52  4833.3  688.74  4838.9  688.91
  4847.2  687.36  4855.6  686.35  4861.2  686.30  4878.0  685.07  4900.4  684.74
  4925.8  683.52  4932.9  683.11  4950.7  682.02  4973.0  681.74  5006.3  682.08
  5031.8  680.51  5032.0  680.01  5035.5  680.01  5035.8  680.51  5043.8  681.72
  5053.8  681.77  5073.8  683.14  5143.8  685.40  5183.8  687.51  5213.8  692.46
  5223.8  695.53  5233.8  697.61  5243.8  698.94  5251.3  701.16  5253.8  701.16
#Mann=5,-1,0
  4780.2    0.05       0  4925.8   0.075       0  4932.9    0.05       0
  5031.8   0.033       0  5035.8    0.05       0
Bank Sta=5031.8,5035.8
Exp/Cntr=0.3,0.1

Type RM Length L Ch R = 1,10290,353,353,353
BEGIN DESCRIPTION:
Stream HEN-5 20.0
END DESCRIPTION:
XS GIS Cut Line= 3
      2337878.96      7033859.98      2338379.00      7034060.00
      2338529.04      7034060.00
#Sta/Elev= 30
  4460.4  697.95  4469.9  698.15  4475.3  697.09  4558.7  692.78  4578.1  689.99
  4583.0  690.24  4600.5  688.52  4631.4  689.00  4666.4  687.63  4739.1  688.15
  4762.0  686.28  4768.7  684.96  4808.7  682.74  4815.9  682.28  4822.6  680.48
  4828.0  681.88  4869.7  680.21  4935.7  679.15  4989.5  679.44  5001.5  679.16
  5007.0  678.30  5007.2  677.80  5011.0  678.30  5019.0  678.72  5029.0  681.13
  5039.0  682.43  5059.0  684.63  5079.0  685.81  5119.0  694.01  5149.0  697.00
#Mann=5,-1,0
  4460.4    0.05       0  4578.1   0.075       0  4808.7    0.05       0
  5007.0   0.033       0  5011.0    0.05       0
Bank Sta=5007,5011
Exp/Cntr=0.3,0.1

Type RM Length L Ch R = 1,9937,354,354,354
BEGIN DESCRIPTION:
Stream HEN-5 19.0
END DESCRIPTION:
XS GIS Cut Line= 3
      2337978.96      7034159.97      2338179.00      7034310.00
      2338478.95      7034310.00
#Sta/Elev= 30
  4750.6  688.97  4753.8  688.97  4757.9  686.19  4772.5  684.92  4787.1  685.24
  4800.6  684.76  4810.1  685.63  4822.5  685.56  4843.4  684.37  4878.8  685.32
  4894.5  685.18  4914.2  684.74  4922.5  685.12  4943.4  681.35  4950.6  678.99
  4957.9  677.77  5003.1  676.46  5010.6  674.36  5018.6  674.21  5018.9  673.71
  5022.4  673.71  5022.6  674.21  5030.6  676.38  5050.6  677.03  5090.6  677.50
  5140.6  679.09  5200.6  682.38  5230.6  685.64  5280.6  687.96  5300.6  689.41
#Mann=5,-1,0
  4750.6    0.05       0  4810.1   0.075       0  4894.5    0.05       0
  5018.6    0.05       0  5022.6    0.05       0
Bank Sta=5018.6,5022.6
Exp/Cntr=0.3,0.1

Type RM Length L Ch R = 1,9583,363,363,363
BEGIN DESCRIPTION:
Stream HEN-5 18.0
END DESCRIPTION:
XS GIS Cut Line= 3
      2337828.99      7034710.00      2338379.00      7034560.00
      2338528.99      7034510.00
#Sta/Elev= 30
  4437.9  692.67  4510.5  687.02  4534.7  686.98  4562.3  686.14  4574.4  687.10
  4593.4  686.86  4634.9  683.82  4655.6  683.81  4665.9  684.44  4683.2  683.52
  4748.9  683.67  4780.0  681.81  4811.1  675.07  4821.4  674.09  4871.5  672.71
  4876.7  673.11  4925.1  671.46  4966.5  671.27  4988.7  670.46  4989.0  669.96
  4992.5  669.96  4992.7  670.46  4997.6  672.28  5005.4  678.22  5010.6  678.22
  5018.5  683.00  5029.1  685.37  5039.6  686.11  5134.5  687.66  5166.1  691.96
#Mann=3,-1,0
  4437.9    0.05       0  4988.7   0.033       0  4992.7    0.05       0
Bank Sta=4988.7,4992.7
Exp/Cntr=0.3,0.1

Type RM Length L Ch R = 1,9220,329,329,329
BEGIN DESCRIPTION:
Stream HEN-5 17.0
END DESCRIPTION:
XS GIS Cut Line= 3
      2338179.04      7034760.01      2338479.00      7034860.00
      2338529.02      7034860.00
#Sta/Elev= 30
  4688.8  682.03  4691.4  682.03  4699.3  680.78  4709.8  678.85  4730.9  673.48
  4741.5  672.39  4752.0  671.59  4762.5  671.30  4773.1  670.79  4783.6  670.62
  4825.8  670.36  4836.3  669.98  4899.6  669.35  4910.1  669.04  4931.2  668.83
  4952.3  668.21  4962.8  668.46  4981.9  667.87  4982.2  667.37  4985.7  667.37
  4985.9  667.87  4994.4  668.14  5002.3  670.06  5007.5  670.06  5015.0  671.19
  5025.0  676.74  5035.0  680.51  5045.0  682.56  5052.5  684.75  5055.0  684.75
#Mann=3,-1,0
  4688.8    0.05       0  4981.9   0.033       0  4985.9    0.05       0
Bank Sta=4981.9,4985.9
Exp/Cntr=0.3,0.1

Type RM Length L Ch R = 1,8891,380,380,380
BEGIN DESCRIPTION:
Stream HEN-5 16.0
END DESCRIPTION:
XS GIS Cut Line= 3
      2338179.05      7035010.02      2338429.00      7035110.00
      2338578.98      7035060.01
#Sta/Elev= 30
  4730.9  679.02  4733.5  679.02  4745.7  677.84  4752.4  675.46  4763.2  673.45
  4769.9  671.16  4775.3  670.72  4784.7  669.36  4817.0  668.08  4823.7  668.06
  4829.1  667.45  4848.0  666.27  4883.0  666.64  4899.8  666.19  4900.1  665.69
  4903.6  665.69  4903.8  666.19  4907.2  666.48  4924.7  666.19  4936.8  667.00
  4961.1  666.50  5002.7  666.48  5031.7  667.30  5042.3  666.73  5063.4  668.05
  5095.0  673.01  5116.1  677.28  5137.1  679.78  5147.7  680.67  5158.2  680.74
#Mann=3,-1,0
  4730.9    0.05       0  4899.8   0.033       0  4903.8    0.05       0
Bank Sta=4899.8,4903.8
Exp/Cntr=0.3,0.1

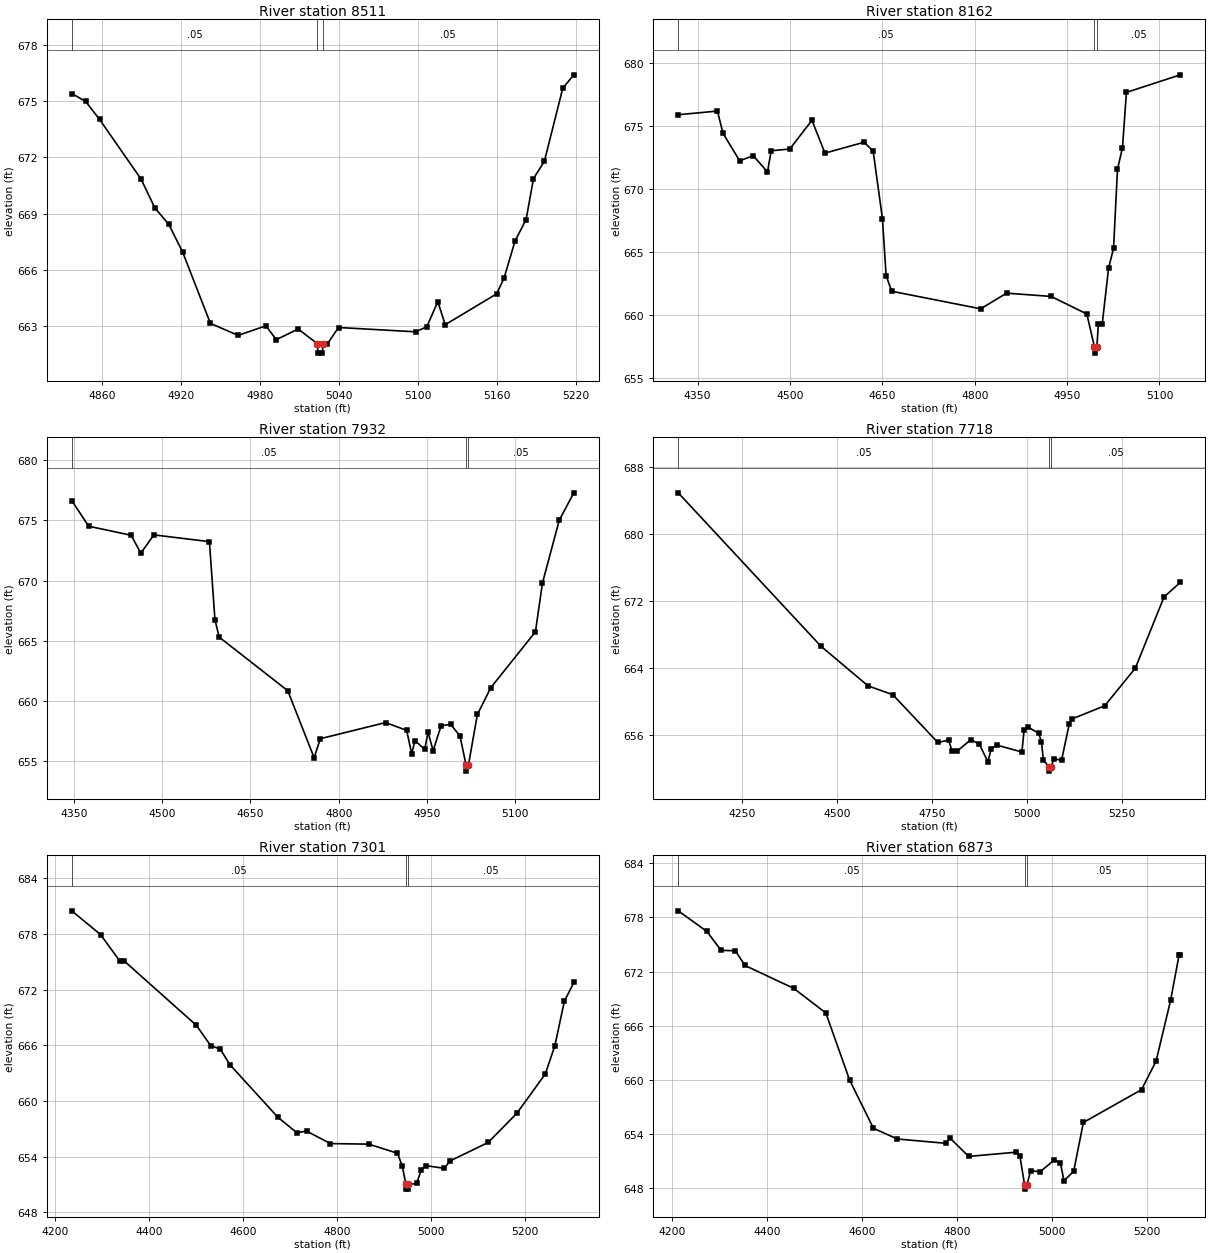
Type RM Length L Ch R = 1,8511,349,349,349
BEGIN DESCRIPTION:
Stream HEN-5 15.0
END DESCRIPTION:
XS GIS Cut Line= 3
      2338379.01      7035510.00      2338529.00      7035460.00
      2338629.00      7035260.01
#Sta/Elev= 30
  4836.7  675.42  4847.2  675.00  4857.8  674.04  4889.4  670.84  4899.9  669.30
  4910.5  668.42  4921.0  666.94  4942.1  663.13  4963.2  662.49  4984.3  663.00
  4992.2  662.26  5008.8  662.83  5023.5  662.04  5023.8  661.54  5027.3  661.54
  5027.5  662.04  5031.1  662.04  5039.5  662.91  5098.2  662.68  5106.6  662.95
  5115.0  664.29  5120.6  663.06  5159.7  664.71  5165.3  665.54  5173.7  667.54
  5182.1  668.68  5187.7  670.87  5196.0  671.80  5210.0  675.71  5218.4  676.42
#Mann=3,-1,0
  4836.7    0.05       0  5023.5   0.033       0  5027.5    0.05       0
Bank Sta=5023.5,5027.5
Exp/Cntr=0.3,0.1

Type RM Length L Ch R = 1,8162,230,230,230
BEGIN DESCRIPTION:
Stream HEN-5 14.0
END DESCRIPTION:
XS GIS Cut Line= 4
      2338207.47      7035837.76      2338760.88      7035471.97
      2338779.00      7035460.00      2338859.53      7035357.93
#Sta/Elev= 30
  4318.7  675.88  4382.3  676.17  4391.4  674.41  4418.4  672.23  4440.4  672.64
  4463.6  671.35  4469.6  673.03  4499.7  673.16  4535.8  675.44  4556.9  672.84
  4620.2  673.70  4635.1  673.01  4650.2  667.66  4656.2  663.14  4665.2  661.90
  4809.7  660.51  4851.8  661.75  4924.0  661.49  4982.1  660.10  4994.3  657.50
  4994.5  657.00  4998.3  657.50  5000.8  659.29  5007.0  659.29  5017.4  663.75
  5025.4  665.29  5031.8  671.56  5039.9  673.27  5046.3  677.65  5133.8  679.04
#Mann=3,-1,0
  4318.7    0.05       0  4994.3   0.033       0  4998.3    0.05       0
Bank Sta=4994.3,4998.3
Exp/Cntr=0.3,0.1

Type RM Length L Ch R = 1,7932,214,214,214
BEGIN DESCRIPTION:
Stream HEN-5 13.5
END DESCRIPTION:
XS GIS Cut Line= 4
      2338252.46      7035980.13      2338821.96      7035687.88
      2338863.93      7035599.46      2338844.45      7035485.60
#Sta/Elev= 30
  4346.2  676.65  4374.9  674.52  4447.1  673.77  4463.6  672.29  4485.8  673.80
  4580.2  673.24  4589.6  666.76  4596.8  665.32  4713.4  660.87  4758.2  655.31
  4768.7  656.89  4879.7  658.23  4915.5  657.58  4924.0  655.65  4929.7  656.73
  4946.2  656.00  4951.8  657.42  4960.5  655.90  4974.0  657.96  4990.3  658.08
  5006.1  657.12  5016.5  654.70  5016.8  654.20  5020.5  654.70  5035.7  658.90
  5058.5  661.12  5134.4  665.76  5146.3  669.80  5174.9  675.02  5199.7  677.29
#Mann=3,-1,0
  4346.2    0.05       0  5016.5   0.033       0  5020.5    0.05       0
Bank Sta=5016.5,5020.5
Exp/Cntr=0.3,0.1

Type RM Length L Ch R = 1,7718,417,417,417
BEGIN DESCRIPTION:
Stream HEN-5 13.0
END DESCRIPTION:
XS GIS Cut Line= 3
      2338178.96      7036260.02      2338979.00      7035810.00
      2339378.97      7035860.00
#Sta/Elev= 30
  4082.0  684.94  4457.2  666.59  4581.5  661.83  4646.5  660.78  4765.0  655.06
  4793.4  655.34  4802.6  654.01  4816.3  654.04  4851.7  655.39  4873.7  654.90
  4896.7  652.75  4905.3  654.25  4919.6  654.75  4986.2  653.92  4992.0  656.57
  5002.4  656.90  5030.2  656.16  5037.7  655.14  5042.8  652.94  5057.9  652.13
  5058.5  651.63  5062.9  652.13  5070.5  653.11  5090.6  652.93  5110.8  657.27
  5118.3  657.88  5204.0  659.45  5284.6  663.95  5360.2  672.48  5403.0  674.22
#Mann=3,-1,0
  4082.0    0.05       0  5057.9   0.033       0  5062.9    0.05       0
Bank Sta=5057.9,5062.9
Exp/Cntr=0.3,0.1

Type RM Length L Ch R = 1,7301,428,428,428
BEGIN DESCRIPTION:
Stream HEN-5 12.0
END DESCRIPTION:
XS GIS Cut Line= 3
      2338278.95      7036260.01      2339029.00      7036110.00
      2339328.96      7036060.01
#Sta/Elev= 30
  4235.7  680.51  4296.9  677.95  4337.7  675.12  4347.9  675.08  4500.9  668.17
  4531.5  665.98  4551.9  665.60  4572.3  663.93  4674.3  658.27  4715.1  656.58
  4735.5  656.77  4786.4  655.42  4868.0  655.36  4929.2  654.38  4939.4  652.99
  4947.1  651.01  4947.7  650.51  4951.5  650.51  4952.2  651.01  4970.0  651.12
  4980.2  652.62  4990.4  653.04  5028.5  652.75  5041.2  653.55  5122.3  655.54
  5183.1  658.67  5243.9  662.92  5264.2  665.95  5284.5  670.76  5304.7  672.79
#Mann=3,-1,0
  4235.7    0.05       0  4947.1   0.033       0  4952.2    0.05       0
Bank Sta=4947.1,4952.2
Exp/Cntr=0.3,0.1

Type RM Length L Ch R = 1,6873,464,464,464
BEGIN DESCRIPTION:
Stream HEN-5 11.0
END DESCRIPTION:
XS GIS Cut Line= 3
      2338328.96      7036310.00      2339129.00      7036360.00
      2339379.05      7036309.99
#Sta/Elev= 30
  4213.0  678.73  4273.2  676.45  4303.2  674.35  4333.3  674.31  4353.3  672.68
  4456.0  670.15  4523.6  667.42  4573.7  659.99  4623.8  654.66  4673.9  653.47
  4776.6  652.99  4784.2  653.61  4824.2  651.54  4924.4  652.01  4931.9  651.62
  4941.8  648.42  4942.6  647.92  4947.1  648.42  4954.5  649.97  4974.5  649.84
  5004.6  651.15  5017.2  650.85  5024.8  648.84  5045.2  649.90  5065.6  655.30
  5188.0  658.93  5218.6  662.09  5249.2  668.83  5267.0  673.84  5269.6  673.84
#Mann=3,-1,0
  4213.0    0.05       0  4941.8   0.033       0  4947.1    0.05       0
Bank Sta=4941.8,4947.1
Exp/Cntr=0.3,0.1

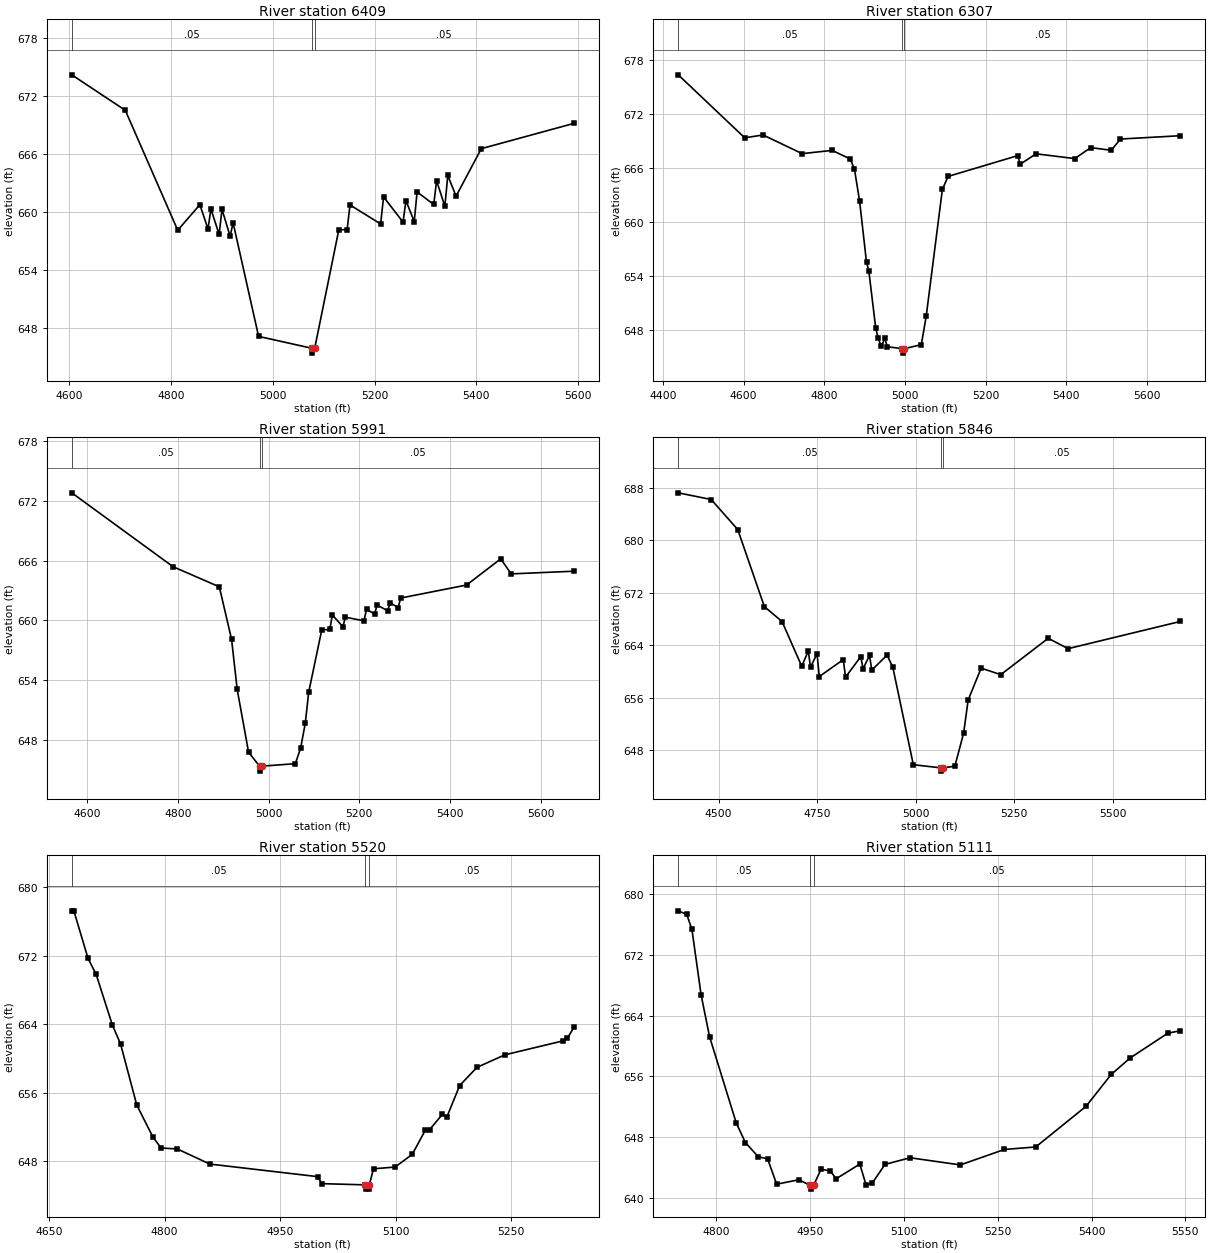
Type RM Length L Ch R = 1,6409,102,102,102
BEGIN DESCRIPTION:
Stream HEN-5 10.0
END DESCRIPTION:
XS GIS Cut Line= 3
      2338433.01      7036423.49      2338754.17      7036601.43
      2339301.00      7036892.21
#Sta/Elev= 30
  4605.0  674.18  4710.2  670.51  4813.2  658.12  4856.7  660.76  4872.7  658.25
  4878.4  660.32  4894.5  657.69  4900.2  660.27  4916.2  657.49  4921.9  658.91
  4972.1  647.15  5076.9  645.92  5077.7  645.42  5082.3  645.92  5129.7  658.16
  5146.0  658.19  5151.7  660.73  5211.9  658.77  5217.6  661.56  5255.9  658.96
  5261.6  661.18  5277.9  659.01  5283.5  662.08  5316.2  660.78  5321.8  663.23
  5338.1  660.59  5343.8  663.78  5360.1  661.64  5409.7  666.55  5591.5  669.16
#Mann=3,-1,0
  4605.0    0.05       0  5076.9    0.05       0  5082.3    0.05       0
Bank Sta=5076.9,5082.3
Exp/Cntr=0.3,0.1

Type RM Length L Ch R = 1,6307,316,316,316
BEGIN DESCRIPTION:
Stream HEN-5 9.5
END DESCRIPTION:
XS GIS Cut Line= 3
      2338263.68      7036475.54      2338910.42      7036779.38
      2339387.84      7037009.41
#Sta/Elev= 30
  4437.9  676.30  4602.6  669.31  4648.2  669.62  4745.0  667.55  4819.4  667.91
  4864.5  666.95  4874.7  665.82  4887.4  662.30  4904.6  655.47  4910.2  654.57
  4927.4  648.18  4933.0  647.13  4941.0  646.14  4950.2  647.05  4955.8  646.11
  4993.1  645.90  4993.9  645.40  4998.7  645.90  5040.4  646.34  5052.5  649.48
  5092.6  663.57  5106.7  665.02  5279.6  667.33  5285.1  666.36  5324.8  667.53
  5420.8  667.00  5460.5  668.22  5511.3  667.92  5533.9  669.17  5682.4  669.54
#Mann=3,-1,0
  4437.9    0.05       0  4993.1    0.05       0  4998.7    0.05       0
Bank Sta=4993.1,4998.7
Exp/Cntr=0.3,0.1

Type RM Length L Ch R = 1,5991,145,145,145
BEGIN DESCRIPTION:
Stream HEN-5 9.0
END DESCRIPTION:
XS GIS Cut Line= 3
      2338211.62      7036827.12      2338629.00      7036960.00
      2339240.29      7037230.78
#Sta/Elev= 30
  4566.3  672.82  4789.6  665.39  4891.5  663.37  4918.5  658.09  4930.9  653.05
  4956.0  646.74  4980.2  645.34  4981.0  644.84  4985.8  645.34  5059.0  645.59
  5070.7  647.14  5080.9  649.64  5088.5  652.78  5117.3  659.04  5135.1  659.08
  5140.6  660.54  5163.9  659.35  5169.3  660.32  5210.4  659.95  5215.9  661.12
  5233.7  660.62  5239.2  661.54  5262.5  660.96  5267.9  661.76  5285.7  661.29
  5291.2  662.24  5436.4  663.55  5511.7  666.18  5535.0  664.67  5672.9  664.94
#Mann=3,-1,0
  4566.3    0.05       0  4980.2    0.05       0  4985.8    0.05       0
Bank Sta=4980.2,4985.8
Exp/Cntr=0.3,0.1

Type RM Length L Ch R = 1,5846,326,326,326
BEGIN DESCRIPTION:
Stream HEN-5 8.5
END DESCRIPTION:
XS GIS Cut Line= 3
      2337994.60      7036792.39      2338689.06      7037148.31
      2339125.74      7037377.45
#Sta/Elev= 30
  4397.5  687.27  4481.1  686.25  4548.5  681.66  4615.9  669.91  4660.8  667.63
  4710.8  660.79  4727.4  663.14  4733.0  660.66  4749.6  662.72  4755.2  659.23
  4816.2  661.82  4821.8  659.14  4860.6  662.28  4866.2  660.42  4882.8  662.45
  4888.4  660.22  4927.2  662.50  4941.8  660.65  4993.8  645.78  5063.2  645.30
  5064.1  644.80  5068.8  645.30  5099.1  645.55  5121.4  650.60  5132.8  655.64
  5165.8  660.52  5215.5  659.52  5335.9  665.07  5386.3  663.49  5671.0  667.64
#Mann=3,-1,0
  4397.5    0.05       0  5063.2    0.05       0  5068.8    0.05       0
Bank Sta=5063.2,5068.8
Exp/Cntr=0.3,0.1

Type RM Length L Ch R = 1,5520,409,409,409
BEGIN DESCRIPTION:
Stream HEN-5 8.0
END DESCRIPTION:
XS GIS Cut Line= 3
      2338128.96      7037259.99      2338429.00      7037360.00
      2338729.02      7037510.01
#Sta/Elev= 30
  4679.5  677.27  4682.2  677.27  4700.6  671.71  4711.2  669.83  4732.2  663.92
  4742.8  661.72  4763.9  654.56  4785.0  650.80  4795.5  649.55  4816.6  649.43
  4858.7  647.67  4998.6  646.20  5004.2  645.38  5060.0  645.24  5060.9  644.74
  5064.8  644.74  5065.7  645.24  5071.2  647.12  5099.2  647.32  5121.5  648.81
  5138.3  651.61  5143.9  651.68  5160.7  653.50  5166.3  653.15  5183.0  656.85
  5205.4  658.97  5241.7  660.44  5317.2  662.07  5322.8  662.36  5331.2  663.64
#Mann=3,-1,0
  4679.5    0.05       0  5060.0   0.033       0  5065.7    0.05       0
Bank Sta=5060,5065.7
Exp/Cntr=0.3,0.1

Type RM Length L Ch R = 1,5111,465,465,465
BEGIN DESCRIPTION:
Stream HEN-5 7.0
END DESCRIPTION:
XS GIS Cut Line= 3
      2338028.99      7037409.98      2338179.00      7037610.00
      2338729.01      7037660.00
#Sta/Elev= 30
  4739.6  677.76  4753.2  677.29  4761.5  675.31  4776.1  666.74  4789.6  661.24
  4832.3  649.89  4846.9  647.32  4867.7  645.43  4882.3  645.20  4896.9  641.85
  4932.3  642.43  4950.3  641.70  4951.2  641.20  4956.0  641.70  4967.7  643.80
  4982.3  643.60  4992.1  642.57  5029.8  644.49  5039.8  641.73  5049.9  642.02
  5070.0  644.45  5110.1  645.32  5190.4  644.38  5260.7  646.41  5310.9  646.74
  5391.3  652.08  5431.4  656.26  5461.6  658.42  5521.8  661.68  5541.9  662.01
#Mann=3,-1,0
  4739.6    0.05       0  4950.3   0.033       0  4956.0    0.05       0
Bank Sta=4950.3,4956
Exp/Cntr=0.3,0.1

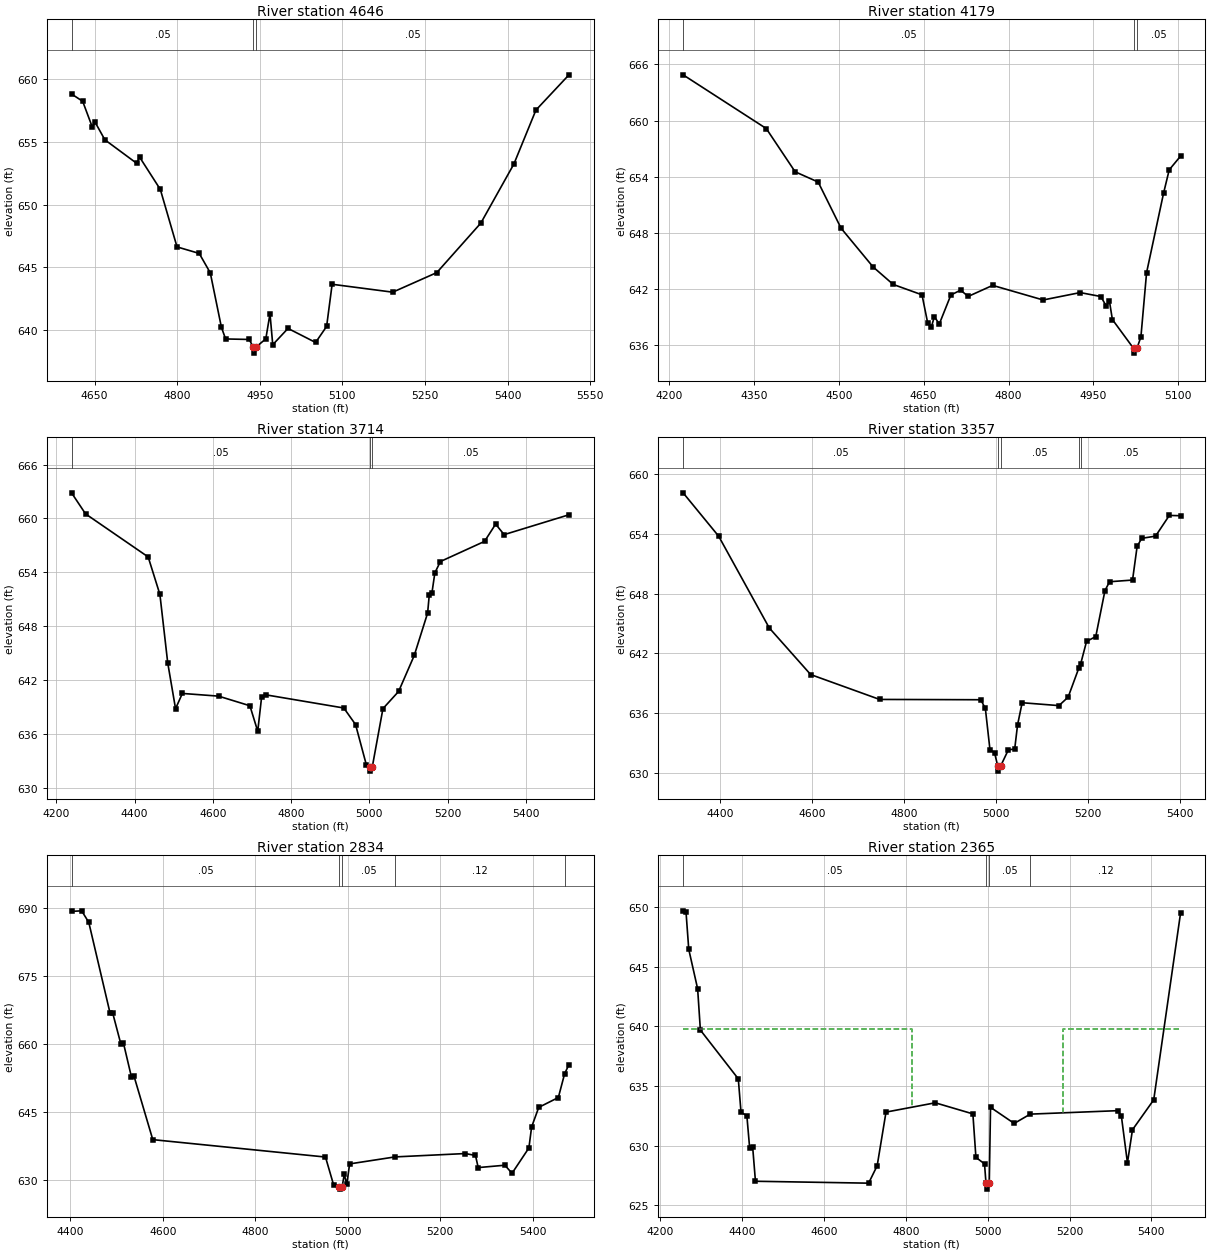
Type RM Length L Ch R = 1,4646,467,467,467
BEGIN DESCRIPTION:
Stream HEN-5 6.0
END DESCRIPTION:
XS GIS Cut Line= 3
      2337779.00      7037860.00      2338179.00      7037810.00
      2338678.99      7037810.00
#Sta/Elev= 30
  4608.2  658.81  4628.4  658.23  4646.0  656.16  4651.0  656.56  4668.7  655.16
  4726.6  653.28  4731.6  653.79  4769.4  651.20  4799.7  646.62  4840.0  646.10
  4860.1  644.55  4880.3  640.21  4887.9  639.28  4930.7  639.24  4937.9  638.65
  4938.8  638.15  4943.6  638.65  4960.9  639.29  4968.5  641.29  4973.5  638.82
  5001.2  640.12  5051.3  639.00  5071.3  640.28  5081.3  643.64  5191.3  643.01
  5271.3  644.57  5351.3  648.52  5411.3  653.23  5451.3  657.53  5511.3  660.34
#Mann=3,-1,0
  4608.2    0.05       0  4937.9   0.033       0  4943.6    0.05       0
Bank Sta=4937.9,4943.6
Exp/Cntr=0.3,0.1

Type RM Length L Ch R = 1,4179,465,465,465
BEGIN DESCRIPTION:
Stream HEN-5 5.0
END DESCRIPTION:
XS GIS Cut Line= 3
      2337714.81      7038259.47      2338479.00      7038110.00
      2338579.03      7038110.00
#Sta/Elev= 30
  4225.1  664.89  4372.0  659.15  4423.0  654.53  4463.7  653.43  4504.1  648.50
  4560.7  644.36  4596.2  642.49  4647.1  641.38  4657.3  638.33  4663.8  637.98
  4668.9  639.04  4677.7  638.27  4698.1  641.36  4715.3  641.88  4728.7  641.21
  4771.9  642.39  4861.1  640.83  4926.5  641.62  4963.0  641.20  4972.9  640.14
  4978.0  640.77  4983.4  638.74  5020.9  635.65  5021.8  635.15  5026.7  635.65
  5033.8  636.89  5043.8  643.75  5073.8  652.24  5083.8  654.74  5103.8  656.20
#Mann=3,-1,0
  4225.1    0.05       0  5020.9   0.033       0  5026.7    0.05       0
Bank Sta=5020.9,5026.7
Exp/Cntr=0.3,0.1

Type RM Length L Ch R = 1,3714,357,357,357
BEGIN DESCRIPTION:
Stream HEN-5 4.0
END DESCRIPTION:
XS GIS Cut Line= 4
      2337723.25      7038485.89      2338479.00      7038510.00
      2338633.12      7038510.00      2338901.46      7038267.85
#Sta/Elev= 30
  4238.6  662.85  4274.4  660.51  4434.5  655.72  4464.5  651.55  4484.5  643.94
  4504.5  638.84  4521.9  640.54  4614.5  640.24  4694.6  639.17  4714.6  636.33
  4724.6  640.17  4734.6  640.39  4934.7  638.92  4964.7  637.08  4992.2  632.61
  5001.8  632.40  5002.7  631.90  5007.6  632.40  5034.7  638.85  5074.7  640.76
  5114.7  644.76  5148.9  649.48  5153.2  651.53  5159.9  651.70  5167.4  653.95
  5181.6  655.21  5294.4  657.45  5322.8  659.37  5344.5  658.20  5510.3  660.41
#Mann=3,-1,0
  4238.6    0.05       0  5001.8   0.033       0  5007.6    0.05       0
Bank Sta=5001.8,5007.6
Exp/Cntr=0.3,0.1

Type RM Length L Ch R = 1,3357,523,523,523
BEGIN DESCRIPTION:
Stream HEN-5 3.0
END DESCRIPTION:
XS GIS Cut Line= 3
      2337861.57      7038817.13      2338582.80      7038821.32
      2338943.44      7038817.13
#Sta/Elev= 30
  4320.2  658.12  4397.6  653.76  4507.6  644.55  4597.6  639.87  4747.6  637.37
  4967.6  637.34  4977.6  636.46  4987.6  632.32  4997.6  632.01  5004.6  630.67
  5005.6  630.17  5010.7  630.67  5027.6  632.31  5041.4  632.39  5047.6  634.81
  5057.6  637.04  5137.6  636.75  5157.6  637.60  5180.7  640.50  5184.8  640.93
  5197.7  643.20  5217.7  643.68  5237.7  648.30  5247.7  649.19  5297.7  649.36
  5307.7  652.75  5317.7  653.55  5347.7  653.77  5377.7  655.85  5402.1  655.82
#Mann=5,-1,0
  4320.2    0.05       0  5004.6   0.033       0  5010.7    0.05       0
  5180.7    0.12       0  5184.8    0.05       0
Bank Sta=5004.6,5010.7
Exp/Cntr=0.3,0.1

Type RM Length L Ch R = 1,2834,469,469,469
BEGIN DESCRIPTION:
Stream HEN-5 2.0
END DESCRIPTION:
XS GIS Cut Line= 3
      2337929.04      7039010.02      2338479.00      7039260.00
      2338879.00      7039010.00
#Sta/Elev= 30
  4402.8  689.22  4424.7  689.34  4440.1  686.80  4486.2  666.79  4491.7  666.89
  4509.3  660.09  4514.8  660.36  4532.4  652.75  4537.9  652.96  4578.5  638.99
  4952.0  635.16  4969.6  629.02  4981.9  628.60  4982.9  628.10  4988.0  628.60
  4992.6  631.34  4998.1  629.17  5004.2  633.65  5102.4  635.19  5254.5  635.93
  5276.4  635.51  5282.3  632.84  5340.0  633.36  5355.4  631.58  5391.9  637.16
  5397.8  641.78  5413.2  646.09  5455.6  648.26  5469.2  653.50  5478.6  655.51
#Mann=5,-1,0
  4402.8    0.05       0  4981.9   0.033       0  4988.0    0.05       0
  5102.4    0.12       0  5469.2    0.05       0
Bank Sta=4981.9,4988
Exp/Cntr=0.3,0.1

Type RM Length L Ch R = 1,2365,604,604,604
BEGIN DESCRIPTION:
Stream HEN-5 1.0
END DESCRIPTION:
XS GIS Cut Line= 3
      2337979.02      7039210.02      2338529.00      7039710.00
      2338929.02      7039459.99
#Sta/Elev= 30
  4256.2  649.69  4263.3  649.60  4270.0  646.46  4291.7  643.15  4298.4  639.69
  4391.0  635.60  4397.7  632.78  4411.9  632.52  4418.7  629.82  4426.1  629.89
  4432.9  627.01  4709.3  626.85  4730.2  628.31  4751.8  632.81  4872.1  633.59
  4964.0  632.66  4971.4  629.01  4992.4  628.47  4996.0  626.85  4998.0  626.35
  5004.0  626.85  5007.1  633.21  5064.9  631.86  5104.1  632.64  5317.9  632.93
  5326.7  632.47  5341.5  628.56  5353.8  631.33  5405.7  633.84  5471.2  649.49
#Mann=4,-1,0
  4256.2    0.05       0  4996.0   0.033       0  5004.0    0.05       0
  5104.1    0.12       0
#XS Ineff=2,0
    0.00 4816.00  639.81 5184.00    0.00  639.81
Permanent Ineff=
       F       F
Bank Sta=4996,5004
Exp/Cntr=0.3,0.1

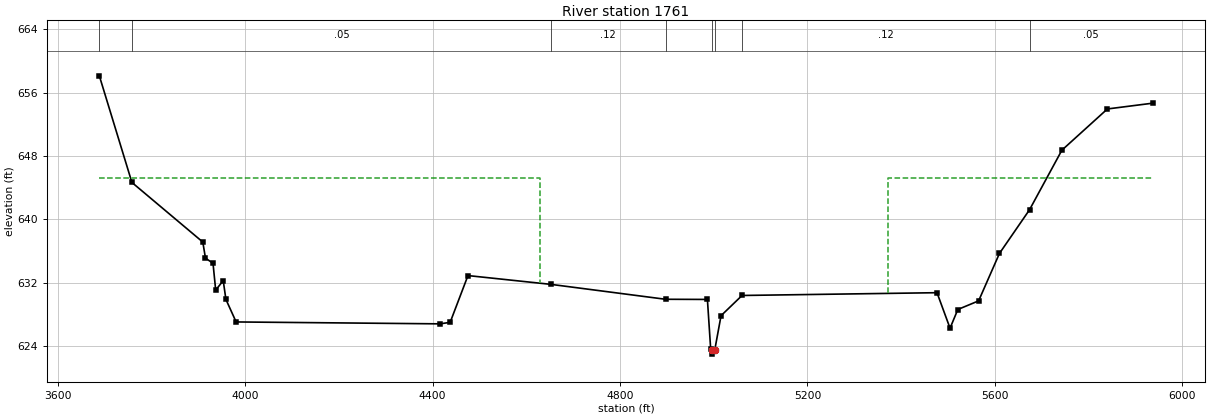
Type RM Length L Ch R = 1,1761,0,0,0
BEGIN DESCRIPTION:
Stream HEN-5 0.5
END DESCRIPTION:
XS GIS Cut Line= 3
      2337786.34      7039194.19      2338376.64      7040270.61
      2339285.15      7039805.95
#Sta/Elev= 30
  3688.8  658.12  3758.3  644.67  3909.6  637.15  3915.3  635.12  3931.4  634.47
  3937.1  631.09  3953.2  632.28  3958.9  629.92  3980.7  627.07  4415.7  626.83
  4437.5  627.02  4475.5  632.92  4652.7  631.81  4897.2  629.93  4986.5  629.91
  4993.4  623.72  4995.9  623.51  4997.0  623.01  5002.1  623.51  5015.6  627.86
  5060.4  630.41  5476.5  630.76  5504.3  626.28  5520.9  628.64  5565.3  629.73
  5609.7  635.71  5673.9  641.22  5743.0  648.74  5840.1  653.94  5936.9  654.67
#Mann=8,-1,0
  3688.8   0.075       0  3758.3    0.05       0  4652.7    0.12       0
  4897.2    0.05       0  4995.9   0.033       0  5002.1    0.05       0
  5060.4    0.12       0  5673.9    0.05       0
#XS Ineff=2,0
    0.00 4628.50  645.17 5371.50    0.00  645.17
Permanent Ineff=
       F       F
Bank Sta=4995.9,5002.1
Exp/Cntr=0.3,0.1

Chan Stop Cuts=-1