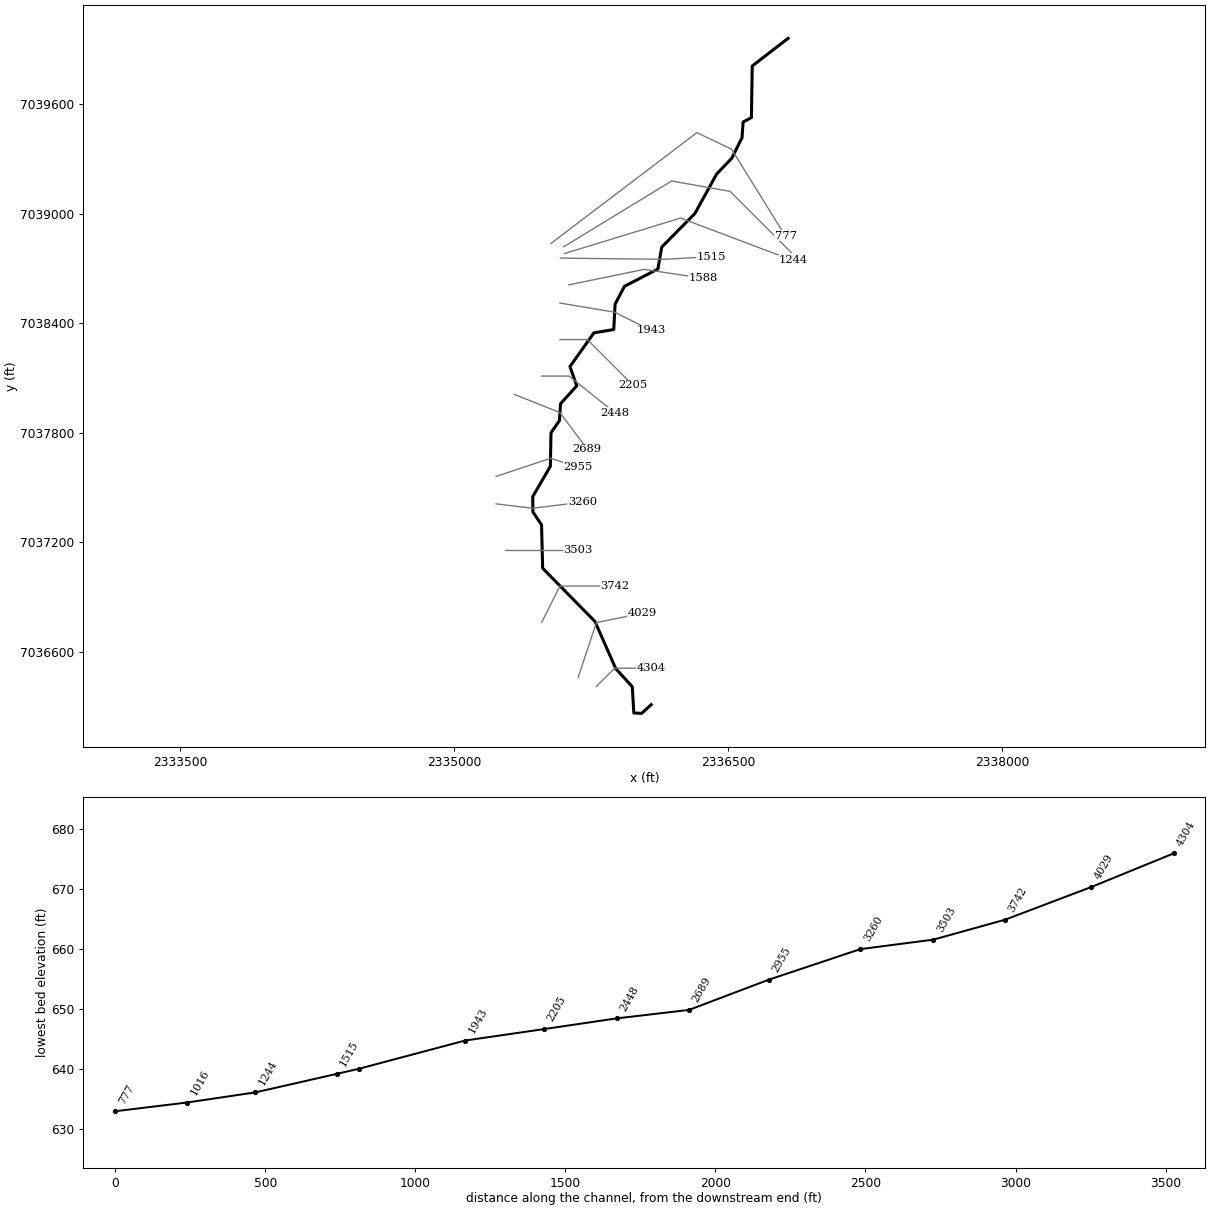
--- Stream HEN-6.prj (project) ---

Proj Title=Stream HEN-6 Base Level Engineering
Current Plan=p01
Default Exp/Contr=0.3,0.1
English Units
Geom File=g01
Flow File=f01
Plan File=p01
Y Axis Title=Elevation
X Axis Title(PF)=Main Channel Distance
X Axis Title(XS)=Station
BEGIN DESCRIPTION:
Stream HEN-6
END DESCRIPTION:
DSS Export Rating Curves= 0
DSS Export Rating Curve Sorted= 0
DSS Export Volume Flow Curves= 0
DXF OffsetX= 0
DXF OffsetY= 0
DXF ScaleX= 1
DXF ScaleY= 10

--- Stream HEN-6.p01 (plan) ---

Plan Title=Multiple Run
Program Version=4.10
Short Identifier=Multiple
Geom File=g01
Flow File=f01
Subcritical Flow
K Sum by GR= 0
Std Step Tol= 0.01
Critical Tol= 0.01
Num of Std Step Trials= 20
Max Error Tol= 0.3
Flow Tol Ratio= 0.001
Split Flow NTrial= 30
Split Flow Tol= 0.02
Split Flow Ratio= 0.02
Log Output Level= 0
Friction Slope Method= 0
Unsteady Friction Slope Method= 2
Unsteady Bridges Friction Slope Method= 1
Parabolic Critical Depth
Global Vel Dist= 1 , 1 , 1
Global Log Level= 0
CheckData=True
Encroach Param=-1 ,0,0, 0
BEGIN DESCRIPTION:
Multiple Run
END DESCRIPTION:
Computation Interval=1HOUR
Output Interval=1HOUR
Run HTab= 0
Run UNet= 0
Run PostProcess= 0
Run WQNet= 0
UNET Theta= 1
UNET Theta Warmup= 1
UNET ZTol= 0.02
UNET ZSATol= 0.05
UNET MxIter= 20
UNET MaxInSteps= 0
UNET DtIC= 0
UNET DtMin= 0
UNET MaxCRTS= 20
UNET WFStab= 2
UNET SFStab= 1
UNET WFX= 1
UNET SFX= 1
UNET DSS MLevel= 4
UNET DZMax Abort= 100
UNET Convert EG Bridges= 0
UNET Use Existing IB Tables=-1
UNET Froude Reduction=False
UNET Froude Limit= 1
UNET Froude Power= 10
UNET Time Slicing=0,0, 5
UNET Junction Losses=0
Instantaneous Interval=1HOUR
Write IC File= 0
Write IC File at Sim End=0
Echo Input=False
Echo Parameters=False
Echo Output=False
Write Detailed= 0
WQ AD Non Conservative
WQ ULTIMATE=-1
WQ Max Comp Step=1HOUR
WQ Output Interval=15MIN
WQ Output Selected Increments= 0
WQ Output face flow=0
WQ Output face velocity=0
WQ Output face area=0
WQ Output face dispersion=0
WQ Output cell volume=0
WQ Output cell surface area=0
WQ Output cell continuity=0
WQ Output cumulative cell continuity=0
WQ Output face conc=0
WQ Output face dconc_dx=0
WQ Output face courant=0
WQ Output face peclet=0
WQ Output face adv mass=0
WQ Output face disp mass=0
WQ Output cell mass=0
WQ Output cell source sink temp=0
WQ Output cell source sink nsm=0
WQ Output MaxMinRange=-1
WQ Daily Max Min Mean=-1
WQ Daily Range=0
WQ Daily Time=0
WQ Create Restart=0
WQ Fixed Restart=0
WQ System Summary=0
WQ Use Fixed Temperature=0
Sorting and Armoring Iterations= 10
XS Update Threshold= 0.02
Hydraulics Update Threshold= 0.02
Energy Slope Method= 1
Volume Change Method= 0
XS Weighting Method= 0
Number of US Weighted Cross Sections= 1
Number of DS Weighted Cross Sections= 1
Upstream XS Weight=0.25
Main XS Weight=0.5
Downstream XS Weight=0.25
Number of DS XS's Weighted with US Boundary= 1
Upstream Boundary Weight= 1
Weight of XSs Associated with US Boundary= 0
Number of US XS's Weighted with DS Boundary= 1
Downstream Boundary Weight= 0.5
Weight of XSs Associated with DS Boundary= 0.5
Sediment Output Level= 4
Mass or Volume Output= 0
Output Increment Type= 1
Profile and TS Output Increment= 10
XS Output Flag= 0
XS Output Increment= 10
Disregard all LS=0
Disregard all Conn=0
Disregard all Breaches=0
Disregard all Pumps=0

--- Stream HEN-6.f01 (steady flow) ---

Flow Title=Multiple
Program Version=4.10
Number of Profiles= 7
Profile Names=10-year,25-year,50-year,1pct_min,100-year,1pct_plu,500-year
River Rch & RM=Stream HEN-6,Reach-1         ,4304
     467     627     756     453     903    1800    1290
Boundary for River Rch & Prof#=Stream HEN-6,Reach-1         , 1
Up Type= 0
Dn Type= 3
Dn Slope=0.001
Boundary for River Rch & Prof#=Stream HEN-6,Reach-1         , 2
Up Type= 0
Dn Type= 3
Dn Slope=0.001
Boundary for River Rch & Prof#=Stream HEN-6,Reach-1         , 3
Up Type= 0
Dn Type= 3
Dn Slope=0.001
Boundary for River Rch & Prof#=Stream HEN-6,Reach-1         , 4
Up Type= 0
Dn Type= 3
Dn Slope=0.001
Boundary for River Rch & Prof#=Stream HEN-6,Reach-1         , 5
Up Type= 0
Dn Type= 3
Dn Slope=0.001
Boundary for River Rch & Prof#=Stream HEN-6,Reach-1         , 6
Up Type= 0
Dn Type= 3
Dn Slope=0.001
Boundary for River Rch & Prof#=Stream HEN-6,Reach-1         , 7
Up Type= 0
Dn Type= 3
Dn Slope=0.001
DSS Import GetInterval= 0
DSS Import GetPeak= 0
DSS Import FillOption= 0

--- Stream HEN-6.g01 (geometry) ---

Geom Title=Existing Conditions
Program Version=4.10

River Reach=Stream HEN-6    ,Reach-1
Reach XY= 30
        2336079.        7036310.      2336026.76      7036262.41
      2335984.03       7036264.5      2335975.44      7036408.52
      2335884.85      7036507.71      2335770.86      7036766.06
      2335484.46      7037057.55      2335478.48      7037294.78
      2335431.17      7037365.98      2335430.09      7037449.46
      2335526.76      7037615.93      2335530.22       7037799.5
      2335576.64      7037865.98      2335582.64       7037958.5
      2335671.16       7038056.6      2335634.13      7038162.28
      2335765.38      7038346.73      2335873.96      7038365.08
      2335881.24      7038504.08       2335932.5      7038601.54
      2336115.74      7038696.34      2336136.86      7038816.17
      2336318.22      7039000.32      2336437.18      7039216.04
      2336520.84      7039303.95      2336576.64      7039416.05
      2336582.56       7039501.5      2336628.05      7039525.96
      2336632.53      7039808.55        2336829.        7039960.

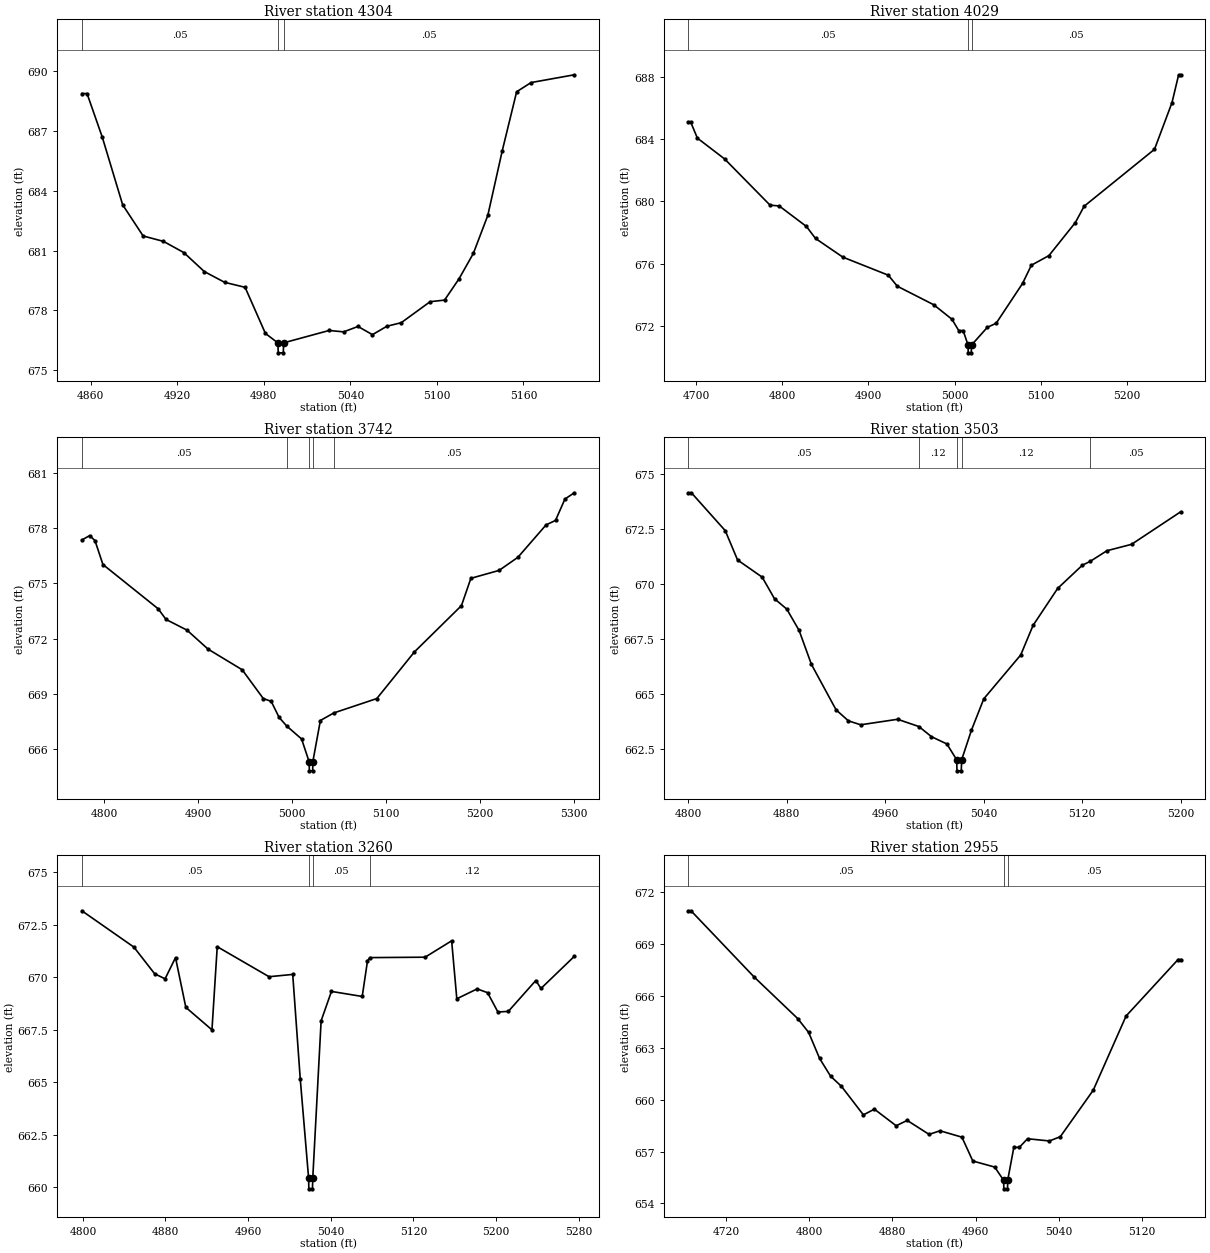
Type RM Length L Ch R = 1 ,4304    ,275,275,275
BEGIN DESCRIPTION:
Stream HEN-6 12.0
END DESCRIPTION:
XS GIS Cut Line= 3
      2335778.98      7036409.98        2335879.        7036510.
      2336079.05        7036510.
#Sta/Elev= 30
  4853.8  688.86  4857.4  688.86    4868  686.67  4882.1  683.29  4896.3  681.73
  4910.4  681.46  4924.5   680.9  4938.7  679.95  4952.8  679.41    4967  679.16
  4981.1  676.85  4989.7  676.38    4990  675.88  4993.5  675.88  4993.7  676.38
  5025.3     677  5035.3  676.93  5045.3   677.2  5055.3  676.79  5065.3  677.21
  5075.3  677.39  5095.3  678.44  5105.3  678.52  5115.3  679.58  5125.3  680.86
  5135.3  682.76  5145.3  685.99  5155.3  688.95  5165.3  689.41  5195.3   689.8
#Mann= 3 ,-1 , 0
  4853.8     .05       0  4989.7    .033       0  4993.7     .05       0
Bank Sta=4989.7,4993.7
XS Rating Curve= 0 ,0
Exp/Cntr=0.3,0.1

Type RM Length L Ch R = 1 ,4029    ,287,287,287
BEGIN DESCRIPTION:
Stream HEN-6 11.0
END DESCRIPTION:
XS GIS Cut Line= 3
      2335679.01      7036460.03        2335779.        7036760.
      2336028.96      7036809.99
#Sta/Elev= 30
  4691.1  685.12  4693.7  685.12  4701.6  684.07  4733.2  682.73  4785.9  679.76
  4796.5  679.71  4828.1  678.39  4838.6  677.62  4870.3  676.42    4923  675.26
  4933.5  674.55  4975.7  673.36  4996.8  672.43  5004.7   671.7  5009.8   671.7
  5015.5  670.77  5015.7  670.27  5019.2  670.27  5019.5  670.77  5037.9  671.91
  5048.1  672.17  5078.7  674.73  5088.9   675.9  5109.3  676.52  5139.9  678.64
  5150.1  679.69  5231.7  683.35    5252  686.35  5259.7  688.14  5262.2  688.14
#Mann= 3 ,-1 , 0
  4691.1     .05       0  5015.5    .033       0  5019.5     .05       0
Bank Sta=5015.5,5019.5
XS Rating Curve= 0 ,0
Exp/Cntr=0.3,0.1

Type RM Length L Ch R = 1 ,3742    ,239,239,239
BEGIN DESCRIPTION:
Stream HEN-6 10.0
END DESCRIPTION:
XS GIS Cut Line= 3
      2335478.98      7036759.97        2335579.        7036960.
      2335878.96        7036960.
#Sta/Elev= 30
  4776.4  677.35  4784.8  677.59  4790.4  677.31  4798.8  676.02  4857.5  673.62
  4865.9  673.04  4888.2  672.46  4910.6  671.43  4946.9  670.31  4969.3  668.75
  4977.7   668.6  4986.1  667.73  4994.2  667.26    5010  666.56    5018  665.33
  5018.3  664.83  5021.8  664.83    5022  665.33    5030  667.56  5044.3  667.97
    5090  668.75    5130  671.28    5180  673.79    5190  675.27    5220   675.7
    5240  676.41    5270  678.17    5280  678.41    5290  679.57    5300  679.91
#Mann= 5 ,-1 , 0
  4776.4     .05       0  4994.2     .12       0    5018     .07       0
    5022     .12       0  5044.3     .05       0
Bank Sta=5018,5022
XS Rating Curve= 0 ,0
Exp/Cntr=0.3,0.1

Type RM Length L Ch R = 1 ,3503    ,243,243,243
BEGIN DESCRIPTION:
Stream HEN-6 9.0
END DESCRIPTION:
XS GIS Cut Line= 3
      2335279.01        7037160.        2335479.        7037160.
      2335679.01        7037160.
#Sta/Elev= 30
  4800.1  674.13  4802.6  674.13  4830.1  672.41  4840.1  671.08  4860.1   670.3
  4870.1  669.32  4880.1  668.85  4890.1  667.88  4900.1  666.34  4920.1  664.28
  4930.1  663.78  4940.1   663.6  4970.1  663.85  4987.4  663.52  4997.6  663.06
  5010.1  662.73  5018.1  662.01  5018.3  661.51  5021.8  661.51  5022.1  662.01
  5030.1  663.36  5040.1  664.78  5070.1  666.77  5080.1  668.11  5100.1  669.79
  5120.1  670.84  5126.6  671.02  5140.1   671.5  5160.1  671.79  5200.1  673.27
#Mann= 5 ,-1 , 0
  4800.1     .05       0  4987.4     .12       0  5018.1     .07       0
  5022.1     .12       0  5126.6     .05       0
Bank Sta=5018.1,5022.1
XS Rating Curve= 0 ,0
Exp/Cntr=0.3,0.1

Type RM Length L Ch R = 1 ,3260    ,305,305,305
BEGIN DESCRIPTION:
Stream HEN-6 8.0
END DESCRIPTION:
XS GIS Cut Line= 3
      2335228.98        7037410.      2335429.44      7037385.99
      2335702.42      7037419.36
#Sta/Elev= 30
    4799  673.17  4849.4  671.44  4869.5  670.17  4879.6  669.93  4889.7  670.94
  4899.7  668.57    4925   667.5  4930.1  671.46  4980.3  670.03  5003.2  670.14
  5010.5  665.16  5018.6  660.43  5018.8  659.93  5022.3  659.93  5022.6  660.43
  5030.7  667.93  5040.7  669.33  5070.5  669.09  5075.6  670.78  5077.9  670.94
  5131.4  670.96  5157.1  671.74  5162.1  668.98  5181.8  669.45  5191.9  669.27
  5201.9  668.35    5212  668.38  5238.6  669.85  5243.6  669.47  5275.9     671
#Mann= 4 ,-1 , 0
    4799     .05       0  5018.6    .033       0  5022.6     .05       0
  5077.9     .12       0
Bank Sta=5018.6,5022.6
XS Rating Curve= 0 ,0
Exp/Cntr=0.3,0.1

Type RM Length L Ch R = 1 ,2955    ,266,266,266
BEGIN DESCRIPTION:
Stream HEN-6 7.0
END DESCRIPTION:
XS GIS Cut Line= 3
      2335229.04      7037560.01        2335529.        7037660.
        2335679.        7037610.
#Sta/Elev= 30
  4683.4  670.93    4686  670.93  4746.6  667.11  4788.8  664.69  4799.3  663.89
  4809.8  662.39  4820.4  661.36  4830.9  660.77    4852  659.12  4862.6  659.45
  4883.6  658.49  4894.2   658.8  4915.3  657.99  4925.8   658.2  4946.9  657.83
  4957.4  656.45  4978.5   656.1    4987  655.34  4987.3  654.84  4990.8  654.84
    4991  655.34  4996.9  657.24  5002.2  657.24  5010.1  657.74  5031.2  657.61
  5041.7  657.86  5073.4  660.55    5105  664.84  5155.1  668.11  5157.7  668.11
#Mann= 3 ,-1 , 0
  4683.4     .05       0    4987    .033       0    4991     .05       0
Bank Sta=4987,4991
XS Rating Curve= 0 ,0
Exp/Cntr=0.3,0.1

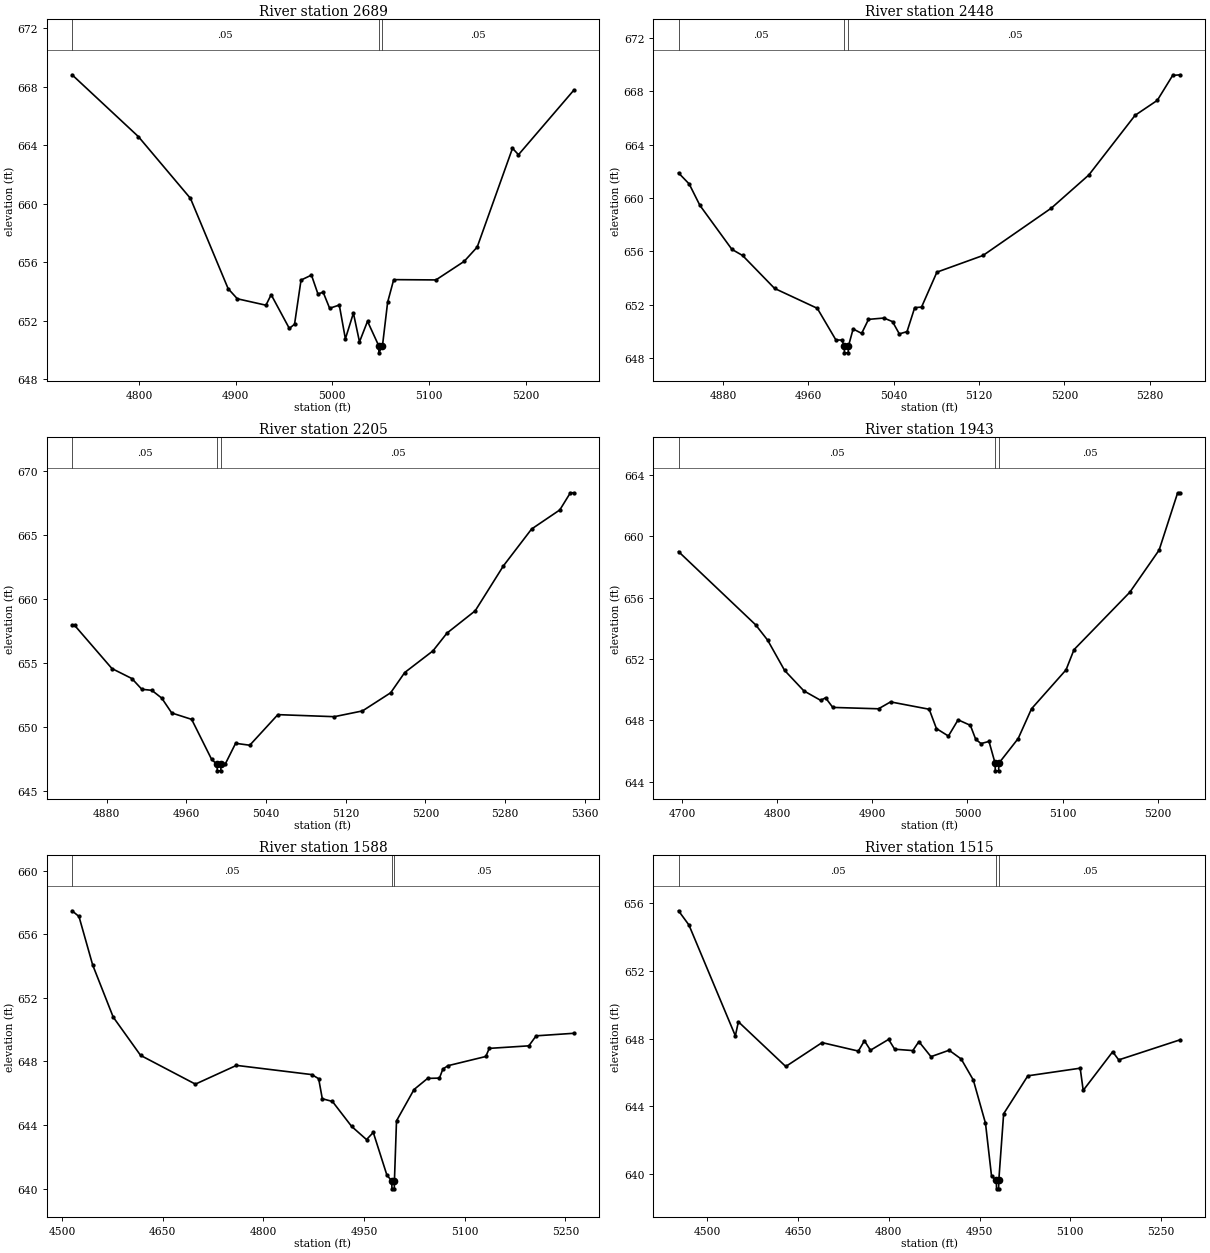
Type RM Length L Ch R = 1 ,2689    ,241,241,241
BEGIN DESCRIPTION:
Stream HEN-6 6.0
END DESCRIPTION:
XS GIS Cut Line= 3
      2335329.02      7038009.99        2335579.        7037910.
      2335728.98      7037710.03
#Sta/Elev= 30
  4730.8  668.83  4799.4   664.6  4853.3  660.37  4892.3  654.19  4901.8   653.5
  4931.4  653.06  4936.8  653.78  4955.6  651.47    4961  651.76  4967.7  654.78
  4978.5  655.12  4985.2  653.83  4990.6  653.95  4997.3  652.85  5007.3  653.07
  5013.6  650.76  5021.9  652.52  5028.2  650.55  5036.5  651.96    5048   650.3
  5048.3   649.8    5052   650.3  5057.3  653.26  5063.6  654.81  5107.3  654.79
  5136.5  656.06    5150  657.04  5186.5   663.8  5192.7  663.36    5250  667.78
#Mann= 3 ,-1 , 0
  4730.8     .05       0    5048    .033       0    5052     .05       0
Bank Sta=5048,5052
XS Rating Curve= 0 ,0
Exp/Cntr=0.3,0.1

Type RM Length L Ch R = 1 ,2448    ,243,243,243
BEGIN DESCRIPTION:
Stream HEN-6 5.0
END DESCRIPTION:
XS GIS Cut Line= 3
      2335478.97        7038110.        2335629.        7038110.
      2335879.01      7037909.99
#Sta/Elev= 30
  4838.4  661.88  4848.4  661.05  4858.4  659.45  4888.4  656.15  4898.4  655.69
  4928.4  653.22  4968.4  651.73  4985.9  649.35  4991.6  649.35  4993.6  648.89
  4993.9  648.39  4997.4  648.39  4997.6  648.89    5002  650.18    5010  649.85
  5016.4   650.9  5030.9     651  5038.9  650.73  5045.3  649.81  5052.5  649.98
  5059.7  651.78  5066.1  651.82  5080.5  654.44  5123.7  655.69  5187.7  659.24
  5222.9  661.73  5266.2   666.2    5287  667.32  5301.4  669.19  5308.6  669.24
#Mann= 3 ,-1 , 0
  4838.4     .05       0  4993.6    .033       0  4997.6     .05       0
Bank Sta=4993.6,4997.6
XS Rating Curve= 0 ,0
Exp/Cntr=0.3,0.1

Type RM Length L Ch R = 1 ,2205    ,262,262,262
BEGIN DESCRIPTION:
Stream HEN-6 4.0
END DESCRIPTION:
XS GIS Cut Line= 3
      2335579.03        7038310.        2335729.        7038310.
      2335978.99      7038060.01
#Sta/Elev= 30
  4845.4  657.97  4847.9  657.97  4885.4  654.59  4905.4  653.81  4915.4  652.97
  4925.4  652.89  4935.4  652.28  4945.4  651.12  4965.4  650.62  4985.4   647.5
  4990.9   647.1  4991.1   646.6  4994.6   646.6  4994.9   647.1  4998.9   647.1
  5009.5  648.75  5023.7   648.6  5051.9  650.99  5108.5  650.83  5136.8  651.28
  5165.1   652.7  5179.2  654.28  5207.5  655.97  5221.6  657.36  5249.9   659.1
  5278.2  662.61  5306.5  665.49  5334.8  666.98  5345.4  668.32  5348.9  668.32
#Mann= 3 ,-1 , 0
  4845.4     .05       0  4990.9    .033       0  4994.9     .05       0
Bank Sta=4990.9,4994.9
XS Rating Curve= 0 ,0
Exp/Cntr=0.3,0.1

Type RM Length L Ch R = 1 ,1943    ,355,355,355
BEGIN DESCRIPTION:
Stream HEN-6 3.0
END DESCRIPTION:
XS GIS Cut Line= 3
      2335579.03      7038509.99        2335879.        7038460.
      2336078.99      7038360.01
#Sta/Elev= 30
  4696.2  659.01  4777.3  654.23  4789.9  653.23  4807.7  651.26    4828  649.92
  4845.7   649.3  4850.8  649.47  4858.4  648.84  4906.5  648.75  4919.2   649.2
  4959.8  648.72  4967.4  647.46    4980  646.97  4990.2  648.03  5003.1  647.67
  5008.7  646.76  5014.3  646.48  5022.7  646.62  5029.1   645.2  5029.3   644.7
  5032.8   644.7  5033.1   645.2  5053.4  646.81  5067.4  648.75  5103.7  651.29
  5112.1  652.61  5170.8  656.36  5201.6  659.11  5221.1  662.85  5223.9  662.85
#Mann= 3 ,-1 , 0
  4696.2     .05       0  5029.1    .033       0  5033.1     .05       0
Bank Sta=5029.1,5033.1
XS Rating Curve= 0 ,0
Exp/Cntr=0.3,0.1

Type RM Length L Ch R = 1 ,1588    ,73,73,73
BEGIN DESCRIPTION:
Stream HEN-6 2.0
END DESCRIPTION:
XS GIS Cut Line= 3
      2335628.96      7038609.99      2336040.08      7038694.34
      2336364.56      7038645.67
#Sta/Elev= 30
  4514.9  657.48  4525.2  657.12  4545.6  654.07  4576.2  650.79    4617  648.38
  4698.7  646.57  4759.9  647.75  4872.2  647.17  4882.4  646.91  4887.8  645.65
  4902.9  645.48  4931.5  643.91  4953.7  643.08  4963.8  643.53  4984.1  640.84
  4991.3  640.48  4991.6  639.98  4995.1  639.98  4995.3  640.48  4998.4  644.26
  5024.5  646.23  5044.7  646.93  5062.4  646.95  5067.5  647.52  5075.1  647.73
  5131.5  648.31  5136.6  648.82  5195.6  648.98  5206.5  649.61  5262.7  649.77
#Mann= 3 ,-1 , 0
  4514.9     .05       0  4991.3    .033       0  4995.3     .05       0
Bank Sta=4991.3,4995.3
XS Rating Curve= 0 ,0
Exp/Cntr=0.3,0.1

Type RM Length L Ch R = 1 ,1515    ,271,271,271
BEGIN DESCRIPTION:
Stream HEN-6 1.0
END DESCRIPTION:
XS GIS Cut Line= 3
      2335581.78      7038756.09      2336150.58      7038749.59
      2336410.63      7038764.22
#Sta/Elev= 30
  4452.6  655.55  4469.8  654.71  4546.5  648.17  4551.5     649  4629.8  646.36
  4689.8  647.77  4749.8  647.27  4759.8  647.88  4769.8  647.32  4799.8  647.96
  4809.8  647.38  4839.8   647.3  4849.8  647.83  4869.8  646.94  4899.8  647.32
  4919.8   646.8  4939.8  645.56  4959.9  643.01  4969.9  639.89  4977.9  639.64
  4978.1  639.14  4981.6  639.14  4981.9  639.64  4989.9  643.57  5029.9  645.81
  5116.4  646.26  5121.4  644.95  5170.1  647.23  5180.1  646.75  5281.9  647.94
#Mann= 3 ,-1 , 0
  4452.6     .05       0  4977.9     .05       0  4981.9     .05       0
Bank Sta=4977.9,4981.9
XS Rating Curve= 0 ,0
Exp/Cntr=0.3,0.1

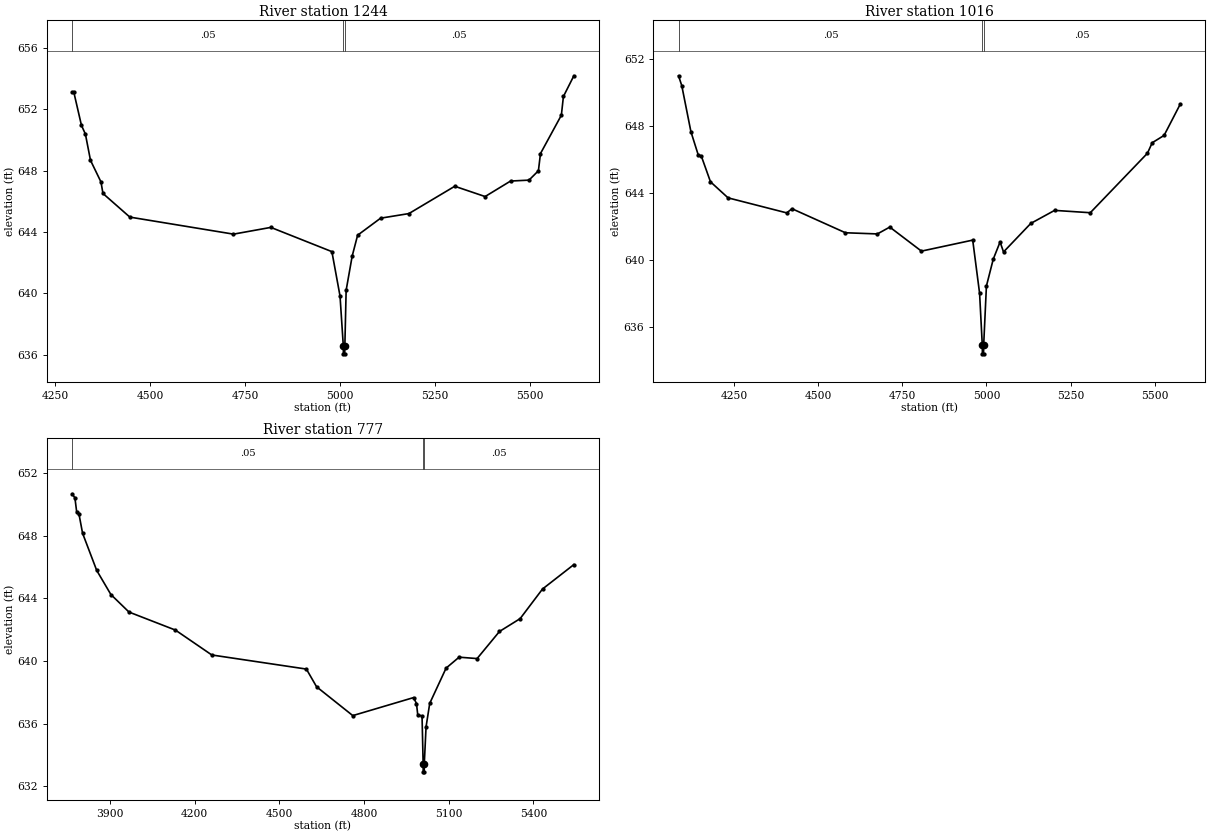
Type RM Length L Ch R = 1 ,1244    ,228,228,228
BEGIN DESCRIPTION:
Stream HEN-6 0.4
END DESCRIPTION:
XS GIS Cut Line= 3
      2335605.41      7038781.47      2336239.96      7038975.47
       2336854.9      7038743.45
#Sta/Elev= 30
  4293.9  653.12  4298.4  653.12  4318.6  650.95    4329  650.38  4342.4  648.67
    4370  647.26  4375.2  646.51    4446  644.97  4718.8  643.86  4817.1   644.3
  4977.8  642.72  4999.2  639.83  5007.9  636.56  5008.1  636.06  5011.6  636.06
  5011.9  636.56  5015.3   640.2  5031.2  642.43  5045.5  643.79    5106   644.9
  5180.5   645.2  5301.2  646.98  5381.1  646.31  5448.1  647.32  5496.6  647.38
  5521.4  647.99  5526.8  649.11  5581.8  651.61  5587.2  652.83  5614.7  654.18
#Mann= 3 ,-1 , 0
  4293.9     .05       0  5007.9     .05       0  5011.9     .05       0
Bank Sta=5007.9,5011.9
XS Rating Curve= 0 ,0
Exp/Cntr=0.3,0.1

Type RM Length L Ch R = 1 ,1016    ,239,239,239
BEGIN DESCRIPTION:
Stream HEN-6 0.3
END DESCRIPTION:
XS GIS Cut Line= 4
      2335599.31      7038817.86      2336191.21       7039178.6
      2336511.34      7039121.73      2336845.09      7038787.99
#Sta/Elev= 30
  4085.5  651.02  4095.1  650.43  4122.3  647.67  4143.7   646.3  4153.2  646.21
  4180.4  644.67  4232.6  643.71  4406.9  642.81  4422.4  643.06  4581.2  641.62
  4676.1  641.55  4712.9  641.96  4806.9  640.52  4959.2  641.18  4979.6     638
  4987.7  634.87    4988  634.37  4991.5  634.37  4991.7  634.87  4999.9  638.43
  5020.2  640.04  5040.5  641.07  5050.7  640.47  5131.7  642.18  5202.4  642.96
  5308.4  642.82  5478.1  646.38  5492.3  647.01  5527.6  647.45  5575.8  649.33
#Mann= 3 ,-1 , 0
  4085.5     .05       0  4987.7     .05       0  4991.7     .05       0
Bank Sta=4987.7,4991.7
XS Rating Curve= 0 ,0
Exp/Cntr=0.3,0.1

Type RM Length L Ch R = 1 ,777     ,0,0,0
BEGIN DESCRIPTION:
Stream HEN-6 0.2
END DESCRIPTION:
XS GIS Cut Line= 5
      2335529.58      7038836.09      2336329.34      7039443.49
      2336519.47      7039352.48       2336813.6      7038877.97
      2336816.87      7038877.97
#Sta/Elev= 30
  3766.4  650.67  3776.5  650.41  3782.8   649.5  3790.8  649.38  3803.6  648.15
  3853.6  645.78  3903.8  644.24  3967.9  643.12  4132.2  641.97  4261.1  640.38
    4596  639.48  4632.1  638.35  4760.3  636.51  4975.5  637.66  4985.8  637.28
  4990.2  636.57  5005.5  636.48  5009.4  633.42  5009.7  632.92  5013.2  632.92
  5013.4  633.42  5019.7  635.79  5032.7  637.29  5090.6  639.54  5136.7  640.24
  5200.4  640.15  5279.6  641.88  5352.8   642.7    5432  644.59    5543  646.15
#Mann= 3 ,-1 , 0
  3766.4     .05       0  5009.4     .05       0  5013.4     .05       0
Bank Sta=5009.4,5013.4
XS Rating Curve= 0 ,0
Exp/Cntr=0.3,0.1

Chan Stop Cuts=-1
Use User Specified Reach Order=0
Composite Channel Slope=5