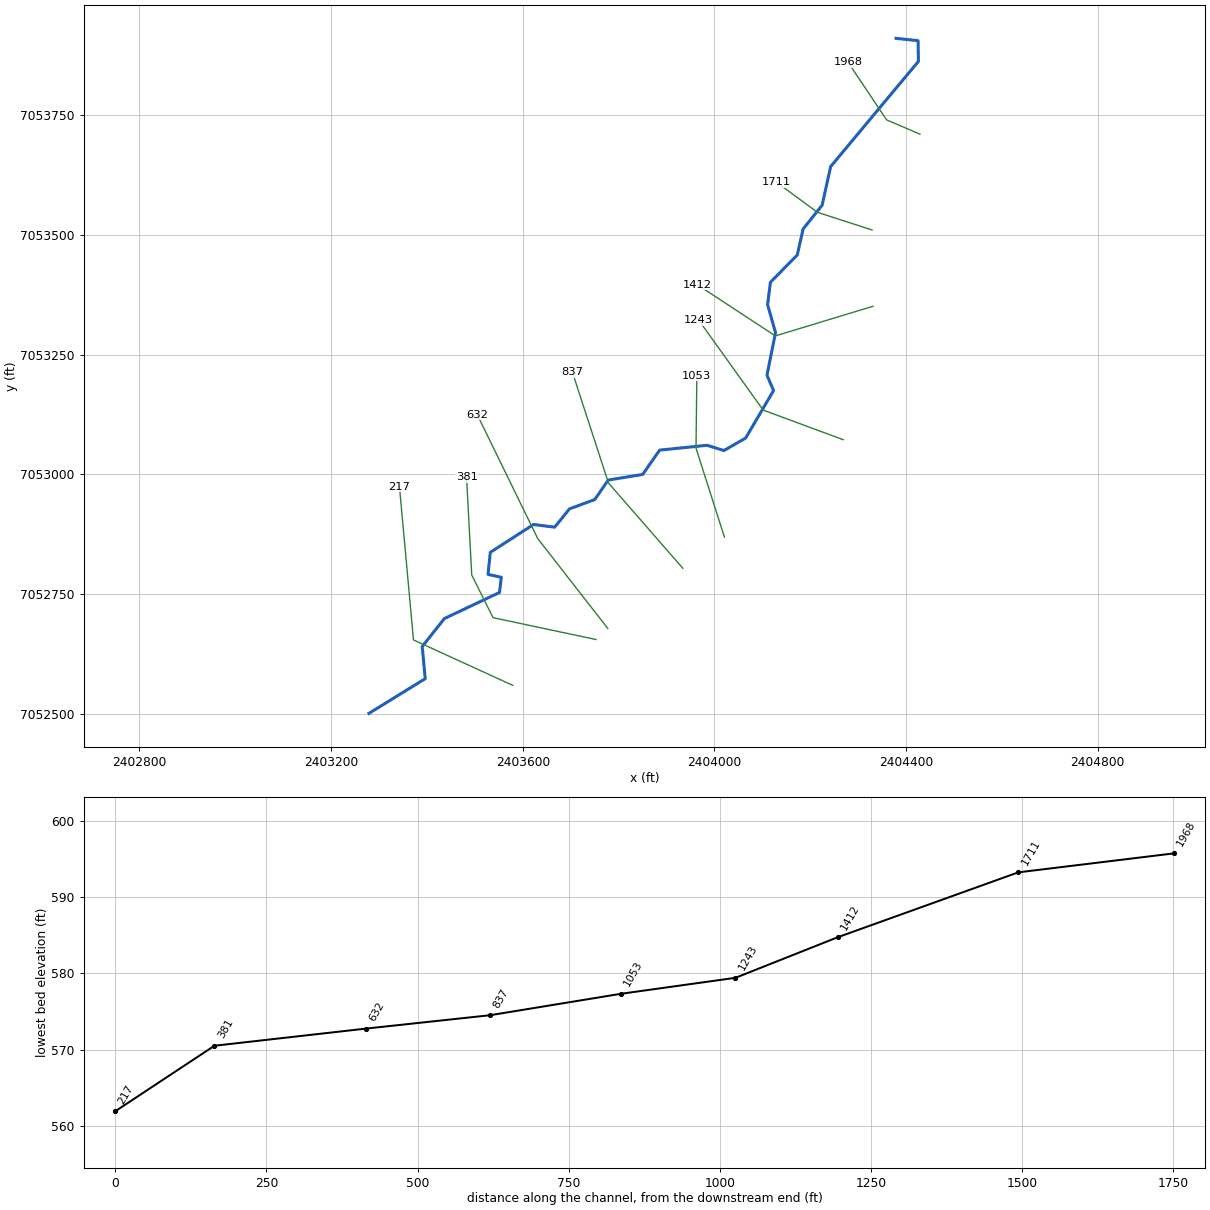
--- Tr 1 to McKamy Creek.prj (project) ---

Proj Title=Tr 1 to McKamy Creek Base Level Engineering
Current Plan=p01
Default Exp/Contr=0.3,0.1
English Units
Geom File=g01
Flow File=f01
Plan File=p01
Y Axis Title=Elevation
X Axis Title(PF)=Main Channel Distance
X Axis Title(XS)=Station
BEGIN DESCRIPTION:
Tr 1 to McKamy Creek
END DESCRIPTION:
DSS Export Rating Curves= 0
DSS Export Rating Curve Sorted= 0
DSS Export Volume Flow Curves= 0
DXF OffsetX= 0
DXF OffsetY= 0
DXF ScaleX= 1
DXF ScaleY= 10

--- Tr 1 to McKamy Creek.p01 (plan) ---

Plan Title=Multiple Run
Short Identifier=Multiple
Geom File=g01
Flow File=f01
Subcritical Flow
K Sum by GR= 0
Std Step Tol= 0.01
Critical Tol= 0.01
Num of Std Step Trials= 20
Max Error Tol= 0.3
Flow Tol Ratio= 0.001
Split Flow NTrial= 30
Split Flow Tol= 0.02
Split Flow Ratio= 0.02
Log Output Level= 0
Friction Slope Method= 1
Unsteady Friction Slope Method= 2
Unsteady Bridges Friction Slope Method= 1
Parabolic Critical Depth
Global Vel Dist=  1 , 1 , 1
Global Log Level= 0
CheckData=True
Encroach Param= -1, 0, 0, 0
BEGIN DESCRIPTION:
Multiple Run
END DESCRIPTION:

--- Tr 1 to McKamy Creek.f01 (steady flow) ---

Flow Title=Multiple
Program Version=4.10
Number of Profiles= 7
Profile Names=10-year,25-year,50-year,1pct_min,100-year,1pct_plu,500-year
River Rch & RM=Tr 1 to McKamy C,Reach-1         ,1968
      85     102     114      64     128     255     159
River Rch & RM=Tr 1 to McKamy C,Reach-1         ,1243
     161     204     236     137     274     546     366
Boundary for River Rch & Prof#=Tr 1 to McKamy C,Reach-1         , 1
Up Type= 0
Dn Type= 3
Dn Slope=0.025
Boundary for River Rch & Prof#=Tr 1 to McKamy C,Reach-1         , 2
Up Type= 0
Dn Type= 3
Dn Slope=0.025
Boundary for River Rch & Prof#=Tr 1 to McKamy C,Reach-1         , 3
Up Type= 0
Dn Type= 3
Dn Slope=0.025
Boundary for River Rch & Prof#=Tr 1 to McKamy C,Reach-1         , 4
Up Type= 0
Dn Type= 3
Dn Slope=0.025
Boundary for River Rch & Prof#=Tr 1 to McKamy C,Reach-1         , 5
Up Type= 0
Dn Type= 3
Dn Slope=0.025
Boundary for River Rch & Prof#=Tr 1 to McKamy C,Reach-1         , 6
Up Type= 0
Dn Type= 3
Dn Slope=0.025
Boundary for River Rch & Prof#=Tr 1 to McKamy C,Reach-1         , 7
Up Type= 0
Dn Type= 3
Dn Slope=0.025
DSS Import GetInterval= 0
DSS Import GetPeak= 0
DSS Import FillOption= 0

--- Tr 1 to McKamy Creek.g01 (geometry) ---

Geom Title=Existing Conditions
Program Version=4.10

River Reach=Tr 1 to McKamy C,Reach-1
Reach XY= 30
        2404379.        7053910.      2404425.03       7053905.1
      2404425.78      7053861.91      2404242.55      7053642.35
      2404224.81      7053561.74      2404185.08       7053512.2
      2404172.88      7053457.82      2404116.86       7053400.9
      2404110.95      7053354.03      2404127.49      7053295.85
      2404109.65      7053206.74      2404123.45      7053174.97
      2404065.17      7053075.75      2404019.86      7053049.71
       2403984.7      7053060.65      2403885.69      7053050.56
      2403850.28      7052999.86       2403778.4      7052988.06
      2403750.28      7052947.43       2403697.5      7052927.99
       2403666.6      7052889.79      2403622.51      7052895.36
      2403532.23       7052837.2      2403527.45       7052791.2
      2403555.23      7052785.12      2403551.33      7052753.44
      2403436.49      7052699.05      2403390.13      7052640.71
      2403396.38      7052573.53      2403278.94      7052501.13

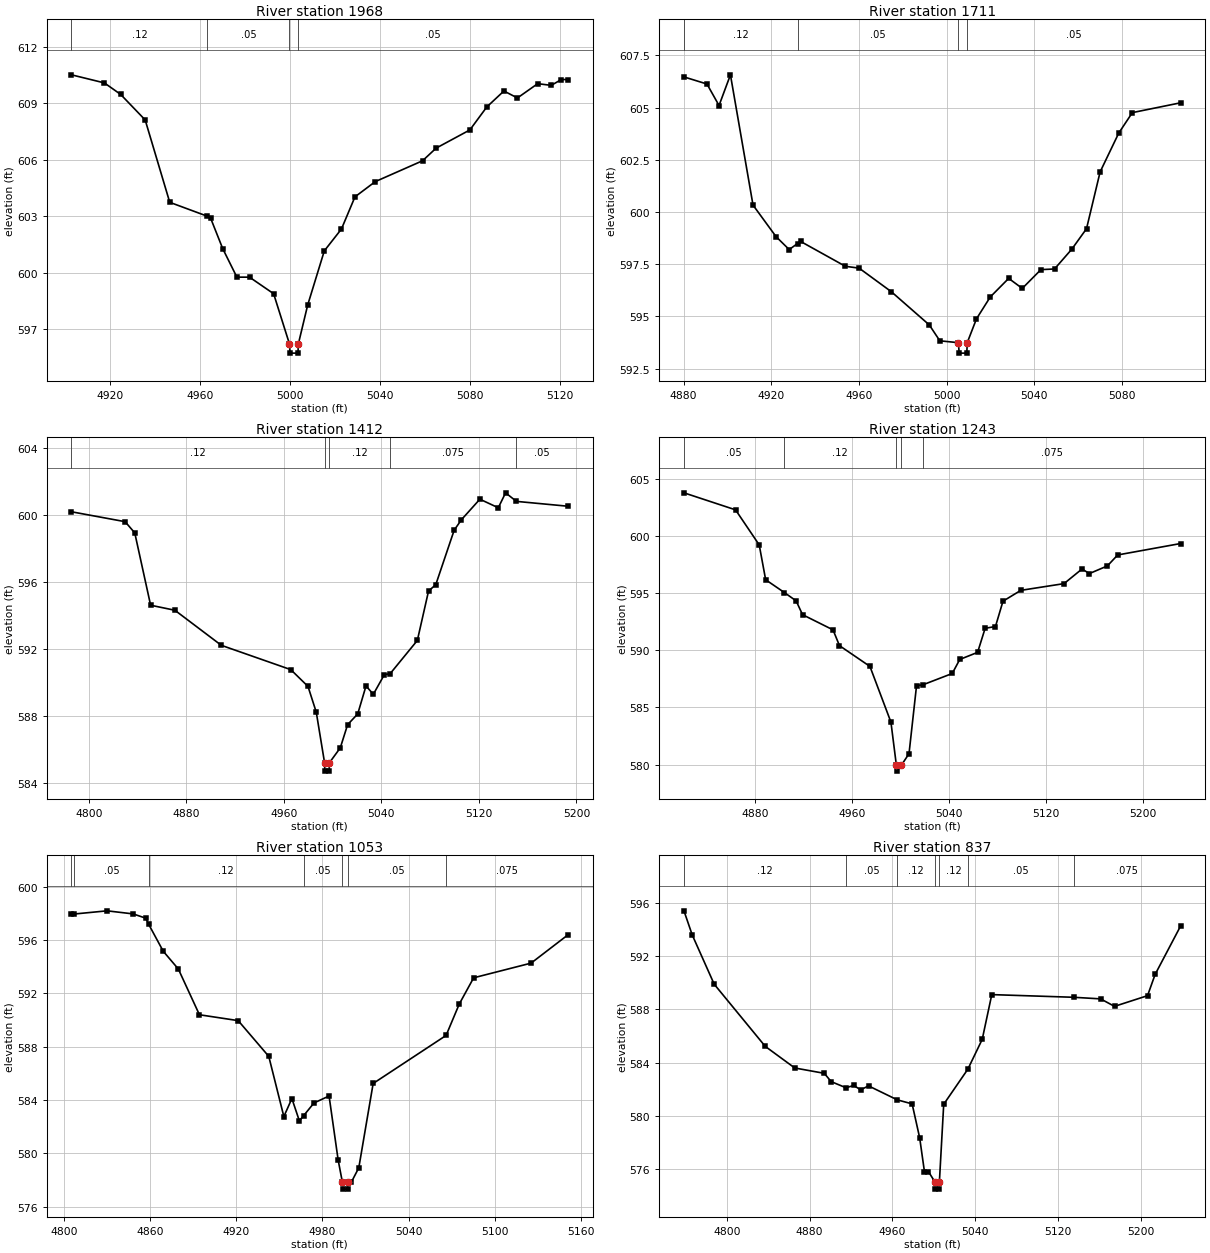
Type RM Length L Ch R = 1 ,1968    ,257,257,257
BEGIN DESCRIPTION:
Tr 1 to McKamy Creek 6.0
END DESCRIPTION:
XS GIS Cut Line= 3
      2404429.05      7053709.98      2404359.22      7053739.91
      2404278.99      7053860.01
#Sta/Elev= 30
  4903.1  610.52  4917.7  610.09  4924.9  609.48  4935.8  608.12  4946.7  603.74
  4963.4     603  4964.8  602.91  4970.2  601.28  4976.5  599.76  4982.1  599.76
  4992.8  598.88  4999.8  596.22  5000.1  595.72  5003.6  595.72  5003.8  596.22
  5007.9  598.27  5015.3  601.16  5022.9  602.32  5028.9  604.03  5037.9  604.84
  5058.9  605.95  5064.9  606.62  5079.9  607.59  5087.4  608.81    5095  609.66
    5101  609.29    5110  610.05    5116  609.96  5120.5  610.27  5123.5  610.27
#Mann= 4 ,-1 , 0
  4903.1     .12       0  4963.4     .05       0  4999.8    .033       0
  5003.8     .05       0
Bank Sta=4999.8,5003.8
XS Rating Curve= 0 ,0
Exp/Cntr=0.3,0.1

Type RM Length L Ch R = 1 ,1711    ,299,299,299
BEGIN DESCRIPTION:
Tr 1 to McKamy Creek 5.0
END DESCRIPTION:
XS GIS Cut Line= 3
      2404328.98      7053510.01      2404215.02      7053546.94
      2404128.97      7053610.03
#Sta/Elev= 30
  4880.2  606.47  4890.7  606.13  4896.2   605.1  4901.4  606.57  4911.7  600.33
  4922.2  598.82  4928.2   598.2    4932  598.49  4933.4  598.59  4953.8   597.4
  4960.1  597.31  4974.8  596.18  4992.1  594.59  4996.9  593.83  5005.4  593.74
  5005.7  593.24  5009.2  593.24  5009.4  593.74  5013.6  594.88  5019.9  595.93
  5028.3  596.82  5034.5  596.34    5043  597.24  5049.2  597.27  5057.1  598.22
  5063.8   599.2    5070  601.92  5078.5  603.78  5084.7  604.76  5106.7  605.23
#Mann= 4 ,-1 , 0
  4880.2     .12       0    4932     .05       0  5005.4    .033       0
  5009.4     .05       0
Bank Sta=5005.4,5009.4
XS Rating Curve= 0 ,0
Exp/Cntr=0.3,0.1

Type RM Length L Ch R = 1 ,1412    ,169,169,169
BEGIN DESCRIPTION:
Mapping XS ac18aa7f
END DESCRIPTION:
XS GIS Cut Line= 3
      2404331.12      7053350.83      2404127.16      7053288.99
      2403964.69      7053395.51
#Sta/Elev= 30
  4785.8  600.19  4829.8   599.6  4837.7  598.93  4850.7  594.62  4870.6  594.32
  4908.7  592.23  4965.7  590.78  4979.8  589.78  4986.6  588.24  4993.4  585.23
  4993.6  584.73  4997.1  584.73  4997.4  585.23  5006.3  586.12  5012.3   587.5
  5020.6  588.14  5027.4  589.81  5033.4  589.31  5042.5  590.49  5047.1  590.53
  5069.5  592.52  5078.7  595.47  5084.6  595.84  5099.7  599.09  5105.7  599.72
  5120.8  600.94  5135.9  600.43  5141.9  601.32  5150.8  600.81  5193.2  600.52
#Mann= 5 ,-1 , 0
  4785.8     .12       0  4993.4     .07       0  4997.4     .12       0
  5047.1    .075       0  5150.8     .05       0
Bank Sta=4993.4,4997.4
XS Rating Curve= 0 ,0
Exp/Cntr=0.3,0.1

Type RM Length L Ch R = 1 ,1243    ,190,190,190
BEGIN DESCRIPTION:
Mapping XS b201741f
END DESCRIPTION:
XS GIS Cut Line= 3
      2404268.88      7053072.26      2404101.77      7053134.11
      2403967.24      7053321.79
#Sta/Elev= 30
  4821.6  603.79  4864.1   602.3  4883.6  599.23  4888.9  596.18  4904.3  595.06
    4914  594.33  4919.3  593.12  4944.4  591.79  4949.7  590.41  4974.8  588.59
  4992.1  583.71  4996.6  579.92  4996.8  579.42  5000.6  579.92    5007  580.95
  5013.2  586.91  5018.2  586.97  5042.6  587.97  5048.8   589.2  5063.5  589.82
  5069.7  591.93  5078.2  592.08  5084.4   594.3  5099.1  595.25  5134.7  595.84
  5149.5  597.12  5155.6  596.72  5170.4  597.39  5178.9  598.35  5230.7  599.35
#Mann= 5 ,-1 , 0
  4821.6     .05       0  4904.3     .12       0  4996.6     .07       0
  5000.6     .12       0  5018.2    .075       0
Bank Sta=4996.6,5000.6
XS Rating Curve= 0 ,0
Exp/Cntr=0.3,0.1

Type RM Length L Ch R = 1 ,1053    ,216,216,216
BEGIN DESCRIPTION:
Tr 1 to McKamy Creek 3.0
END DESCRIPTION:
XS GIS Cut Line= 3
      2404020.81       7052869.1      2403961.53      7053054.66
       2403963.3      7053205.75
#Sta/Elev= 30
  4805.2  597.94    4807  597.94    4830  598.18  4848.1  597.95  4856.9  597.63
    4859  597.16  4869.1  595.15  4879.6  593.82  4894.3  590.39  4921.3  589.95
  4942.6  587.27  4953.1  582.76  4958.7  584.11  4963.9  582.44  4966.9  582.83
  4974.1  583.78  4984.6   584.3  4990.9  579.52  4993.9  577.82  4994.2  577.32
  4997.7  577.32  4997.9  577.82    5000  577.82  5005.3  578.92  5015.3  585.24
  5066.1  588.84  5075.3   591.2  5085.3  593.16  5125.3  594.26  5151.1  596.39
#Mann= 7 ,-1 , 0
  4805.2     .12       0    4807     .05       0    4859     .12       0
  4966.9     .05       0  4993.9    .033       0  4997.9     .05       0
  5066.1    .075       0
Bank Sta=4993.9,4997.9
XS Rating Curve= 0 ,0
Exp/Cntr=0.3,0.1

Type RM Length L Ch R = 1 ,837     ,205,205,205
BEGIN DESCRIPTION:
Mapping XS b0031d2b
END DESCRIPTION:
XS GIS Cut Line= 3
        2403934.      7052803.98      2403778.85      7052981.92
      2403703.49      7053213.38
#Sta/Elev= 30
  4758.7  595.38  4766.7  593.57  4787.9  589.88  4837.2  585.22  4865.7   583.6
  4894.2   583.2  4900.8  582.58  4915.1  582.12  4922.7  582.29  4929.3  581.96
  4936.9  582.26  4964.7  581.21    4979  580.91  4986.3  578.36  4990.9  575.83
  4994.8  575.83  5001.3  575.02  5001.5  574.52    5005  574.52  5005.3  575.02
  5009.5  580.88  5032.8  583.51  5046.7  585.75  5055.9   589.1  5134.9   588.9
    5161  588.78  5174.4  588.22  5206.3  589.02  5213.6  590.61  5238.2  594.24
#Mann= 7 ,-1 , 0
  4758.7     .12       0  4915.1     .05       0  4964.7     .12       0
  5001.3     .07       0  5005.3     .12       0  5032.8     .05       0
  5134.9    .075       0
Bank Sta=5001.3,5005.3
XS Rating Curve= 0 ,0
Exp/Cntr=0.3,0.1

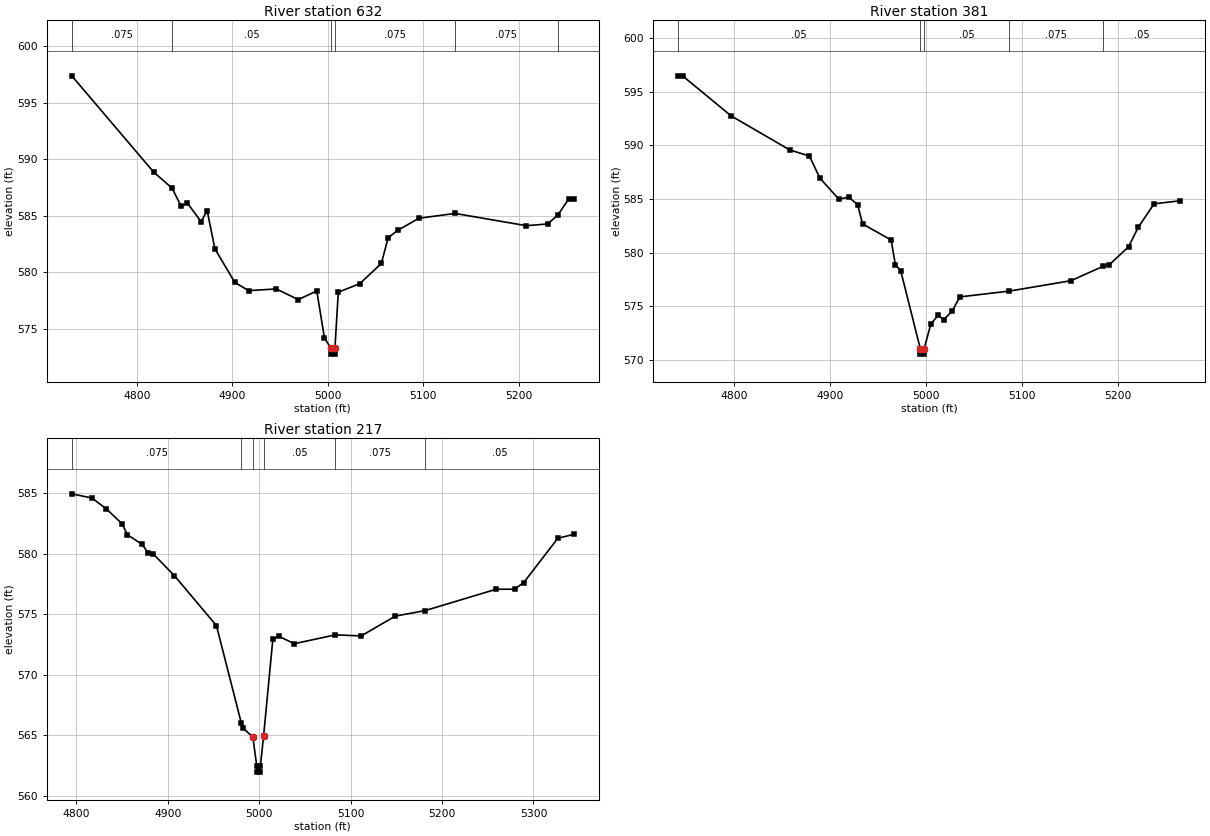
Type RM Length L Ch R = 1 ,632     ,251,251,251
BEGIN DESCRIPTION:
Tr 1 to McKamy Creek 2.0
END DESCRIPTION:
XS GIS Cut Line= 3
       2403777.4       7052678.4      2403631.26      7052865.88
      2403504.86      7053124.75
#Sta/Elev= 30
    4732  597.36  4817.7  588.86  4837.1  587.43  4846.6  585.82  4852.9  586.14
  4867.4  584.48  4873.8  585.44  4881.9  582.07  4902.7  579.11  4917.2  578.38
  4946.1  578.53  4969.2  577.59  4988.6  578.35  4996.6   574.2  5003.6  573.27
  5003.8  572.77  5007.3  572.77  5007.6  573.27  5011.1  578.24  5033.7     579
  5056.2  580.78  5063.3  583.05  5073.2   583.7  5095.7  584.78  5133.4   585.2
    5208  584.12  5230.3  584.27    5241  585.06  5252.4  586.47  5257.8  586.47
#Mann= 6 ,-1 , 0
    4732    .075       0  4837.1     .05       0  5003.6    .033       0
  5007.6    .075       0  5133.4    .075       0    5241     .05       0
Bank Sta=5003.6,5007.6
XS Rating Curve= 0 ,0
Exp/Cntr=0.3,0.1

Type RM Length L Ch R = 1 ,381     ,164,164,164
BEGIN DESCRIPTION:
Mapping XS 8cbfeea7
END DESCRIPTION:
XS GIS Cut Line= 4
      2403752.76      7052655.32      2403537.96      7052700.88
      2403493.48      7052789.86      2403482.63      7052993.82
#Sta/Elev= 30
  4742.1  596.49  4746.6  596.49  4797.1  592.76  4858.4  589.57  4878.8  589.01
  4889.7  586.95  4909.5  584.98  4919.7  585.17  4929.1  584.47  4934.2  582.67
    4964  581.17  4968.4  578.87    4974   578.3  4994.4  571.02  4994.6  570.52
  4998.1  570.52  4998.4  571.02  5005.4  573.34  5013.1  574.14  5018.7  573.74
  5027.8  574.55  5035.5  575.86    5087   576.4  5151.4  577.37  5184.8  578.71
  5191.5  578.87  5211.5  580.54  5221.5  582.35  5238.1  584.55  5265.4  584.83
#Mann= 5 ,-1 , 0
  4742.1     .05       0  4994.4    .033       0  4998.4     .05       0
    5087    .075       0  5184.8     .05       0
Bank Sta=4994.4,4998.4
XS Rating Curve= 0 ,0
Exp/Cntr=0.3,0.1

Type RM Length L Ch R = 1 ,217     ,0,0,0
BEGIN DESCRIPTION:
Tr 1 to McKamy Creek 1.0
END DESCRIPTION:
XS GIS Cut Line= 3
      2403579.09      7052559.62      2403371.88      7052654.44
      2403342.58      7052974.52
#Sta/Elev= 30
  4794.9  584.93    4817  584.58  4832.7  583.69    4850  582.45  4855.7  581.55
    4872  580.75  4878.7  580.01  4884.2  579.95  4907.2  578.17  4953.2  574.04
  4980.4  565.99    4982  565.59    4993  564.84  4997.3  562.44  4997.5  561.94
    5001  561.94  5001.3  562.44  5004.8  564.96  5014.9  572.93  5021.6  573.15
  5038.4  572.55  5083.3  573.28  5111.5  573.19  5148.9  574.83  5181.3  575.28
  5259.3  577.05  5279.4  577.05  5289.4   577.6  5326.6  581.25  5344.2  581.59
#Mann= 6 ,-1 , 0
  4794.9    .075       0  4980.4     .05       0    4993    .033       0
  5004.8     .05       0  5083.3    .075       0  5181.3     .05       0
Bank Sta=4993,5004.8
XS Rating Curve= 0 ,0
Exp/Cntr=0.3,0.1

Chan Stop Cuts=-1
Use User Specified Reach Order=0
Composite Channel Slope=5