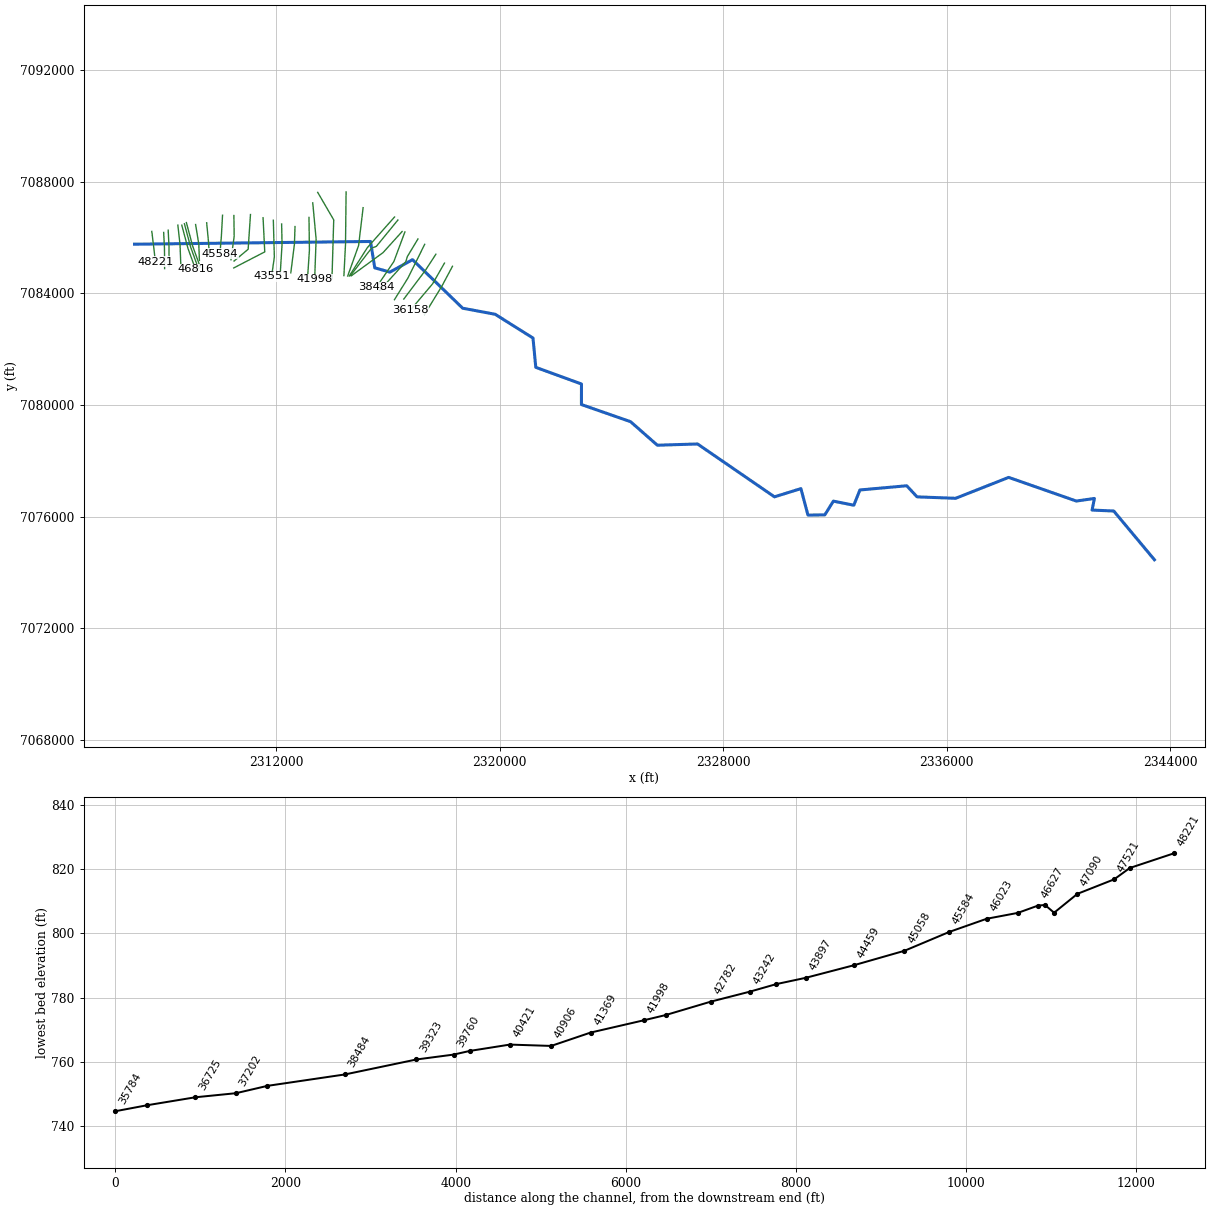
--- Trail Creek.prj (project) ---

Proj Title=Trail Creek Base Level Engineering
Current Plan=p01
Default Exp/Contr=0.3,0.1
English Units
Geom File=g01
Flow File=f01
Plan File=p01
Y Axis Title=Elevation
X Axis Title(PF)=Main Channel Distance
X Axis Title(XS)=Station
BEGIN DESCRIPTION:
Trail Creek
END DESCRIPTION:
DSS Export Rating Curves= 0
DSS Export Rating Curve Sorted= 0
DSS Export Volume Flow Curves= 0
DXF OffsetX= 0
DXF OffsetY= 0
DXF ScaleX= 1
DXF ScaleY= 10

--- Trail Creek.p01 (plan) ---

Plan Title=Multiple Run
Program Version=4.10
Short Identifier=Multiple
Geom File=g01
Flow File=f01
Subcritical Flow
K Sum by GR= 0
Std Step Tol= 0.01
Critical Tol= 0.01
Num of Std Step Trials= 20
Max Error Tol= 0.3
Flow Tol Ratio= 0.001
Split Flow NTrial= 30
Split Flow Tol= 0.02
Split Flow Ratio= 0.02
Log Output Level= 0
Friction Slope Method= 1
Unsteady Friction Slope Method= 2
Unsteady Bridges Friction Slope Method= 1
Parabolic Critical Depth
Global Vel Dist= 1 , 1 , 1
Global Log Level= 0
CheckData=True
Encroach Param=-1 ,0,0, 0
BEGIN DESCRIPTION:
Multiple Run
END DESCRIPTION:
Computation Interval=1HOUR
Output Interval=1HOUR
Run HTab= 0
Run UNet= 0
Run PostProcess= 0
Run WQNet= 0
UNET Theta= 1
UNET Theta Warmup= 1
UNET ZTol= 0.02
UNET ZSATol= 0.05
UNET MxIter= 20
UNET MaxInSteps= 0
UNET DtIC= 0
UNET DtMin= 0
UNET MaxCRTS= 20
UNET WFStab= 2
UNET SFStab= 1
UNET WFX= 1
UNET SFX= 1
UNET DSS MLevel= 4
UNET DZMax Abort= 100
UNET Convert EG Bridges= 0
UNET Use Existing IB Tables=-1
UNET Froude Reduction=False
UNET Froude Limit= 1
UNET Froude Power= 10
UNET Time Slicing=0,0, 5
UNET Junction Losses=0
Instantaneous Interval=1HOUR
Write IC File= 0
Write IC File at Sim End=0
Echo Input=False
Echo Parameters=False
Echo Output=False
Write Detailed= 0
WQ AD Non Conservative
WQ ULTIMATE=-1
WQ Max Comp Step=1HOUR
WQ Output Interval=15MIN
WQ Output Selected Increments= 0
WQ Output face flow=0
WQ Output face velocity=0
WQ Output face area=0
WQ Output face dispersion=0
WQ Output cell volume=0
WQ Output cell surface area=0
WQ Output cell continuity=0
WQ Output cumulative cell continuity=0
WQ Output face conc=0
WQ Output face dconc_dx=0
WQ Output face courant=0
WQ Output face peclet=0
WQ Output face adv mass=0
WQ Output face disp mass=0
WQ Output cell mass=0
WQ Output cell source sink temp=0
WQ Output cell source sink nsm=0
WQ Output MaxMinRange=-1
WQ Daily Max Min Mean=-1
WQ Daily Range=0
WQ Daily Time=0
WQ Create Restart=0
WQ Fixed Restart=0
WQ System Summary=0
WQ Use Fixed Temperature=0
Sorting and Armoring Iterations= 10
XS Update Threshold= 0.02
Hydraulics Update Threshold= 0.02
Energy Slope Method= 1
Volume Change Method= 0
XS Weighting Method= 0
Number of US Weighted Cross Sections= 1
Number of DS Weighted Cross Sections= 1
Upstream XS Weight=0.25
Main XS Weight=0.5
Downstream XS Weight=0.25
Number of DS XS's Weighted with US Boundary= 1
Upstream Boundary Weight= 1
Weight of XSs Associated with US Boundary= 0
Number of US XS's Weighted with DS Boundary= 1
Downstream Boundary Weight= 0.5
Weight of XSs Associated with DS Boundary= 0.5
Sediment Output Level= 4
Mass or Volume Output= 0
Output Increment Type= 1
Profile and TS Output Increment= 10
XS Output Flag= 0
XS Output Increment= 10
Disregard all LS=0
Disregard all Conn=0
Disregard all Breaches=0
Disregard all Pumps=0

--- Trail Creek.f01 (steady flow) ---

Flow Title=Multiple
Number of Profiles=7
Profile Names=10-year,25-year,50-year,1pct_min,100-year,1pct_plu,500-year
River Rch & RM= Trail Creek,Reach-1,48221
     477     648     787     476     949    1894    1383
River Rch & RM= Trail Creek,Reach-1,46627
     614     845    1037     631    1260    2514    1865
River Rch & RM= Trail Creek,Reach-1,43551
     830    1161    1440     886    1768    3528    2673
River Rch & RM= Trail Creek,Reach-1,40906
     997    1408    1757    1087    2169    4328    3315
River Rch & RM= Trail Creek,Reach-1,39323
    1108    1569    1961    1214    2423    4834    3711
River Rch & RM= Trail Creek,Reach-1,31631
    1626    2343    2962    1853    3698    7378    5782
River Rch & RM= Trail Creek,Reach-1,28892
    1763    2549    3231    2026    4042    8064    6348
River Rch & RM= Trail Creek,Reach-1,28529
    1881    2726    3461    2173    4335    8650    6828
River Rch & RM= Trail Creek,Reach-1,27066
    1474    2115    2666    1664    3319    6623    5163
River Rch & RM= Trail Creek,Reach-1,26134
    1965    2853    3625    2278    4544    9067    7168
River Rch & RM= Trail Creek,Reach-1,22119
    2075    3018    3841    2416    4822    9620    7626
River Rch & RM= Trail Creek,Reach-1,21894
    2172    3165    4032    2539    5066   10107    8026
River Rch & RM= Trail Creek,Reach-1,18406
    2205    3213    4093    2578    5143   10262    8150
River Rch & RM= Trail Creek,Reach-1,16100
    2667    3917    5017    3175    6334   12638   10133
River Rch & RM= Trail Creek,Reach-1,13813
    2869    4224    5420    3434    6853   13673   10996
River Rch & RM= Trail Creek,Reach-1,9644
    3060    4518    5806    3685    7353   14671   11836
River Rch & RM= Trail Creek,Reach-1,6203
    3111    4593    5904    3748    7479   14922   12042
River Rch & RM= Trail Creek,Reach-1,3155
    3157    4662    5992    3804    7589   15143   12218
Boundary for River Rch & Prof#=Trail Creek,Reach-1,1
Up Type=0
Dn Type=3
Dn Slope=0.0051
Boundary for River Rch & Prof#=Trail Creek,Reach-1,2
Up Type=0
Dn Type=3
Dn Slope=0.0051
Boundary for River Rch & Prof#=Trail Creek,Reach-1,3
Up Type=0
Dn Type=3
Dn Slope=0.0051
Boundary for River Rch & Prof#=Trail Creek,Reach-1,4
Up Type=0
Dn Type=3
Dn Slope=0.0051
Boundary for River Rch & Prof#=Trail Creek,Reach-1,5
Up Type=0
Dn Type=3
Dn Slope=0.0051
Boundary for River Rch & Prof#=Trail Creek,Reach-1,6
Up Type=0
Dn Type=3
Dn Slope=0.0051
Boundary for River Rch & Prof#=Trail Creek,Reach-1,7
Up Type=0
Dn Type=3
Dn Slope=0.0051

--- Trail Creek.g01 (geometry) ---

Geom Title=Existing Conditions
Program Version=4.10

River Reach=Trail Creek     ,Reach-1
Reach XY= 30
        2306929.        7085760.      2315373.33      7085858.02
      2315526.42        7084915.      2316068.36      7084760.55
      2316877.53      7085206.45      2318672.92      7083468.13
      2319835.74      7083250.87      2321188.79      7082399.48
      2321289.63        7081350.      2322923.42      7080754.42
      2322922.61        7080018.      2324681.29      7079404.16
      2325640.53       7078561.5      2327077.54      7078606.46
      2329830.45      7076713.53      2330777.56      7077006.96
        2331029.        7076060.      2331631.66      7076065.45
      2331939.42      7076558.95      2332671.09      7076412.91
      2332889.46      7076958.88      2334563.84      7077109.62
      2334934.85      7076712.06      2336313.85      7076660.36
      2338213.58      7077409.68      2340634.93      7076562.24
      2341281.55      7076655.02      2341198.14      7076239.58
      2341973.56      7076204.83        2343429.        7074460.

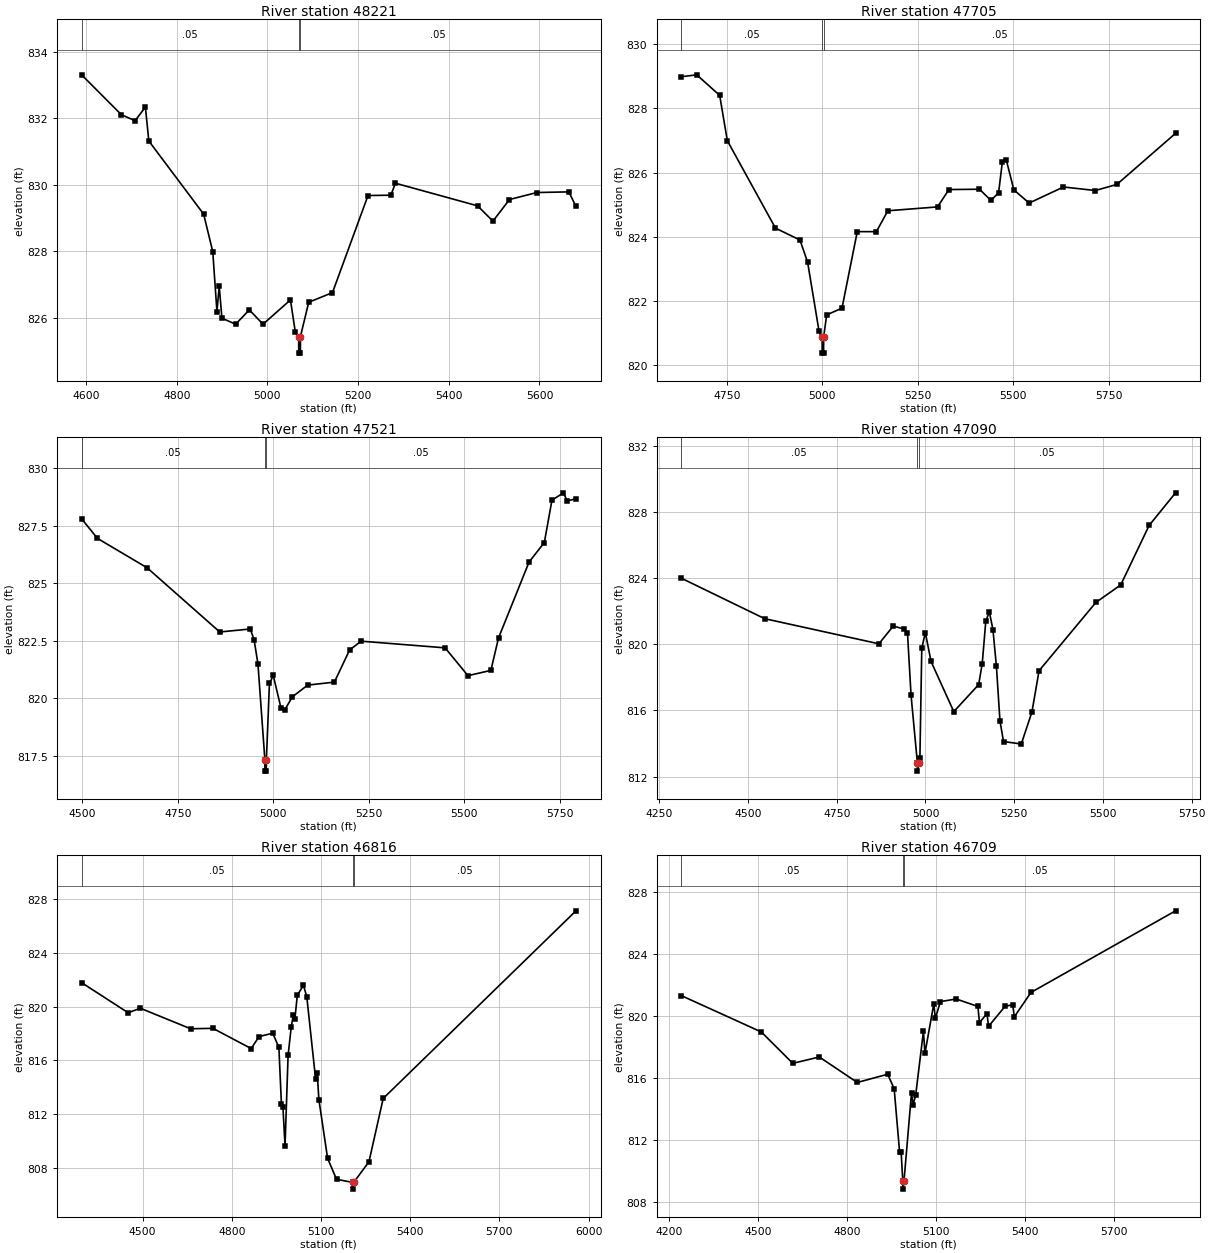
Type RM Length L Ch R = 1 ,48221   ,516,516,516
BEGIN DESCRIPTION:
Trail Creek 87.0
END DESCRIPTION:
XS GIS Cut Line= 3
       2307547.2      7086217.06       2307612.3      7085685.84
      2307674.74      7085134.35
#Sta/Elev= 30
  4590.3   833.3    4678   832.1  4708.2  831.92  4730.9  832.33  4738.5  831.31
  4859.4  829.11  4879.5  827.98  4888.7  826.18  4893.7  826.94  4899.7  825.98
  4929.9   825.8  4960.1  826.23  4990.3   825.8  5050.8  826.53  5061.6  825.56
  5068.9  825.43  5069.2  824.93  5072.7  824.93  5072.9  825.43  5091.1  826.46
  5143.5  826.75  5221.9  829.67  5272.3  829.68  5282.3  830.04  5463.5  829.36
  5497.4   828.9  5533.9  829.55  5594.3  829.76  5664.8  829.78  5680.5  829.34
#Mann= 3 ,-1 , 0
  4590.3     .05       0  5068.9     .04       0  5072.9     .05       0
Bank Sta=5068.9,5072.9
XS Rating Curve= 0 ,0
Exp/Cntr=0.3,0.1

Type RM Length L Ch R = 1 ,47705   ,184,184,184
BEGIN DESCRIPTION:
Trail Creek 85.2
END DESCRIPTION:
XS GIS Cut Line= 3
      2307971.68      7086180.68      2308000.33      7085605.11
      2308005.53      7084886.41
#Sta/Elev= 30
  4630.5  828.98  4671.2  829.04  4731.3   828.4  4751.3  826.99  4877.4  824.27
  4941.6   823.9  4961.6  823.21  4991.6  821.06  4999.6  820.88  4999.9  820.38
  5003.4  820.38  5003.6  820.88  5011.6  821.57  5051.7  821.78  5091.7  824.16
  5141.8  824.16  5171.8  824.81  5301.9  824.93  5331.9  825.47  5411.9  825.48
  5441.9  825.13  5461.9  825.37  5471.9  826.34  5481.9   826.4  5501.9  825.46
  5541.9  825.05  5631.9  825.55  5715.4  825.44  5771.9  825.63  5925.5  827.22
#Mann= 3 ,-1 , 0
  4630.5     .05       0  4999.6     .04       0  5003.6     .05       0
Bank Sta=4999.6,5003.6
XS Rating Curve= 0 ,0
Exp/Cntr=0.3,0.1

Type RM Length L Ch R = 1 ,47521   ,431,431,431
BEGIN DESCRIPTION:
Trail Creek 85.0
END DESCRIPTION:
XS GIS Cut Line= 3
      2308133.14      7086261.37      2308161.78      7085685.84
      2308166.99      7084967.11
#Sta/Elev= 30
  4497.8  827.81  4539.2  826.96  4669.4  825.68  4859.6  822.89  4939.7  823.02
  4949.7  822.54  4959.7   821.5  4977.8  817.34    4978  816.84  4981.5  816.84
  4981.8  817.34  4989.8  820.65  4999.8     821  5019.8   819.6  5029.8   819.5
  5049.9  820.07  5089.9  820.58  5159.9  820.71  5199.9  822.11  5229.9  822.49
  5449.9   822.2  5509.9  820.99  5569.9  821.22  5589.9  822.63  5669.9  825.93
  5709.9  826.78  5729.9  828.62  5759.9  828.94  5769.9  828.59  5792.8  828.68
#Mann= 3 ,-1 , 0
  4497.8     .05       0  4977.8    .033       0  4981.8     .05       0
Bank Sta=4977.8,4981.8
XS Rating Curve= 0 ,0
Exp/Cntr=0.3,0.1

Type RM Length L Ch R = 1 ,47090   ,274,274,274
BEGIN DESCRIPTION:
Trail Creek 84.0
END DESCRIPTION:
XS GIS Cut Line= 3
       2308479.5      7086443.61      2308557.62      7085743.13
      2308583.66      7085055.64
#Sta/Elev= 30
  4311.9     824    4547  821.55  4868.9  820.03  4909.2   821.1  4939.4  820.93
  4949.4  820.68  4959.5  816.91  4977.3  812.83  4977.6  812.33  4981.3  812.83
  4984.4  813.13  4989.7  819.76  4999.7  820.71  5015.8  818.96  5079.9  815.93
  5149.9  817.56    5160  818.83    5170  821.39    5180  821.96  5190.2  820.89
    5200  818.66    5210  815.36    5220  814.12    5270  813.97  5300.1  815.91
  5320.1   818.4  5480.2  822.53  5550.2  823.59  5630.3  827.19  5704.7  829.16
#Mann= 3 ,-1 , 0
  4311.9     .05       0  4977.3    .033       0  4981.3     .05       0
Bank Sta=4977.3,4981.3
XS Rating Curve= 0 ,0
Exp/Cntr=0.3,0.1

Type RM Length L Ch R = 1 ,46816   ,107,107,107
BEGIN DESCRIPTION:
Trail Creek 83.4
END DESCRIPTION:
XS GIS Cut Line= 3
      2308620.13      7086441.01      2308841.47      7085610.32
      2309113.99      7084855.05
#Sta/Elev= 30
  4295.2  821.77  4451.5  819.54  4492.9  819.87  4661.7  818.35  4736.8  818.38
  4865.4  816.88  4892.1  817.77  4937.9  818.02  4958.6  816.97  4967.1  812.79
  4972.3  812.51  4979.3  809.65  4989.6  816.38    5000  818.45  5007.2  819.38
  5012.4  819.09  5020.7  820.85  5041.4  821.57  5052.5  820.71  5082.3  814.59
  5087.5  815.07  5093.1   813.1  5122.4  808.74  5152.4  807.18  5206.4  806.95
  5206.6  806.45  5210.4  806.95  5261.5  808.48  5309.5  813.18  5957.8   827.1
#Mann= 3 ,-1 , 0
  4295.2     .05       0  5206.4    .033       0  5210.4     .05       0
Bank Sta=5206.4,5210.4
XS Rating Curve= 0 ,0
Exp/Cntr=0.3,0.1

Type RM Length L Ch R = 1 ,46709   ,82,82,82
BEGIN DESCRIPTION:
Trail Creek 83.2
END DESCRIPTION:
XS GIS Cut Line= 3
      2308713.87       7086493.1      2308935.22       7085662.4
      2309208.58       7084904.8
#Sta/Elev= 30
  4241.3  821.31    4511  818.97  4617.1  816.95  4706.4  817.36  4834.4  815.72
  4936.8  816.25  4958.6  815.32  4976.9  811.24  4982.1  811.25  4987.6  809.36
  4987.9  808.86  4991.6  809.36    5017  815.06  5022.2   814.3    5031  814.89
  5057.2  819.02  5062.3   817.6  5092.1  820.78  5097.3  819.84  5114.2  820.92
  5167.3  821.09  5240.6  820.61  5245.9  819.57  5271.2  820.15  5276.6  819.33
  5332.6  820.63    5358  820.71  5363.3  819.94  5419.3  821.51  5906.4  826.76
#Mann= 3 ,-1 , 0
  4241.3     .05       0  4987.6    .033       0  4991.6     .05       0
Bank Sta=4987.6,4991.6
XS Rating Curve= 0 ,0
Exp/Cntr=0.3,0.1

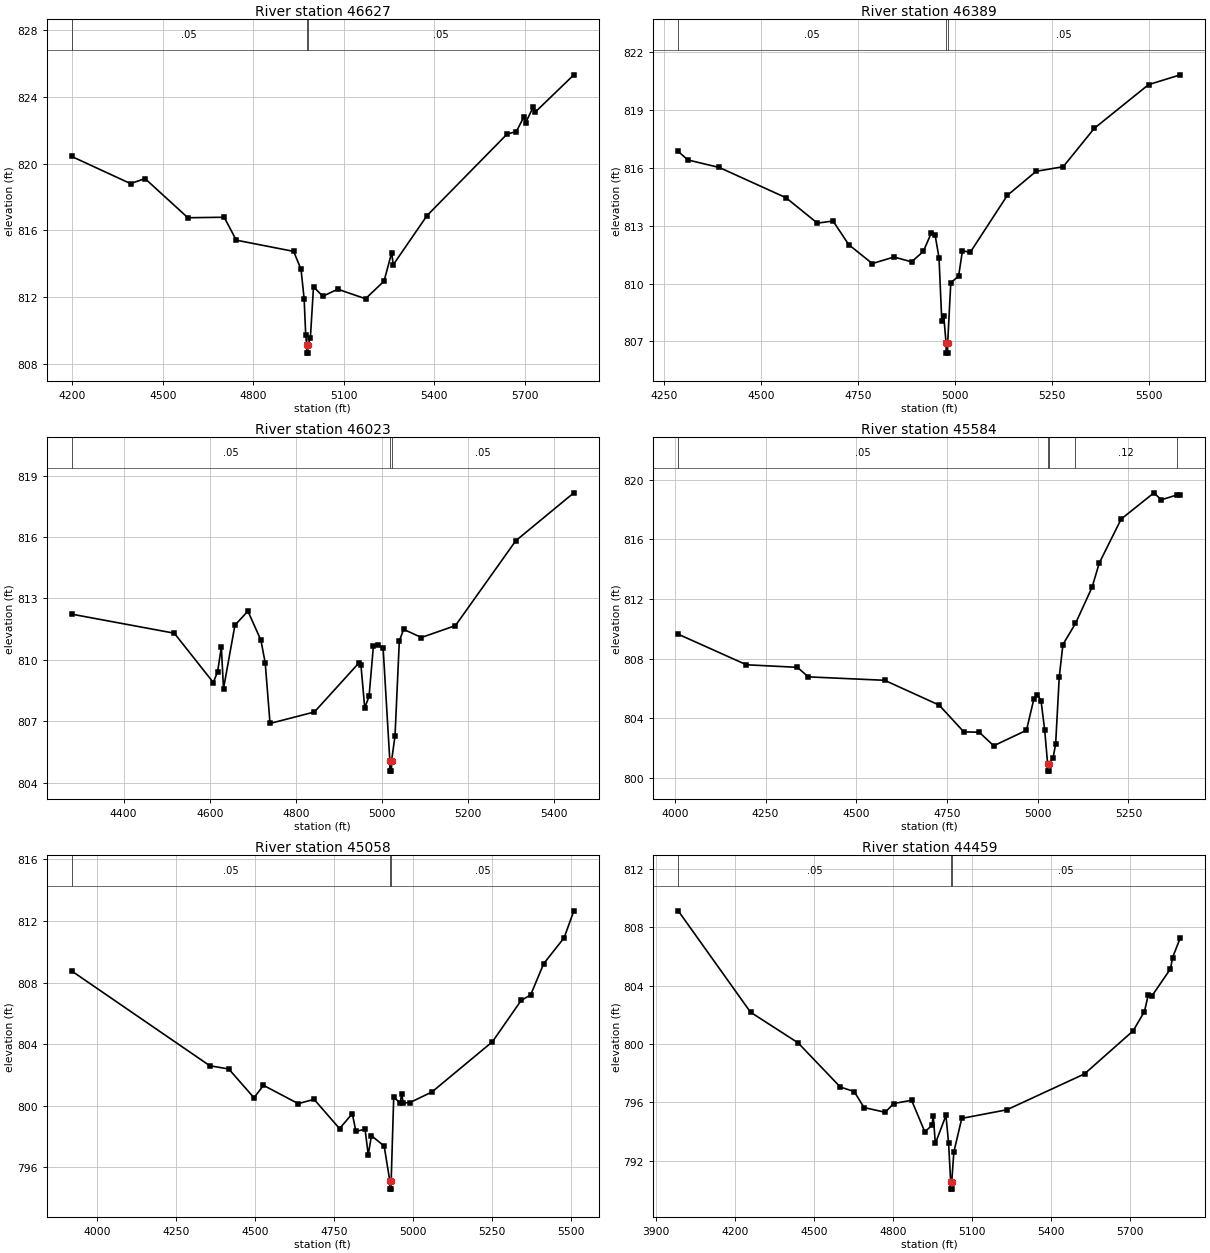
Type RM Length L Ch R = 1 ,46627   ,238,238,238
BEGIN DESCRIPTION:
Trail Creek 83.0
END DESCRIPTION:
XS GIS Cut Line= 3
      2308784.19      7086534.76      2309005.53      7085704.07
      2309278.97      7084946.26
#Sta/Elev= 30
  4198.2  820.42  4393.1   818.8  4441.1   819.1  4583.4  816.76  4703.7  816.79
  4743.8  815.42  4934.1  814.75  4958.6  813.68  4968.9  811.92  4974.2  809.74
  4977.4  809.17  4977.6  808.67  4981.1  808.67  4981.4  809.17  4989.6  809.57
    5000  812.63    5031  812.07  5080.5  812.49  5172.5  811.92  5233.9  812.97
  5259.2  814.67  5264.5  813.95  5376.6  816.89  5642.1  821.76  5672.8  821.91
  5698.1   822.8  5703.5  822.44  5728.8  823.37  5734.1  823.05  5863.5   825.3
#Mann= 3 ,-1 , 0
  4198.2     .05       0  4977.4    .033       0  4981.4     .05       0
Bank Sta=4977.4,4981.4
XS Rating Curve= 0 ,0
Exp/Cntr=0.3,0.1

Type RM Length L Ch R = 1 ,46389   ,366,366,366
BEGIN DESCRIPTION:
Trail Creek 82.0
END DESCRIPTION:
XS GIS Cut Line= 3
       2309114.9      7086464.53        2309229.        7085760.
      2309250.33        7085178.
#Sta/Elev= 30
  4285.9  816.86  4310.8  816.42  4391.8  816.03    4564  814.46  4645.1  813.14
  4685.6  813.25  4726.1  812.02  4786.9  811.04  4842.9  811.38  4888.2  811.13
  4918.6  811.67  4938.8  812.61    4949  812.52  4959.1  811.34  4966.2  808.08
  4971.3  808.31  4977.4  806.89  4977.6  806.39  4981.1  806.39  4981.4  806.89
  4989.5  810.05  5009.6  810.38  5019.6  811.71  5039.6  811.62  5135.4  814.58
  5209.8  815.83  5279.8  816.07  5359.9  818.06  5499.9  820.33    5582  820.84
#Mann= 3 ,-1 , 0
  4285.9     .05       0  4977.4    .033       0  4981.4     .05       0
Bank Sta=4977.4,4981.4
XS Rating Curve= 0 ,0
Exp/Cntr=0.3,0.1

Type RM Length L Ch R = 1 ,46023   ,439,439,439
BEGIN DESCRIPTION:
Trail Creek 81.0
END DESCRIPTION:
XS GIS Cut Line= 3
      2309510.74      7086526.98        2309579.        7085810.
      2309604.49      7085365.55
#Sta/Elev= 30
  4279.8  812.23  4517.8   811.3  4608.3  808.89  4618.3  809.42    4627  810.62
    4632  808.59  4658.5  811.69  4688.6  812.38  4718.8  810.96  4728.8  809.85
    4740  806.89    4843  807.45    4946  809.84    4951  809.75  4959.8  807.65
  4969.9  808.22  4979.9  810.67    4990  810.74  5002.5  810.57  5018.1  805.06
  5018.3  804.56  5021.8  804.56  5022.1  805.06  5030.1  806.28  5040.1  810.92
  5050.1  811.49  5091.3  811.09  5170.3  811.67  5310.5  815.82  5445.2  818.16
#Mann= 3 ,-1 , 0
  4279.8     .05       0  5018.1    .033       0  5022.1     .05       0
Bank Sta=5018.1,5022.1
XS Rating Curve= 0 ,0
Exp/Cntr=0.3,0.1

Type RM Length L Ch R = 1 ,45584   ,526,526,526
BEGIN DESCRIPTION:
Trail Creek 80.0
END DESCRIPTION:
XS GIS Cut Line= 3
      2310078.45      7086797.86      2310036.78      7086042.61
       2309984.7      7085417.57
#Sta/Elev= 30
  4009.3  809.64  4197.4  807.59  4337.7  807.42  4367.7  806.78    4578  806.55
  4728.2  804.89  4796.3  803.09  4838.6  803.07  4878.7  802.16    4969   803.2
  4989.1  805.28  4999.1  805.59  5009.1  805.18  5019.2  803.21  5027.2  800.96
  5027.5  800.46    5031  800.46  5031.2  800.96  5042.2  801.35  5049.3  802.27
  5059.3  806.77  5069.4  808.95    5104  810.36  5149.6  812.78  5169.7  814.42
  5229.9  817.36  5320.2  819.12  5340.3  818.65  5382.6  818.97  5392.9  818.95
#Mann= 5 ,-1 , 0
  4009.3     .05       0  5027.2    .033       0  5031.2     .05       0
    5104     .12       0  5382.6     .05       0
Bank Sta=5027.2,5031.2
XS Rating Curve= 0 ,0
Exp/Cntr=0.3,0.1

Type RM Length L Ch R = 1 ,45058   ,599,599,599
BEGIN DESCRIPTION:
Trail Creek 79.0
END DESCRIPTION:
XS GIS Cut Line= 3
       2310484.7      7086787.38      2310495.12      7086047.82
      2310380.59      7085204.49
#Sta/Elev= 30
  3919.2  808.75  4356.6   802.6  4416.6  802.39  4496.6  800.52  4526.6  801.33
  4636.6  800.14  4686.9  800.42  4767.6  798.52    4808  799.49  4819.4  798.34
  4848.4  798.48  4858.5  796.82  4868.6  798.06  4908.9  797.39  4927.1  795.09
  4927.4  794.59  4930.9  794.59  4931.1  795.09  4939.2  800.56  4959.4  800.18
  4964.4  800.75  4969.5  800.19  4989.7   800.2  5060.3   800.9    5252  804.16
  5342.9  806.84  5373.1   807.2  5414.4  809.23  5479.1  810.91  5509.9  812.66
#Mann= 3 ,-1 , 0
  3919.2     .05       0  4927.1    .033       0  4931.1     .05       0
Bank Sta=4927.1,4931.1
XS Rating Curve= 0 ,0
Exp/Cntr=0.3,0.1

Type RM Length L Ch R = 1 ,44459   ,562,562,562
BEGIN DESCRIPTION:
Trail Creek 78.0
END DESCRIPTION:
XS GIS Cut Line= 3
      2311078.45      7086823.83      2310995.12      7085579.07
      2310489.94      7085157.22
#Sta/Elev= 30
  3983.9  809.13  4258.3  802.18  4438.7  800.08  4599.1  797.05  4651.8  796.74
  4689.3  795.64  4769.5  795.32  4801.8  795.92  4869.7  796.14  4919.8  793.98
  4946.8  794.42  4951.8  795.06  4959.9  793.18    5000   795.1    5010  793.22
    5018  790.55  5018.3  790.05  5021.8  790.05    5022  790.55  5030.1   792.6
  5060.1   794.9  5231.4  795.49    5526  797.95  5710.4   800.9  5753.3  802.22
  5767.7  803.34    5782   803.3  5852.3  805.15  5860.1  805.92  5889.6  807.28
#Mann= 3 ,-1 , 0
  3983.9     .05       0    5018    .033       0    5022     .05       0
Bank Sta=5018,5022
XS Rating Curve= 0 ,0
Exp/Cntr=0.3,0.1

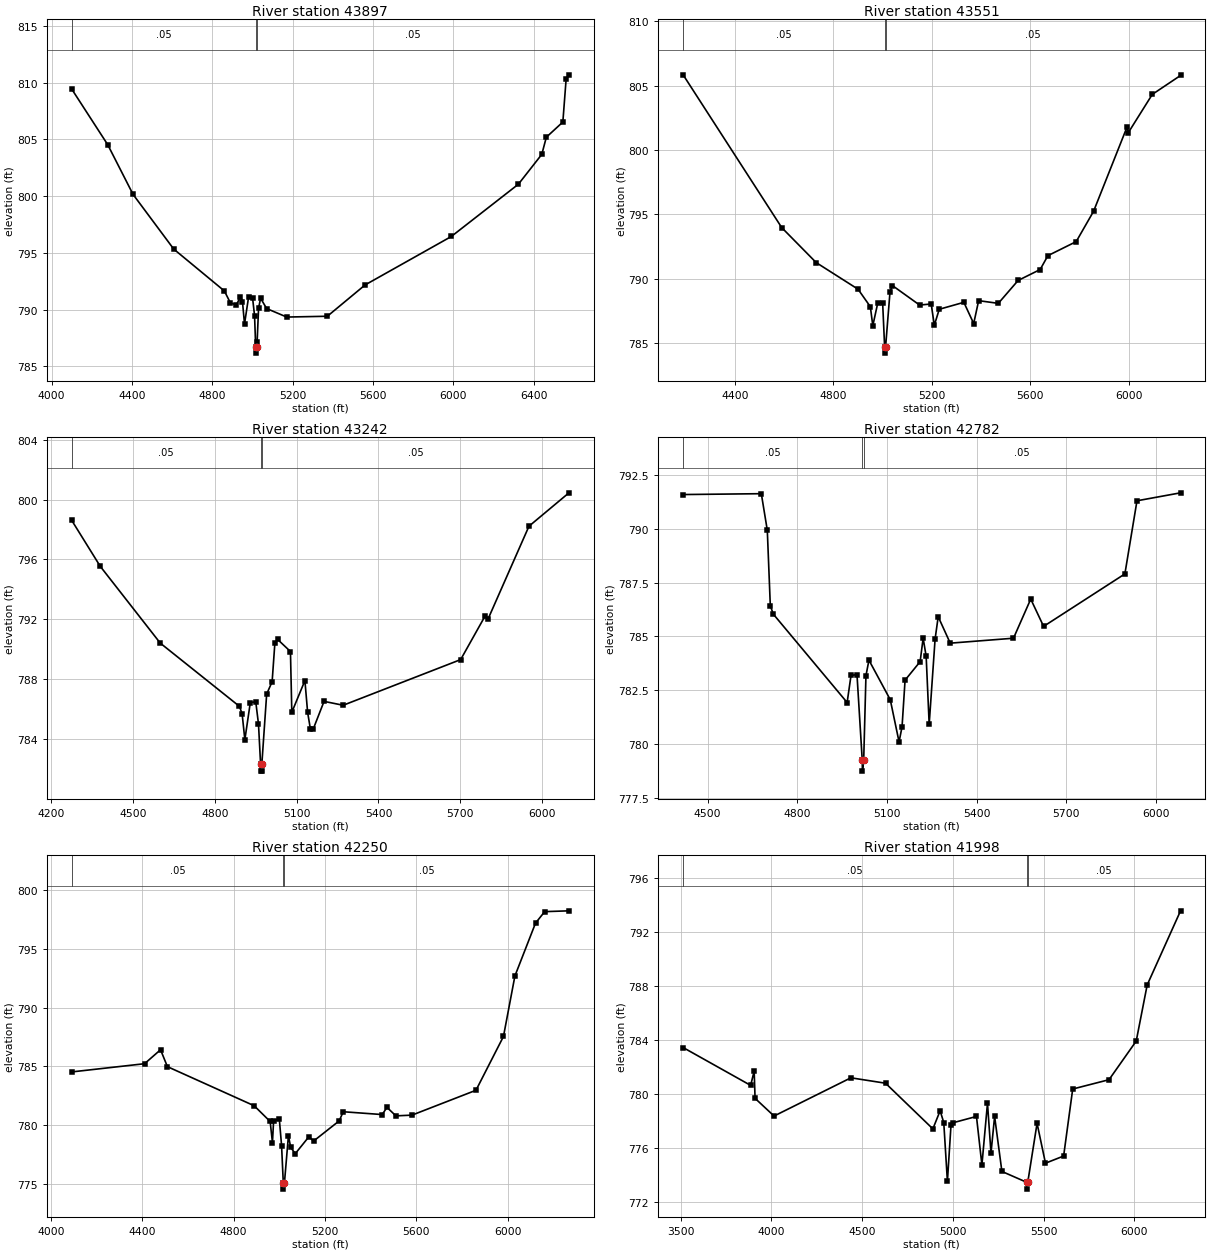
Type RM Length L Ch R = 1 ,43897   ,346,346,346
BEGIN DESCRIPTION:
Trail Creek 77.0
END DESCRIPTION:
XS GIS Cut Line= 3
        2311529.      7086710.03      2311588.87      7085485.32
      2310478.99        7084910.
#Sta/Elev= 30
  4098.9  809.46  4279.1  804.53  4405.2  800.15  4607.7  795.33  4859.8  791.64
  4889.9  790.58  4919.9  790.41  4939.9  791.15  4949.9  790.71    4960  788.72
    4980  791.07    5000  791.05    5010  789.47  5015.8  786.66    5016  786.16
  5019.8  786.66  5022.8  787.14    5030  790.11  5040.1     791  5070.1  790.09
  5170.2  789.34  5372.4  789.41  5560.3  792.17  5989.5  796.44  6323.5  801.05
    6440  803.68  6462.6  805.19  6544.8  806.53  6561.3  810.35  6575.2  810.69
#Mann= 3 ,-1 , 0
  4098.9     .05       0  5015.8    .033       0  5019.8     .05       0
Bank Sta=5015.8,5019.8
XS Rating Curve= 0 ,0
Exp/Cntr=0.3,0.1

Type RM Length L Ch R = 1 ,43551   ,309,309,309
BEGIN DESCRIPTION:
Trail Creek 76.0
END DESCRIPTION:
XS GIS Cut Line= 3
      2311896.16       7086620.7      2311932.62      7085297.82
      2311833.83      7084606.32
#Sta/Elev= 30
    4189  805.84  4589.8  793.96  4729.9  791.24    4900  789.17    4950  787.81
    4960  786.33    4980  788.09    5000  788.12    5008   784.7  5008.3   784.2
    5012   784.7    5030  788.98    5040  789.45  5150.1  787.94  5197.3  788.02
  5210.1  786.37  5230.1  787.61  5330.1  788.15  5370.1   786.5  5390.2  788.28
  5470.2  788.07  5550.6  789.85  5640.2   790.7  5671.8  791.78  5786.7  792.87
  5857.4  795.23  5993.8   801.8  5998.8  801.35  6096.1  804.32  6210.9  805.79
#Mann= 3 ,-1 , 0
    4189     .05       0    5008    .033       0    5012     .05       0
Bank Sta=5008,5012
XS Rating Curve= 0 ,0
Exp/Cntr=0.3,0.1

Type RM Length L Ch R = 1 ,43242   ,460,460,460
BEGIN DESCRIPTION:
Trail Creek 75.0
END DESCRIPTION:
XS GIS Cut Line= 3
      2312193.03      7086485.32      2312208.66      7085756.15
      2312141.03      7084663.68
#Sta/Elev= 30
  4274.5  798.63  4379.8  795.54  4599.9  790.41    4890  786.19    4900  785.69
    4910  783.96    4930  786.44    4950  786.49    4960  785.01  4967.6  782.36
  4968.1  781.86  4971.8  781.86  4972.4  782.36    4990  787.01    5010  787.83
    5020  790.39    5030  790.66  5077.2  789.85  5082.2  785.79  5130.2  787.91
  5140.2  785.78  5150.3  784.68  5160.3  784.65  5200.4  786.52  5270.5  786.26
  5701.3  789.31  5791.5  792.24  5801.5  792.01  5951.8  798.22  6098.4  800.45
#Mann= 3 ,-1 , 0
  4274.5     .05       0  4967.6    .033       0  4972.4     .05       0
Bank Sta=4967.6,4972.4
XS Rating Curve= 0 ,0
Exp/Cntr=0.3,0.1

Type RM Length L Ch R = 1 ,42782   ,532,532,532
BEGIN DESCRIPTION:
Trail Creek 74.0
END DESCRIPTION:
XS GIS Cut Line= 3
       2312672.2      7086391.59      2312651.37      7085761.36
      2312521.16      7084735.36
#Sta/Elev= 30
  4418.1   791.6  4679.8  791.64  4699.8  789.94  4709.9  786.43  4719.9  786.04
    4967  781.93    4980  783.19    5000  783.23  5017.6  779.24  5018.2  778.74
  5022.4  779.24    5030  783.18    5040   783.9  5111.4  782.06  5140.8   780.1
  5150.8   780.8  5160.9  782.97  5211.3  783.83  5221.4  784.92  5231.5  784.08
  5241.6  780.92  5261.4  784.88  5271.8  785.92  5312.1  784.69  5523.8  784.92
  5581.5  786.74  5624.6  785.47  5896.6  787.91  5937.1  791.31  6082.9  791.68
#Mann= 3 ,-1 , 0
  4418.1     .05       0  5017.6    .033       0  5022.4     .05       0
Bank Sta=5017.6,5022.4
XS Rating Curve= 0 ,0
Exp/Cntr=0.3,0.1

Type RM Length L Ch R = 1 ,42250   ,252,252,252
BEGIN DESCRIPTION:
Trail Creek 73.0
END DESCRIPTION:
XS GIS Cut Line= 3
       2313172.2      7086719.74      2313187.83      7085547.82
       2313120.2      7084543.82
#Sta/Elev= 30
  4090.6  784.53  4410.4  785.23  4480.4  786.42  4510.4  784.98  4890.4  781.65
  4960.4  780.31  4970.4  778.52  4975.5  780.35  5000.4  780.55  5010.4  778.26
    5018  775.05  5018.6  774.55  5022.8  775.05  5040.4   779.1  5050.4   778.1
  5070.4  777.57  5130.4  779.02  5150.4  778.64  5262.6  780.36  5280.5  781.14
  5450.9   780.9  5472.1  781.51    5511  780.79  5581.2  780.85  5861.8  782.97
  5982.1  787.55  6032.2   792.7  6122.4   797.2  6162.5  798.18  6268.9  798.25
#Mann= 3 ,-1 , 0
  4090.6     .05       0    5018    .033       0  5022.8     .05       0
Bank Sta=5018,5022.8
XS Rating Curve= 0 ,0
Exp/Cntr=0.3,0.1

Type RM Length L Ch R = 1 ,41998   ,629,629,629
BEGIN DESCRIPTION:
Trail Creek 72.0
END DESCRIPTION:
XS GIS Cut Line= 3
      2313307.62      7087240.54      2313427.41      7085943.65
      2313375.33       7084506.2
#Sta/Elev= 30
  3513.8  783.43  3885.9  780.63  3905.2  781.69  3910.2  779.67  4014.8  778.36
  4438.3  781.19  4629.1  780.79  4889.9  777.41  4929.9  778.75  4949.9  777.88
    4970  773.52    4990  777.73    5000  777.86  5130.1  778.33  5160.1  774.74
  5190.8  779.31  5210.1  775.62  5230.1  778.33  5270.2  774.26  5407.8  773.45
  5408.4  772.95  5412.7  773.45    5464  777.82  5510.3  774.87  5610.4   775.4
  5660.4  780.36  5860.5  781.05  6010.4  783.91  6070.7  788.06  6254.6  793.55
#Mann= 3 ,-1 , 0
  3513.8     .05       0  5407.8    .033       0  5412.7     .05       0
Bank Sta=5407.8,5412.7
XS Rating Curve= 0 ,0
Exp/Cntr=0.3,0.1

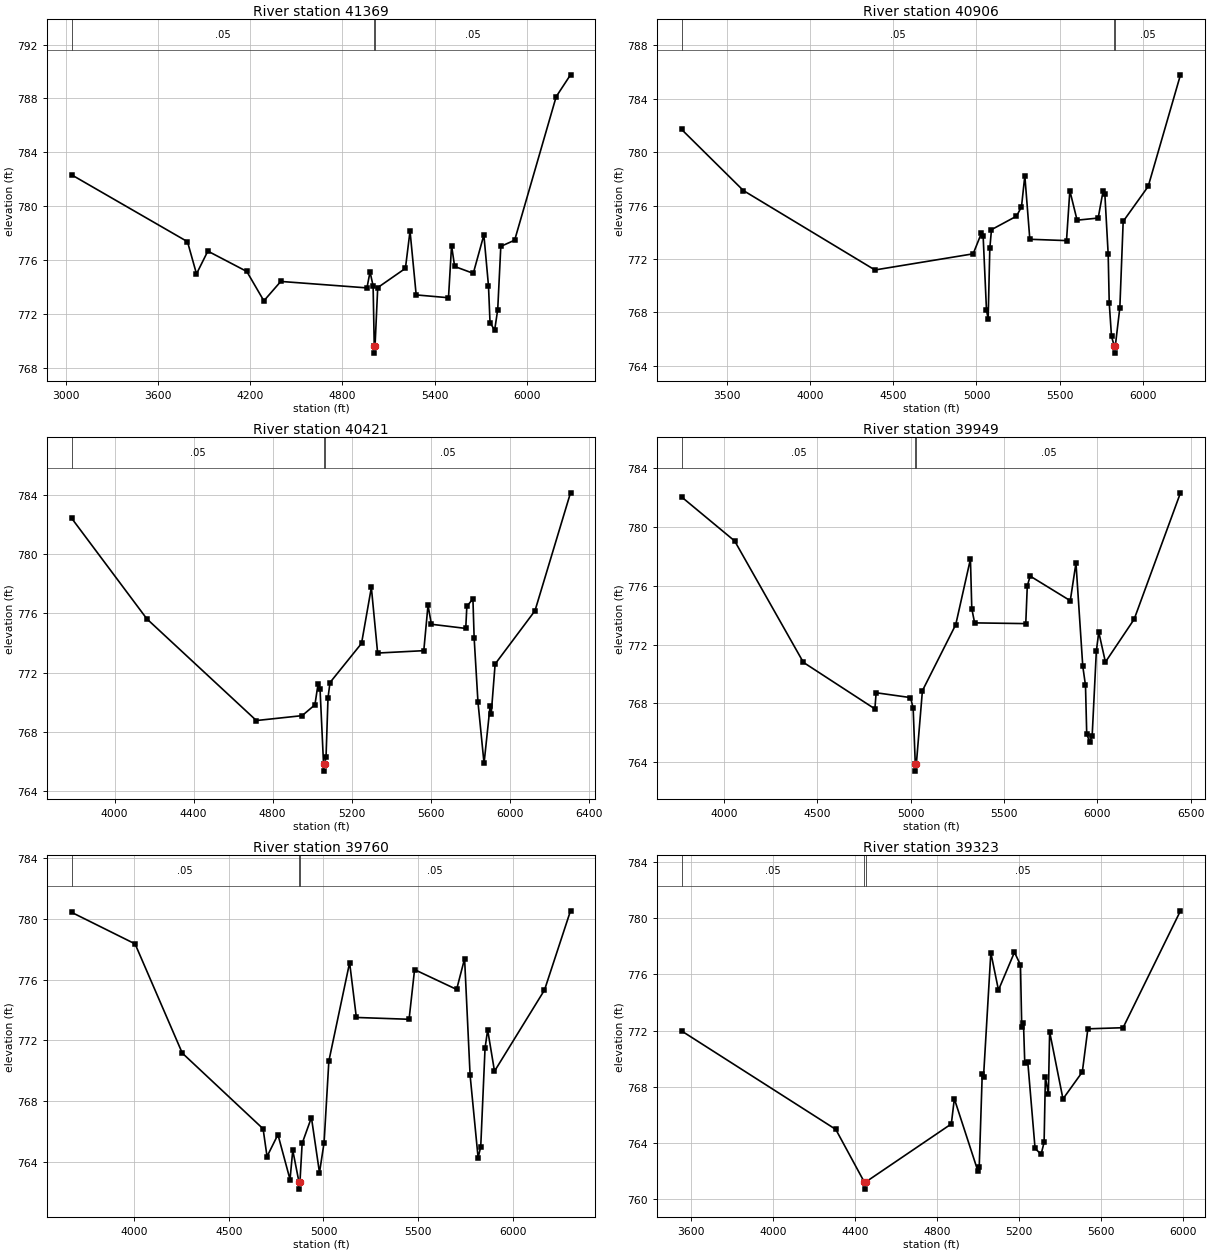
Type RM Length L Ch R = 1 ,41369   ,463,463,463
BEGIN DESCRIPTION:
Trail Creek 71.0
END DESCRIPTION:
XS GIS Cut Line= 3
      2313484.69      7087615.54      2314057.62      7086631.15
      2313995.12      7084526.96
#Sta/Elev= 30
  3039.5  782.33  3792.9  777.37  3851.6  774.98  3925.3  776.67  4178.5  775.16
  4289.7  772.98  4399.7  774.42    4960  773.94    4980  775.13    5000  774.09
  5007.5   769.6  5008.1   769.1  5012.4   769.6    5030  773.96  5210.1  775.39
  5240.1  778.16  5280.1  773.42  5490.2  773.21  5510.2  777.08  5530.2  775.53
  5651.4  775.02  5720.3  777.87  5750.3  774.09  5760.3  771.37  5790.3   770.8
  5810.3  772.33  5830.4  777.02  5920.4  777.48  6190.5  788.13  6283.6  789.75
#Mann= 3 ,-1 , 0
  3039.5     .05       0  5007.5    .033       0  5012.4     .05       0
Bank Sta=5007.5,5012.4
XS Rating Curve= 0 ,0
Exp/Cntr=0.3,0.1

Type RM Length L Ch R = 1 ,40906   ,485,485,485
BEGIN DESCRIPTION:
Trail Creek 70.0
END DESCRIPTION:
XS GIS Cut Line= 3
      2314500.33       7087631.2      2314479.49      7085756.15
       2314422.2      7084636.38
#Sta/Elev= 30
  3228.7   781.7  3599.9  777.12    4390  771.17    4980  772.38    5030  773.94
    5040  773.68    5060  768.15    5070  767.52    5080  772.79    5090  774.19
  5240.2   775.2  5270.2   775.9  5290.3  778.23  5320.3  773.47  5540.6  773.37
  5560.6  777.11  5604.2   774.9  5730.8  775.06  5760.9  777.12  5770.9  776.87
  5790.9  772.35  5797.2   768.7  5810.9  766.19  5828.5  765.44  5829.1  764.94
  5833.4  765.44    5861  768.35    5881  774.81  6031.2  777.43  6225.1  785.79
#Mann= 3 ,-1 , 0
  3228.7     .05       0  5828.5    .035       0  5833.4     .05       0
Bank Sta=5828.5,5833.4
XS Rating Curve= 0 ,0
Exp/Cntr=0.3,0.1

Type RM Length L Ch R = 1 ,40421   ,472,472,472
BEGIN DESCRIPTION:
Trail Creek 69.0
END DESCRIPTION:
XS GIS Cut Line= 3
       2315109.7      7087068.65      2314948.24      7085714.49
       2314557.6       7084620.7
#Sta/Elev= 30
  3782.8  782.41  4163.9  775.62    4718  768.77  4949.7   769.1  5014.3  769.83
  5030.2  771.23  5040.3  770.89  5057.9  765.86  5058.6  765.36  5062.9  765.86
  5070.5  766.28  5080.6   770.3  5090.6  771.33  5250.3  773.97    5300  777.74
  5331.8  773.32  5565.4  773.48  5586.7  776.54  5603.9  775.26  5777.8  774.98
  5783.3  776.47  5814.1  776.97  5820.3  774.33  5839.6  770.02  5870.4  765.88
  5901.2  769.77  5906.5  769.19  5926.5  772.58  6128.2  776.17    6308  784.12
#Mann= 3 ,-1 , 0
  3782.8     .05       0  5057.9    .035       0  5062.9     .05       0
Bank Sta=5057.9,5062.9
XS Rating Curve= 0 ,0
Exp/Cntr=0.3,0.1

Type RM Length L Ch R = 1 ,39949   ,189,189,189
BEGIN DESCRIPTION:
Trail Creek 68.0
END DESCRIPTION:
XS GIS Cut Line= 3
      2316234.71      7086735.33      2315260.74      7085636.36
      2314614.92      7084620.75
#Sta/Elev= 30
  3772.7  782.06    4057  779.06    4425  770.79    4808  767.62  4814.7  768.72
  4998.7  768.39  5012.9  767.69  5024.3  763.88  5025.2  763.38  5030.1  763.88
  5062.6  768.86  5241.1  773.36  5319.8  777.83    5327  774.45  5342.2  773.48
  5616.1  773.43  5624.2  775.98  5639.4  776.67  5854.5  774.99    5885  777.56
  5921.4  770.53    5936  769.22  5942.6  765.92  5957.8  765.38  5971.6  765.75
  5994.2  771.57  6007.1  772.85  6042.7  770.81  6196.7  773.73  6444.7  782.34
#Mann= 3 ,-1 , 0
  3772.7     .05       0  5024.3    .033       0  5030.1     .05       0
Bank Sta=5024.3,5030.1
XS Rating Curve= 0 ,0
Exp/Cntr=0.3,0.1

Type RM Length L Ch R = 1 ,39760   ,437,437,437
BEGIN DESCRIPTION:
Trail Creek 67.8
END DESCRIPTION:
XS GIS Cut Line= 4
      2316354.49      7086625.95      2315583.66      7085683.24
      2315411.78      7085620.74      2314662.89      7084643.02
#Sta/Elev= 30
  3671.2  780.41    4006  778.34  4255.1  771.17  4681.5   766.2  4702.3  764.38
  4759.8  765.82  4823.6  762.87    4838  764.79  4870.3  762.74  4871.2  762.24
  4876.1  762.74  4887.5  765.24  4936.5  766.94    4979  763.32  5003.2  765.29
  5028.5  770.65    5138  777.11  5173.5  773.51  5451.7  773.39  5480.7  776.65
  5702.6  775.35  5744.6  777.37  5773.6  769.73  5815.9   764.3  5829.8  765.03
  5852.5  771.49  5866.3   772.7  5902.4  769.98  6166.2  775.31  6303.4  780.51
#Mann= 3 ,-1 , 0
  3671.2     .05       0  4870.3    .033       0  4876.1     .05       0
Bank Sta=4870.3,4876.1
XS Rating Curve= 0 ,0
Exp/Cntr=0.3,0.1

Type RM Length L Ch R = 1 ,39323   ,839,839,839
BEGIN DESCRIPTION:
Trail Creek 67.5
END DESCRIPTION:
XS GIS Cut Line= 3
      2316505.52      7086214.47      2315823.24      7085459.28
      2314683.31      7084626.45
#Sta/Elev= 30
  3555.9  771.98  4306.9  764.97  4445.9  761.22  4446.9  760.72  4451.9  761.22
  4869.5  765.36  4884.2  767.15  4999.2  761.99  5005.4  762.33  5020.1  768.94
  5026.3  768.71  5061.9  777.55  5099.1  774.89  5176.9  777.58  5206.2  776.68
  5212.4  772.29  5220.9  772.54  5227.1  769.72  5241.7  769.79  5277.3  763.62
  5306.6   763.2  5321.3  764.05  5327.5   768.7  5342.1  767.48  5348.3  771.92
  5413.2  767.14  5507.4  769.06  5534.4  772.13  5705.9  772.21  5985.4  780.53
#Mann= 3 ,-1 , 0
  3555.9     .05       0  4445.9    .033       0  4451.9     .05       0
Bank Sta=4445.9,4451.9
XS Rating Curve= 0 ,0
Exp/Cntr=0.3,0.1

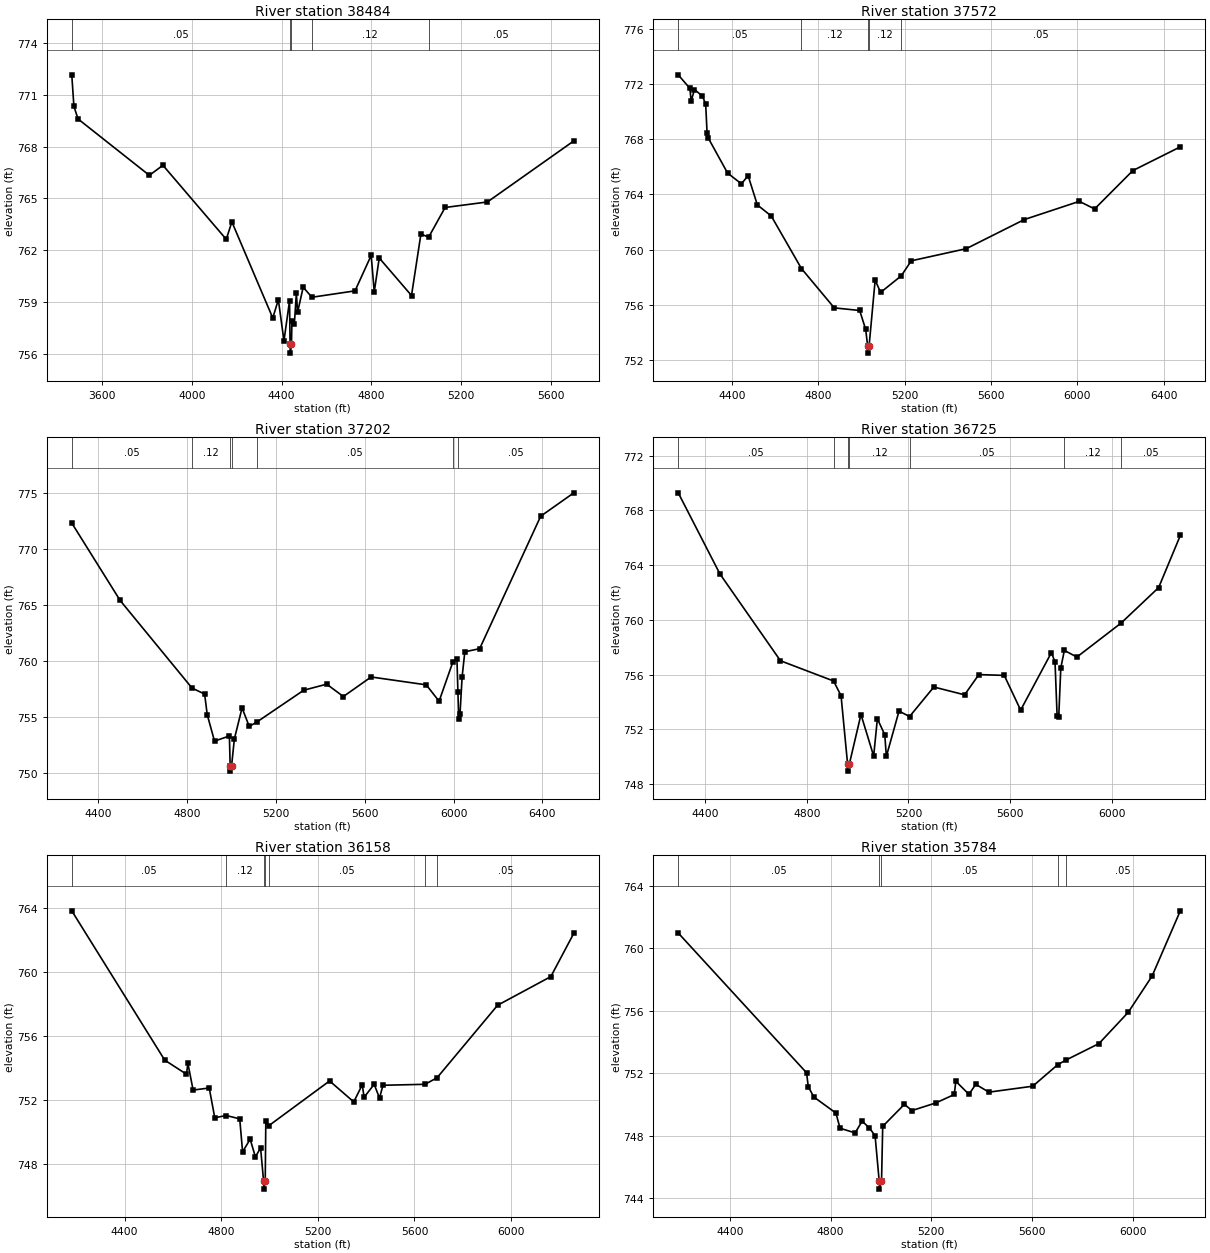
Type RM Length L Ch R = 1 ,38484   ,912,912,912
BEGIN DESCRIPTION:
Trail Creek 67.0
END DESCRIPTION:
XS GIS Cut Line= 3
       2316604.5      7086198.87      2316208.66      7085136.36
      2315588.91      7084224.97
#Sta/Elev= 30
  3465.6  772.15  3475.1  770.33  3493.4   769.6    3811  766.34  3871.6  766.92
  4153.6  762.64  4178.6  763.65  4360.8  758.09  4385.6  759.15  4410.6  756.77
  4435.5  759.09  4437.8  756.56  4438.8  756.06    4444  756.56  4446.2  757.94
  4456.8  757.74  4465.9  759.52  4471.2  758.42  4496.2  759.87  4535.1  759.29
  4727.1  759.66    4799  761.71  4812.7   759.6  4834.9  761.56  4978.6  759.39
  5020.6  762.95  5054.8  762.76  5128.3  764.48  5316.8   764.8  5701.6  768.33
#Mann= 5 ,-1 , 0
  3465.6     .05       0  4437.8     .07       0    4444     .05       0
  4535.1     .12       0  5054.8     .05       0
Bank Sta=4437.8,4444
XS Rating Curve= 0 ,0
Exp/Cntr=0.3,0.1

Type RM Length L Ch R = 1 ,37572   ,370,370,370
BEGIN DESCRIPTION:
Trail Creek 65.0
END DESCRIPTION:
XS GIS Cut Line= 4
      2317073.25      7085948.88      2316693.03      7085318.65
      2316637.56      7085134.25      2315698.25      7084099.91
#Sta/Elev= 30
  4150.7  772.67  4204.6  771.69  4210.5  770.77    4226   771.6  4262.9  771.13
  4277.9  770.54  4284.2  768.47  4290.1  768.08  4379.3  765.55  4443.4  764.77
  4474.4  765.36  4517.2  763.24  4581.5  762.44  4721.4  758.63  4873.5  755.78
  4991.2  755.59    5019  754.22  5028.3     753  5029.4   752.5  5034.7     753
  5062.9  757.79  5088.2   756.9  5183.7   758.1  5230.1  759.19  5484.9  760.07
  5753.8  762.18  6008.6   763.5  6079.5  762.95  6256.6  765.73  6476.5  767.45
#Mann= 5 ,-1 , 0
  4150.7     .05       0  4721.4     .12       0  5028.3     .07       0
  5034.7     .12       0  5183.7     .05       0
Bank Sta=5028.3,5034.7
XS Rating Curve= 0 ,0
Exp/Cntr=0.3,0.1

Type RM Length L Ch R = 1 ,37202   ,477,477,477
BEGIN DESCRIPTION:
Trail Creek 64.0
END DESCRIPTION:
XS GIS Cut Line= 3
       2317312.8      7085756.11      2316713.87      7084547.82
      2316230.49      7083773.38
#Sta/Elev= 30
    4280  772.29  4497.9   765.4  4821.8   757.6  4878.4  757.07  4890.2  755.23
    4923  752.88    4990  753.34  4993.4  750.71  4994.4  750.21    5000  750.71
  5012.3  753.07  5047.1  755.84  5079.3  754.19  5112.1  754.56  5324.8  757.41
  5428.2  757.95  5503.4  756.85  5628.4  758.59  5876.7  757.89  5934.5  756.43
    5997  759.95    6015  760.16  6019.4  757.21  6022.9  754.87  6028.8  755.33
  6038.3  758.61  6050.4  760.83  6117.3  761.11  6392.2   772.9  6541.5  774.98
#Mann= 7 ,-1 , 0
    4280     .05       0  4821.8     .12       0  4993.4     .07       0
    5000     .12       0  5112.1     .05       0    5997     .12       0
  6019.4     .05       0
Bank Sta=4993.4,5000
XS Rating Curve= 0 ,0
Exp/Cntr=0.3,0.1

Type RM Length L Ch R = 1 ,36725   ,567,567,567
BEGIN DESCRIPTION:
Trail Creek 63.0
END DESCRIPTION:
XS GIS Cut Line= 3
      2317713.85      7085401.97        2317329.        7084810.
      2316564.32       7083794.6
#Sta/Elev= 30
  4293.7  769.29  4457.8  763.36  4696.3  757.01  4905.5  755.53  4934.9  754.45
  4960.7  749.44  4961.7  748.94  4967.3  749.44  5013.3  753.08  5063.3  750.04
  5077.9  752.77    5107   751.6  5113.3  750.02  5163.2  753.33  5204.6  752.93
  5300.2  755.09  5421.4  754.52  5477.6     756  5577.6  755.94  5642.1   753.4
  5763.4  757.61  5777.5  756.91  5785.8  752.94    5792  752.87  5800.3  756.49
  5814.3  757.77  5863.5  757.28  6037.9  759.77  6185.5  762.36  6270.9  766.17
#Mann= 7 ,-1 , 0
  4293.7     .05       0  4905.5     .12       0  4960.7     .07       0
  4967.3     .12       0  5204.6     .05       0  5814.3     .12       0
  6037.9     .05       0
Bank Sta=4960.7,4967.3
XS Rating Curve= 0 ,0
Exp/Cntr=0.3,0.1

Type RM Length L Ch R = 1 ,36158   ,374,374,374
BEGIN DESCRIPTION:
Trail Creek 62.0
END DESCRIPTION:
XS GIS Cut Line= 3
      2318021.15      7085084.27      2317599.28      7084344.69
       2316807.6      7083407.18
#Sta/Elev= 30
  4181.2  763.85    4566  754.52  4656.1  753.64  4661.9  754.32  4683.5  752.65
  4750.2  752.78  4773.2  750.92    4821  751.06  4876.5  750.85  4888.4  748.79
  4919.7  749.58  4941.3  748.48  4962.9  749.03  4975.3  746.96  4976.4  746.46
  4982.1  746.96  4984.5  750.72  4996.6  750.42  5248.5  753.22  5348.6  751.91
  5383.7  752.98  5391.5   752.2  5433.1  753.01  5455.2  752.15  5469.5  752.95
  5643.7  753.01  5693.5  753.42  5944.1  757.95  6164.4  759.74  6259.7  762.45
#Mann= 7 ,-1 , 0
  4181.2     .05       0    4821     .12       0  4975.3    .035       0
  4982.1     .12       0  4996.6     .05       0  5643.7     .12       0
  5693.5     .05       0
Bank Sta=4975.3,4982.1
XS Rating Curve= 0 ,0
Exp/Cntr=0.3,0.1

Type RM Length L Ch R = 1 ,35784   ,470,470,470
BEGIN DESCRIPTION:
Trail Creek 61.0
END DESCRIPTION:
XS GIS Cut Line= 3
      2318307.59      7084969.65        2317929.        7084260.
      2317307.62      7083245.74
#Sta/Elev= 30
  4195.1  760.99  4704.7  752.04  4711.5  751.15  4733.5  750.49  4821.3  749.46
  4837.6  748.49  4897.4  748.19  4925.4  748.94  4954.1  748.51  4976.8  748.01
  4993.2  745.09  4994.3  744.59    5000  745.09  5002.4  745.09  5007.1  748.61
  5093.2  750.02  5123.2  749.62    5218  750.11  5291.4  750.65  5297.3   751.5
  5349.5  750.66  5376.6   751.3  5428.8   750.8  5602.9  751.18  5702.2  752.56
  5734.3  752.85  5865.9  753.91    5982  755.91  6076.7  758.23  6188.9  762.41
#Mann= 5 ,-1 , 0
  4195.1     .05       0  4993.2    .033       0    5000     .05       0
  5702.2     .12       0  5734.3     .05       0
Bank Sta=4993.2,5000
XS Rating Curve= 0 ,0
Exp/Cntr=0.3,0.1