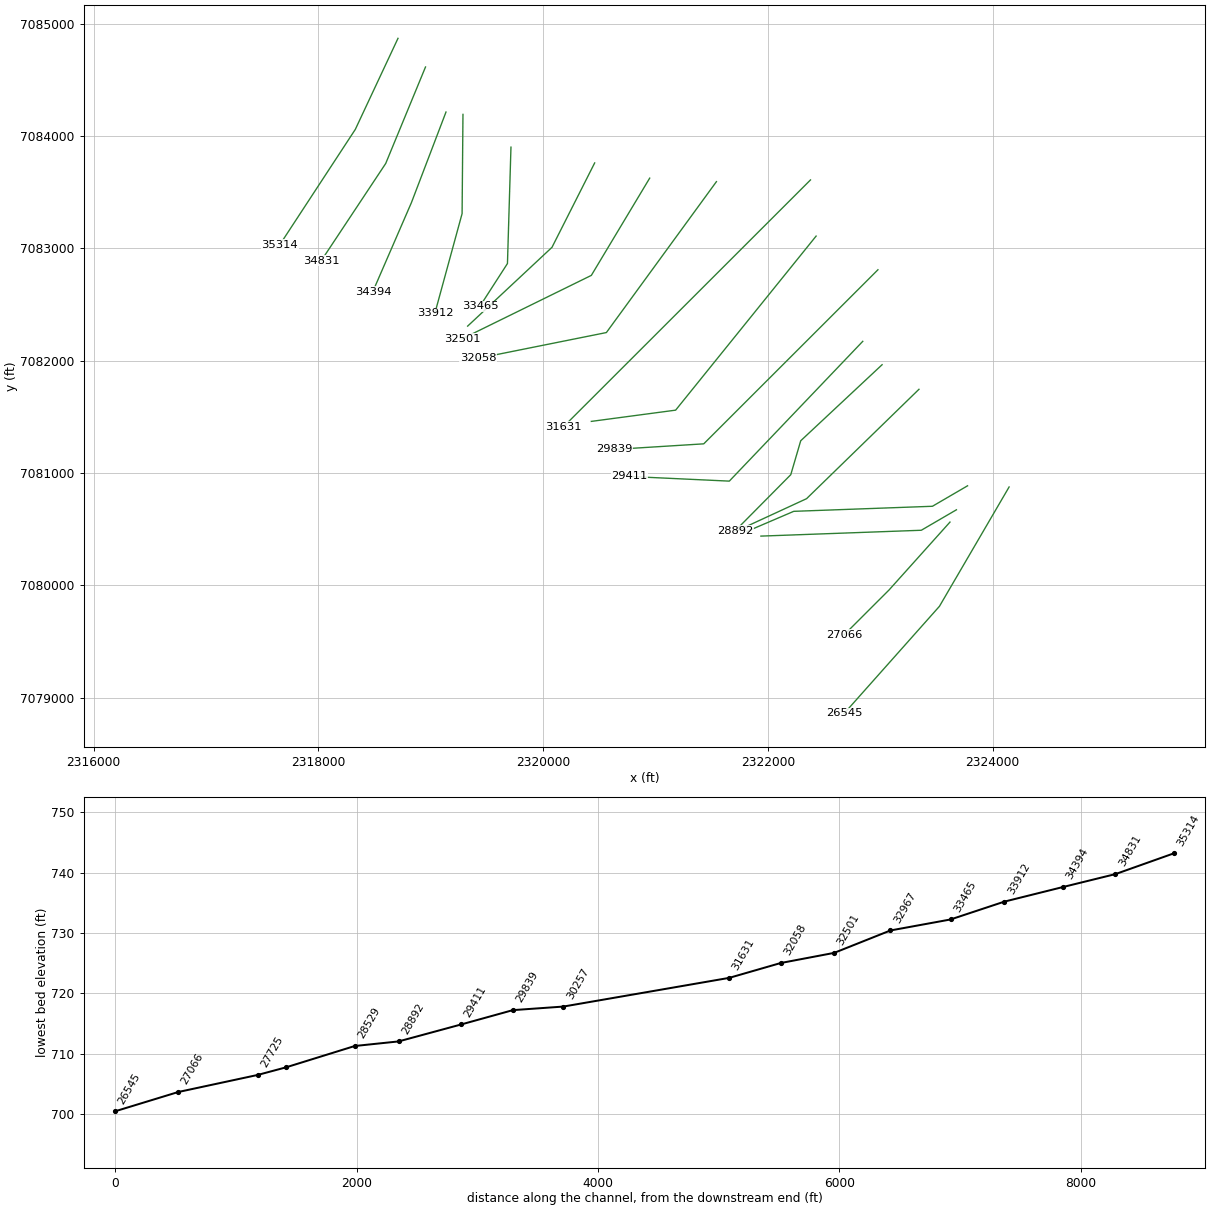
HEC-RAS study Trail Creek.prj: Trail Creek Base Level Engineering

--- Trail Creek.g01 (geometry) --- (continued)

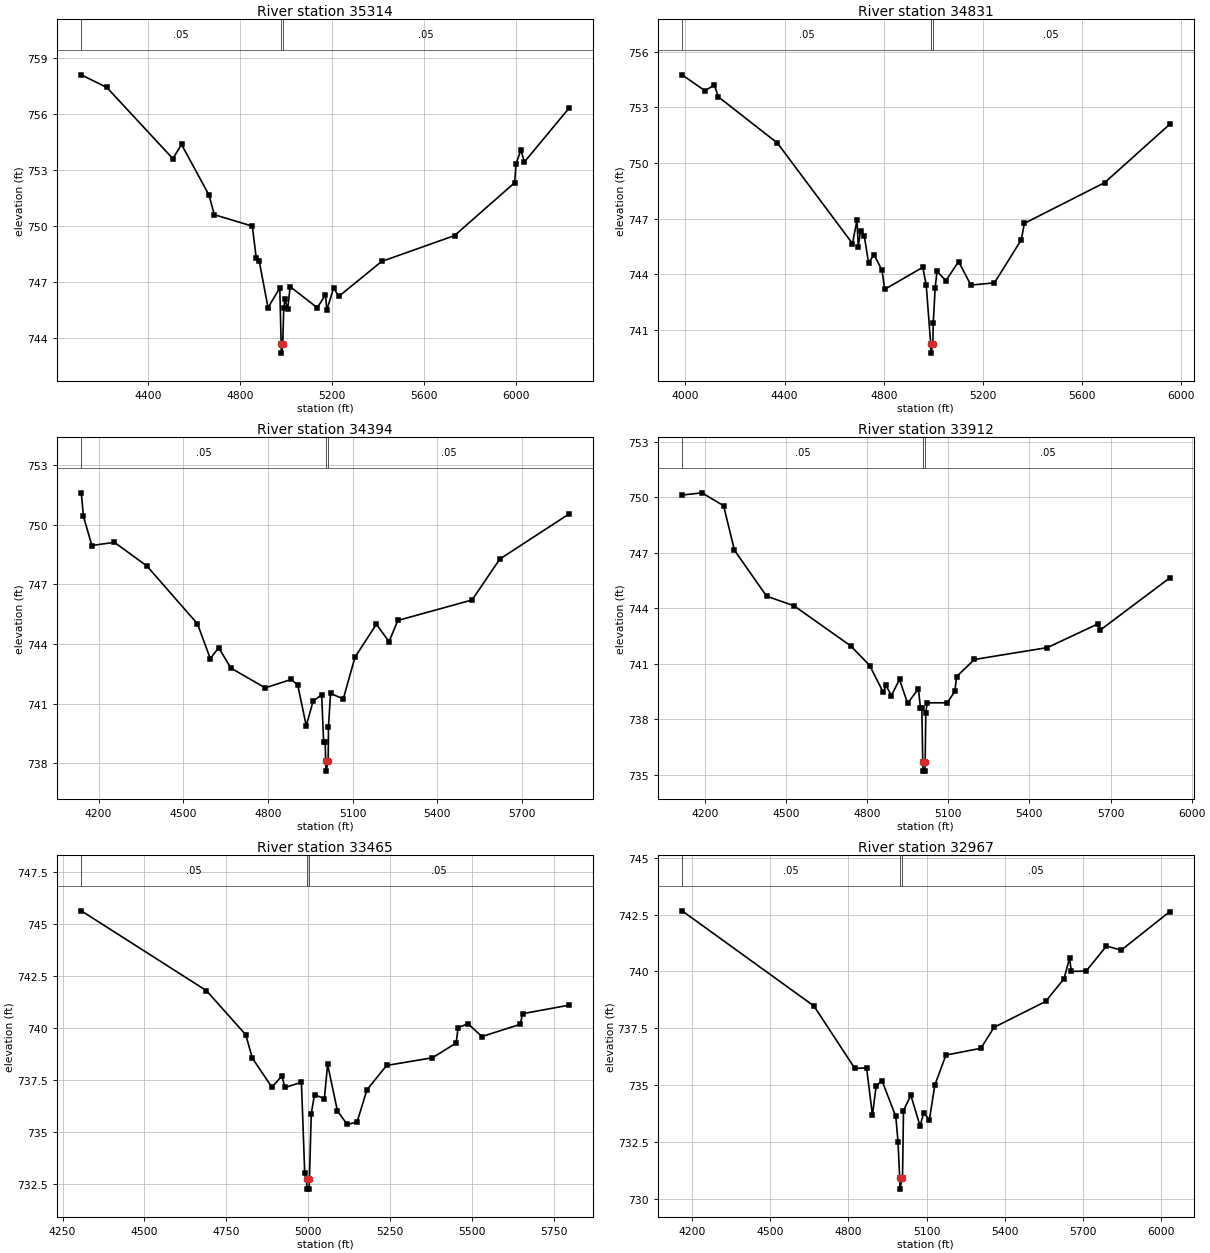
Type RM Length L Ch R = 1 ,35314   ,483,483,483
BEGIN DESCRIPTION:
Trail Creek 60.0
END DESCRIPTION:
XS GIS Cut Line= 3
      2318708.67      7084870.76        2318329.        7084060.
      2317657.49       7083033.6
#Sta/Elev= 30
  4109.3  758.12  4220.6  757.44  4507.7  753.62  4545.5  754.38  4665.2  751.66
    4688  750.61  4853.4     750  4870.7  748.29  4883.1  748.15  4921.9  745.62
  4973.1  746.68    4979  743.68  4980.1  743.18  4985.9  743.68  4990.4  745.61
  4995.9  746.06  5007.5  745.54  5018.1  746.75  5135.8  745.62  5171.9   746.3
    5178   745.5  5207.7  746.69  5229.2  746.22  5416.2   748.1  5733.5  749.49
  5995.2  752.33  6001.2  753.34  6022.3  754.09  6037.4  753.44  6231.1  756.32
#Mann= 3 ,-1 , 0
  4109.3     .05       0    4979    .033       0  4985.9     .05       0
Bank Sta=4979,4985.9
XS Rating Curve= 0 ,0
Exp/Cntr=0.3,0.1

Type RM Length L Ch R = 1 ,34831   ,437,437,437
BEGIN DESCRIPTION:
Trail Creek 59.0
END DESCRIPTION:
XS GIS Cut Line= 3
      2318953.46      7084615.56      2318599.28      7083756.15
      2318026.37      7082891.58
#Sta/Elev= 30
  3986.6  754.76  4079.1   753.9  4116.7  754.21  4133.2  753.57  4371.2  751.08
    4674  745.66    4692  746.91  4697.4   745.5  4706.5  746.33  4721.4  746.09
  4738.9  744.61  4760.5  745.06    4793  744.23    4804  743.19  4957.7  744.38
  4971.5  743.41  4989.5  740.25  4990.7  739.75  4998.2  740.25  4999.8  741.36
  5007.5  743.27  5014.9  744.16  5050.9  743.66  5102.1  744.69  5151.4  743.42
  5246.5  743.54  5354.8  745.86  5367.4  746.75  5691.7  748.95  5953.3  752.09
#Mann= 3 ,-1 , 0
  3986.6     .05       0  4989.5    .033       0  4998.2     .05       0
Bank Sta=4989.5,4998.2
XS Rating Curve= 0 ,0
Exp/Cntr=0.3,0.1

Type RM Length L Ch R = 1 ,34394   ,482,482,482
BEGIN DESCRIPTION:
Trail Creek 58.0
END DESCRIPTION:
XS GIS Cut Line= 3
      2319135.75       7084214.5        2318829.        7083410.
      2318484.69       7082615.5
#Sta/Elev= 30
    4139   751.6  4146.5  750.42  4176.6  748.95  4256.2  749.11  4371.2  747.92
  4550.5  745.01  4595.8  743.26  4625.9  743.81  4668.2  742.79  4790.4  741.79
  4882.3  742.21  4905.4  741.94  4935.8  739.88  4960.2  741.13  4990.3  741.44
  4997.3  739.07  5002.7  739.07  5004.6   738.1  5005.9   737.6  5013.4   738.1
  5014.5  739.84  5021.8  741.51  5066.9  741.23  5108.3  743.33  5184.2  744.99
  5228.9  744.11  5260.1  745.18  5523.1  746.21  5621.4  748.27  5865.9  750.53
#Mann= 3 ,-1 , 0
    4139     .05       0  5004.6    .033       0  5013.4     .05       0
Bank Sta=5004.6,5013.4
XS Rating Curve= 0 ,0
Exp/Cntr=0.3,0.1

Type RM Length L Ch R = 1 ,33912   ,447,447,447
BEGIN DESCRIPTION:
Trail Creek 57.0
END DESCRIPTION:
XS GIS Cut Line= 3
      2319286.78      7084193.64        2319279.        7083310.
      2319037.08      7082423.91
#Sta/Elev= 30
  4116.4  750.11    4190  750.23    4270  749.53    4310  747.13  4428.7  744.65
  4530.1  744.13  4740.1  741.96  4810.1   740.9  4860.1  739.45  4870.1  739.83
  4890.1  739.28  4920.1  740.15  4950.1  738.86  4990.1  739.65  4997.6   738.6
  5002.7   738.6    5006   735.7  5007.3   735.2  5013.6   735.2  5014.9   735.7
  5017.3  738.35  5022.5  738.89  5096.8  738.89  5124.5  739.51  5131.3  740.31
    5197  741.23  5466.5  741.87  5653.1  743.15  5661.4  742.81  5918.6  745.63
#Mann= 3 ,-1 , 0
  4116.4     .05       0    5006    .033       0  5014.9     .05       0
Bank Sta=5006,5014.9
XS Rating Curve= 0 ,0
Exp/Cntr=0.3,0.1

Type RM Length L Ch R = 1 ,33465   ,498,498,498
BEGIN DESCRIPTION:
Trail Creek 56.0
END DESCRIPTION:
XS GIS Cut Line= 3
      2319713.87      7083901.96      2319682.62      7082865.53
      2319437.82      7082485.32
#Sta/Elev= 30
  4307.3  745.63  4689.4  741.79  4809.5  739.67  4829.5  738.55  4889.5  737.14
  4919.5  737.68  4929.5  737.13  4979.6  737.38  4989.6  733.03  4995.1  732.74
  4996.4  732.24  5002.8  732.24  5004.1  732.74  5009.6  735.87  5019.6  736.79
  5049.6  736.59  5059.6  738.24  5089.6     736  5119.6  735.35  5149.6  735.47
  5179.7  737.02  5239.7  738.19  5379.6  738.56  5452.2  739.27  5458.1  740.01
  5488.5   740.2  5530.7  739.58  5648.1  740.17  5654.9  740.68  5796.4  741.09
#Mann= 3 ,-1 , 0
  4307.3     .05       0  4995.1    .033       0  5004.1     .05       0
Bank Sta=4995.1,5004.1
XS Rating Curve= 0 ,0
Exp/Cntr=0.3,0.1

Type RM Length L Ch R = 1 ,32967   ,466,466,466
BEGIN DESCRIPTION:
Trail Creek 55.0
END DESCRIPTION:
XS GIS Cut Line= 3
      2320458.65      7083761.34        2320079.        7083010.
      2319328.47      7082308.25
#Sta/Elev= 30
  4162.5  742.67  4668.2  738.48    4825  735.73  4869.9  735.76  4892.3  733.68
  4906.8  734.97  4929.1  735.19  4981.9  733.62  4990.4  732.51  4996.8  730.92
  4998.1  730.42  5006.3  730.92  5007.7  730.92  5011.4  733.88  5039.7  734.55
  5074.9   733.2  5089.1  733.78  5110.6  733.47  5131.6     735  5174.1  736.32
  5308.4  736.62  5358.2  737.54  5556.1  738.68  5626.9  739.68  5647.9  740.58
  5655.2     740  5711.9  740.02  5789.6  741.12  5846.2  740.94  6031.8  742.63
#Mann= 3 ,-1 , 0
  4162.5     .05       0  4996.8    .033       0  5006.3     .05       0
Bank Sta=4996.8,5006.3
XS Rating Curve= 0 ,0
Exp/Cntr=0.3,0.1

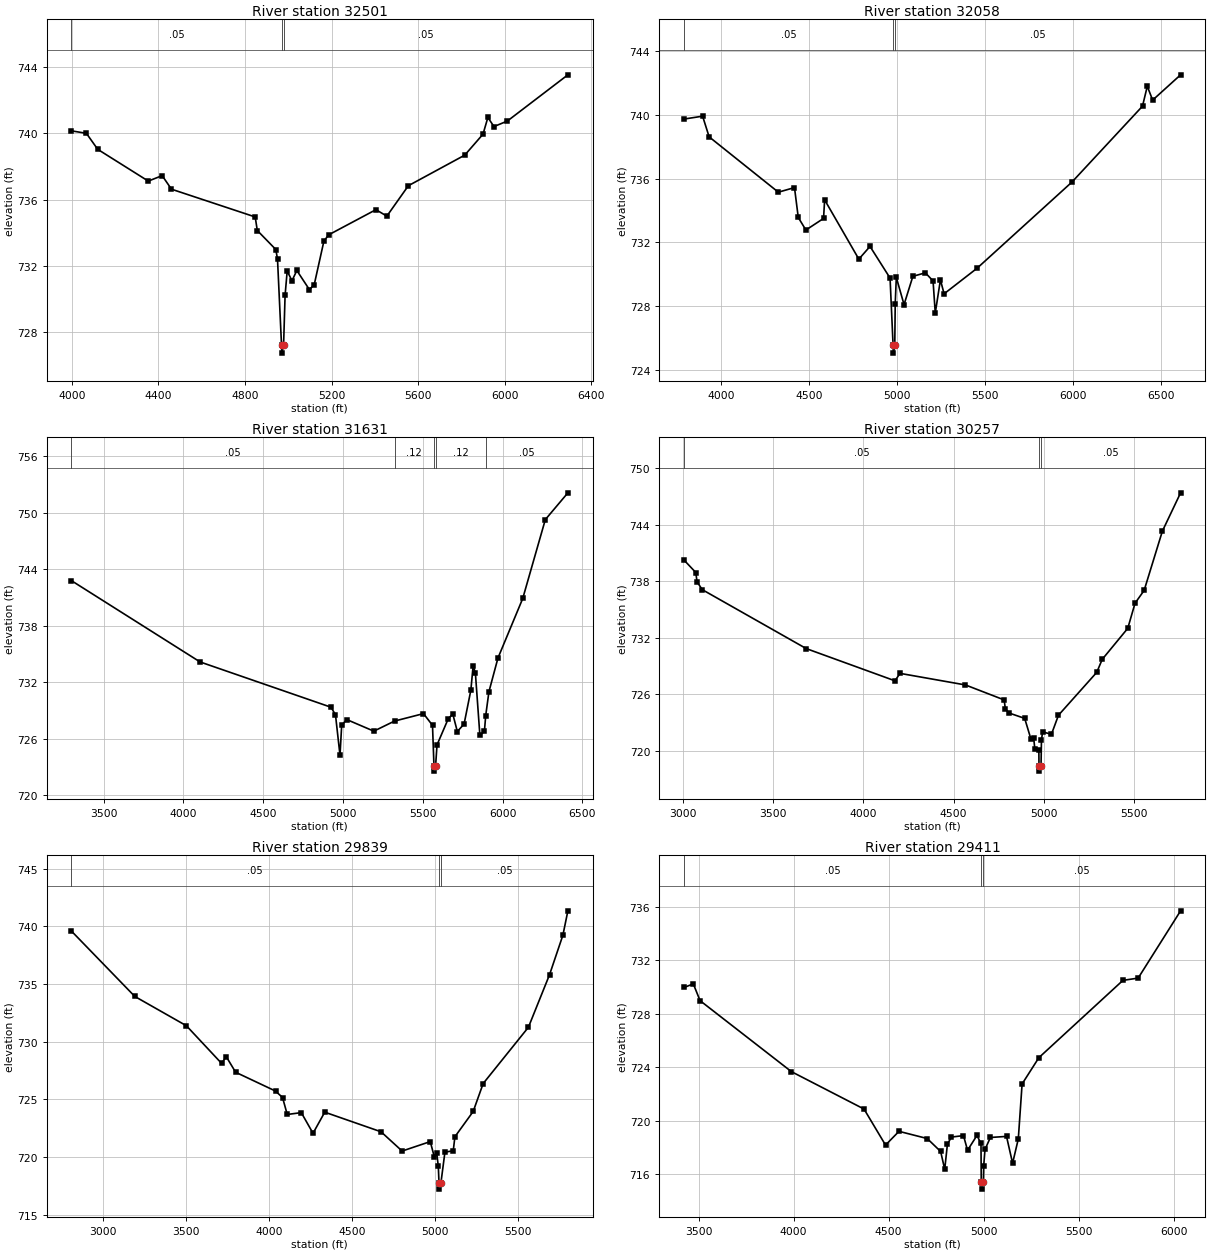
Type RM Length L Ch R = 1 ,32501   ,443,443,443
BEGIN DESCRIPTION:
Trail Creek 54.0
END DESCRIPTION:
XS GIS Cut Line= 3
      2320948.26      7083625.97        2320429.        7082760.
      2319277.78      7082194.35
#Sta/Elev= 30
  3998.8  740.16  4067.6  740.01  4120.1  739.04  4353.4  737.12  4417.6  737.45
  4460.5  736.63  4847.2  734.95  4856.9  734.13  4942.4  732.98  4950.2   732.4
  4968.7  727.21  4970.1  726.71  4978.3  727.21  4985.2   730.2  4994.9  731.68
    5017  731.09  5039.5  731.71  5097.7  730.55  5119.9  730.86  5164.5  733.49
  5186.8  733.87  5404.7  735.39  5455.2     735  5554.5  736.84  5814.9  738.69
  5899.3  739.96  5921.7  740.97  5949.8  740.42  6011.3  740.75  6291.2  743.55
#Mann= 3 ,-1 , 0
  3998.8     .05       0  4968.7    .033       0  4978.3     .05       0
Bank Sta=4968.7,4978.3
XS Rating Curve= 0 ,0
Exp/Cntr=0.3,0.1

Type RM Length L Ch R = 1 ,32058   ,427,427,427
BEGIN DESCRIPTION:
Trail Creek 53.0
END DESCRIPTION:
XS GIS Cut Line= 3
      2321541.97      7083594.67      2320562.83      7082250.94
      2319423.12      7082021.96
#Sta/Elev= 30
  3788.3  739.75  3893.1  739.93  3930.2  738.63  4324.1  735.15    4416  735.44
  4437.5  733.56  4480.9  732.77  4581.4   733.5  4587.5  734.67  4782.2  730.94
  4845.8  731.74  4959.9  729.75  4977.1  725.53  4978.5  725.03  4986.7  725.53
  4989.3  728.14  4995.5  729.79  5039.5  728.08  5089.7  729.86  5160.8  730.08
  5204.6  729.57  5217.2  727.55  5246.5  729.64  5267.4  728.76  5455.4  730.37
  5995.4  735.79  6396.6  740.56  6423.8  741.81  6454.4  740.94  6613.4  742.53
#Mann= 3 ,-1 , 0
  3788.3     .05       0  4977.1    .033       0  4986.7     .05       0
Bank Sta=4977.1,4986.7
XS Rating Curve= 0 ,0
Exp/Cntr=0.3,0.1

Type RM Length L Ch R = 1 ,31631   ,1374,1374,1374
BEGIN DESCRIPTION:
Trail Creek 52.0
END DESCRIPTION:
XS GIS Cut Line= 3
      2322378.99      7083609.99        2321179.        7082410.
      2320179.03      7081410.03
#Sta/Elev= 30
  3298.6  742.77  4104.7  734.15  4924.9  729.35  4953.2  728.55  4981.5  724.25
  4992.1  727.44  5023.9  728.04  5193.6  726.81  5323.3  727.88  5504.8  728.67
  5561.3  727.43  5570.6  723.07    5572  722.57  5580.4  723.07  5589.6  725.35
  5660.3  728.14  5688.6  728.62  5716.9  726.77  5759.3  727.57  5801.7  731.16
  5815.9  733.74    5830     733  5858.3  726.35  5886.6  726.79  5894.8  728.46
  5914.9  730.99  5971.4  734.56    6127  740.89  6268.4  749.25  6409.8  752.09
#Mann= 5 ,-1 , 0
  3298.6     .05       0  5323.3     .12       0  5570.6    .033       0
  5580.4     .12       0  5894.8     .05       0
Bank Sta=5570.6,5580.4
XS Rating Curve= 0 ,0
Exp/Cntr=0.3,0.1

Type RM Length L Ch R = 1 ,30257   ,418,418,418
BEGIN DESCRIPTION:
Trail Creek 51.0
END DESCRIPTION:
XS GIS Cut Line= 3
      2322428.97      7083109.96        2321179.        7081560.
      2320429.02        7081460.
#Sta/Elev= 30
  3008.8  740.21    3073  738.91  3079.9  737.92  3108.7  737.09  3684.5  730.83
  4175.5  727.41  4203.5   728.2  4565.8  726.97    4780  725.38  4786.5  724.43
  4807.3  723.99  4893.6  723.42  4928.8  721.18  4943.2  721.37  4949.6  720.19
    4972  720.07  4972.8  718.32  4974.4  717.82  4983.9  718.32  4986.4  721.12
  4992.8  721.99  5041.6  721.73  5080.7  723.76  5292.5  728.31  5322.8  729.69
  5464.1  732.98  5504.4  735.65  5554.8  737.01  5655.7   743.3  5756.6  747.37
#Mann= 3 ,-1 , 0
  3008.8     .05       0  4972.8     .04       0  4983.9     .05       0
Bank Sta=4972.8,4983.9
XS Rating Curve= 0 ,0
Exp/Cntr=0.3,0.1

Type RM Length L Ch R = 1 ,29839   ,428,428,428
BEGIN DESCRIPTION:
Trail Creek 50.0
END DESCRIPTION:
XS GIS Cut Line= 3
      2322978.99      7082809.99        2321429.        7081260.
      2320628.98        7081210.
#Sta/Elev= 30
  2808.2  739.59    3190  733.93  3501.2  731.39  3713.3  728.13  3741.6  728.71
  3798.1  727.36  4038.6  725.73    4081  725.17  4109.3   723.7  4194.1  723.86
  4264.8  722.07  4335.5   723.9    4675   722.2  4802.2  720.53  4971.9  721.35
  4996.7     720  5010.2   720.4  5020.3  719.23  5024.7  717.73  5026.3  717.23
  5035.8  717.73  5060.3  720.44  5110.4  720.55  5120.5  721.77  5230.7  723.96
  5290.8  726.38  5563.8  731.26  5691.6  735.83  5771.7  739.24  5801.8  741.35
#Mann= 3 ,-1 , 0
  2808.2     .05       0  5024.7    .033       0  5035.8     .05       0
Bank Sta=5024.7,5035.8
XS Rating Curve= 0 ,0
Exp/Cntr=0.3,0.1

Type RM Length L Ch R = 1 ,29411   ,519,519,519
BEGIN DESCRIPTION:
Trail Creek 49.0
END DESCRIPTION:
XS GIS Cut Line= 3
      2322844.08      7082172.83      2321656.58      7080928.03
      2320765.93       7080969.7
#Sta/Elev= 30
  3424.3  729.97  3472.2  730.24  3507.8  728.98  3988.7  723.66  4370.5  720.86
  4483.7  718.16  4554.5  719.19    4703  718.65  4773.7  717.68  4795.1  716.34
  4809.3  718.22  4830.3  718.76  4893.9  718.87  4915.3  717.77  4964.6  718.88
    4986  718.28  4987.4  715.36  4988.9  714.86  4998.5  715.36  5000.2  716.61
  5007.1  717.83  5035.4  718.73  5120.3  718.81  5152.3   716.8  5182.3  718.62
  5202.3  722.74  5290.6  724.71  5732.9   730.5    5813  730.67  6036.3  735.71
#Mann= 3 ,-1 , 0
  3424.3     .05       0  4987.4    .033       0  4998.5     .05       0
Bank Sta=4987.4,4998.5
XS Rating Curve= 0 ,0
Exp/Cntr=0.3,0.1

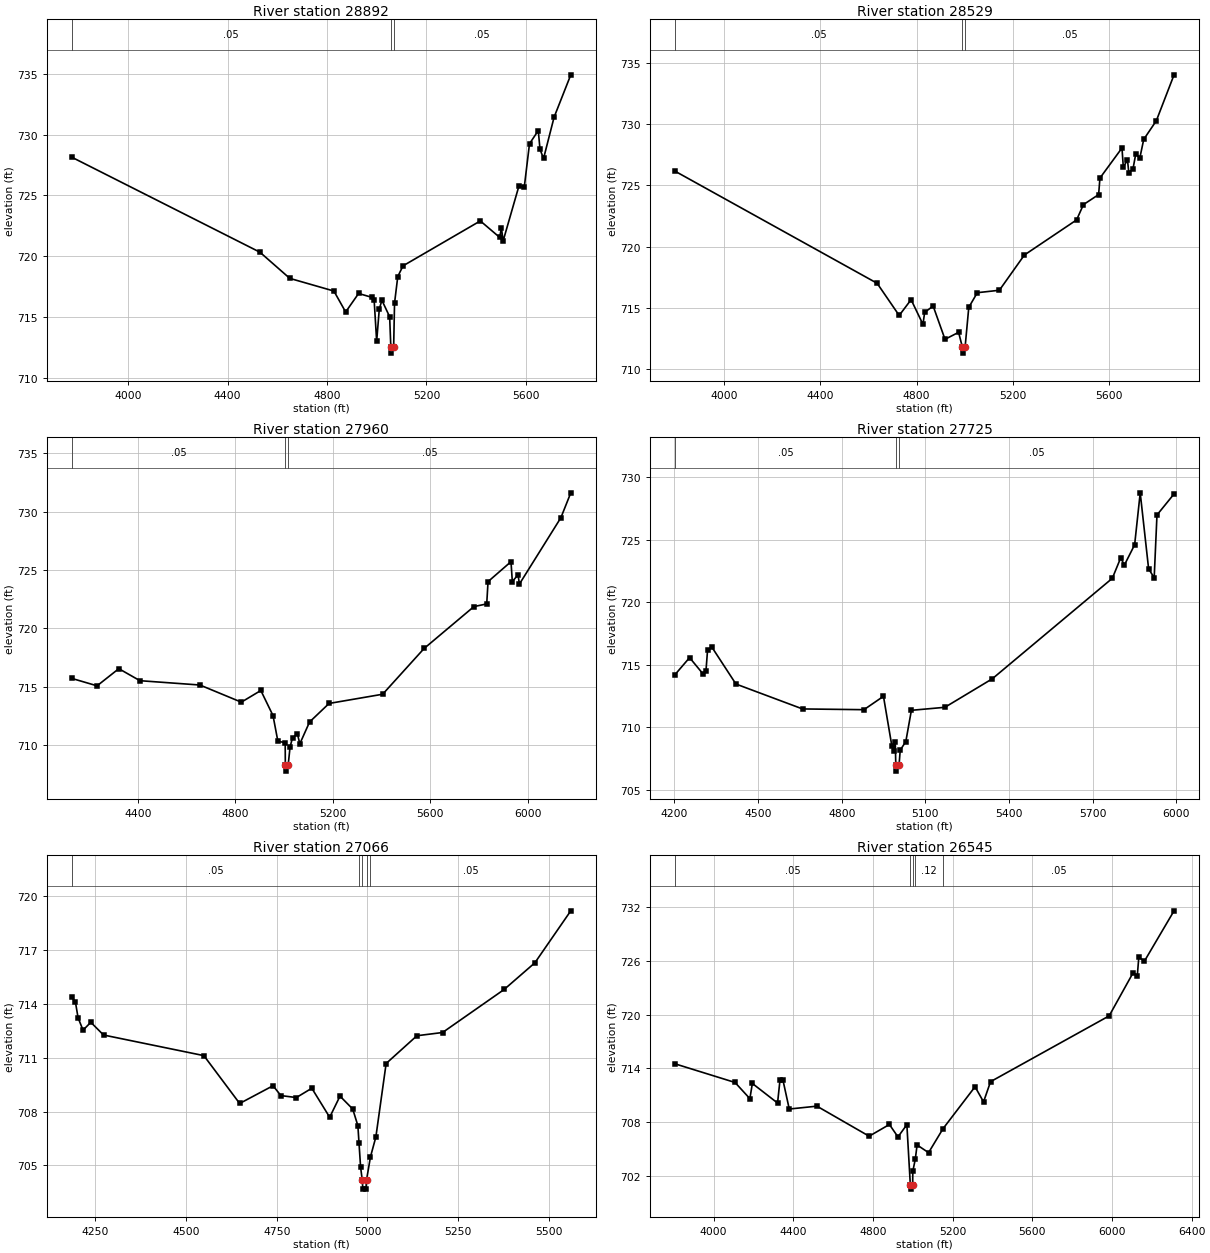
Type RM Length L Ch R = 1 ,28892   ,363,363,363
BEGIN DESCRIPTION:
Trail Creek 48.0
END DESCRIPTION:
XS GIS Cut Line= 4
      2323015.96       7081964.5      2322291.99       7081287.4
      2322203.45      7080985.32      2321708.65      7080485.31
#Sta/Elev= 30
  3771.8  728.15  4529.9  720.34  4650.1  718.19  4827.6  717.15    4875  715.43
  4927.1  716.95  4979.2  716.64  4989.6  716.43  4999.8  713.02  5010.4  715.67
  5020.9  716.39  5052.1  715.04  5056.8  712.55  5058.4  712.05  5068.2  712.55
  5071.8  716.16  5084.8  718.34    5106  719.22  5417.1  722.91  5494.9  721.56
    5502  722.32    5509  721.27  5572.7  725.79  5593.9  725.66  5615.1  729.25
  5650.4  730.33  5657.5  728.78  5671.7  728.04  5714.1  731.43  5781.3  734.91
#Mann= 3 ,-1 , 0
  3771.8     .05       0  5056.8    .033       0  5068.2     .05       0
Bank Sta=5056.8,5068.2
XS Rating Curve= 0 ,0
Exp/Cntr=0.3,0.1

Type RM Length L Ch R = 1 ,28529   ,569,569,569
BEGIN DESCRIPTION:
Trail Creek 47.0
END DESCRIPTION:
XS GIS Cut Line= 3
       2323344.1      7081745.76      2322344.08      7080771.78
      2321724.32      7080485.34
#Sta/Elev= 30
  3793.7  726.17  4635.9     717  4727.8  714.37  4777.4  715.66  4826.8  713.64
  4833.8  714.62  4869.2  715.14  4918.6  712.42  4975.2  712.99  4990.8  711.79
  4992.3  711.29  5002.3  711.79  5017.6  715.03  5053.1  716.23    5145  716.43
  5249.1  719.31  5466.6  722.18    5495  723.43  5558.3  724.25  5563.8   725.6
  5655.6  728.06  5661.1   726.5  5678.5  727.08    5684  726.05  5701.4  726.35
    5713  727.57  5729.9  727.24  5746.1  728.76  5798.7  730.29  5872.4  734.04
#Mann= 3 ,-1 , 0
  3793.7     .05       0  4990.8     .04       0  5002.3     .05       0
Bank Sta=4990.8,5002.3
XS Rating Curve= 0 ,0
Exp/Cntr=0.3,0.1

Type RM Length L Ch R = 1 ,27960   ,235,235,235
BEGIN DESCRIPTION:
Trail Creek 46.2
END DESCRIPTION:
XS GIS Cut Line= 4
       2323776.4      7080886.38      2323463.87      7080704.07
        2322230.      7080659.04      2321813.41      7080480.36
#Sta/Elev= 30
  4127.9  715.71  4232.4  715.07  4321.7  716.54  4408.5  715.51  4654.7  715.14
  4824.8  713.67  4904.9  714.67  4954.9  712.52  4974.9  710.32  5004.9   710.2
  5005.5  708.26  5007.1  707.76  5017.1  708.26  5024.9  709.83    5035  710.62
    5055  710.96    5065   710.1    5105  711.97  5185.1  713.56  5405.2  714.35
  5575.3  718.27  5779.9  721.86  5832.5  722.09  5837.9     724  5932.2  725.71
  5937.6  724.01  5961.2  724.58  5966.7  723.79  6137.1  729.48  6177.7  731.61
#Mann= 3 ,-1 , 0
  4127.9     .05       0  5005.5    .033       0  5017.1     .05       0
Bank Sta=5005.5,5017.1
XS Rating Curve= 0 ,0
Exp/Cntr=0.3,0.1

Type RM Length L Ch R = 1 ,27725   ,659,659,659
BEGIN DESCRIPTION:
Trail Creek 46.0
END DESCRIPTION:
XS GIS Cut Line= 3
      2323677.39      7080672.81      2323364.91      7080490.53
      2321937.82      7080438.44
#Sta/Elev= 30
  4201.9   714.2  4254.6  715.57  4304.2  714.23  4313.3  714.49  4319.1  716.18
  4334.8   716.4  4420.8  713.46  4659.6  711.47  4879.8  711.41  4949.8  712.48
  4979.8  708.52  4987.1  708.07  4992.1  708.86    4994     707  4995.7   706.5
  5005.7     707  5009.9  708.18  5029.9  708.86  5049.9  711.36    5170   711.6
  5340.1  713.88  5770.4  721.91  5800.4  723.54  5813.7  722.97  5850.4  724.59
  5870.4  728.74  5900.5  722.67  5920.5  721.95  5930.5  726.97  5991.7  728.65
#Mann= 3 ,-1 , 0
  4201.9     .05       0    4994    .033       0  5005.7     .05       0
Bank Sta=4994,5005.7
XS Rating Curve= 0 ,0
Exp/Cntr=0.3,0.1

Type RM Length L Ch R = 1 ,27066   ,521,521,521
BEGIN DESCRIPTION:
Trail Creek 45.0
END DESCRIPTION:
XS GIS Cut Line= 3
      2323620.13      7080563.46        2323079.        7079960.
      2322679.03      7079560.03
#Sta/Elev= 30
  4184.4  714.38  4194.7  714.13  4202.2  713.23  4215.9  712.54  4237.3  712.98
  4272.4  712.27    4549  711.12  4647.7  708.45  4739.7  709.44  4761.3  708.89
    4804  708.78  4846.6   709.3  4895.9  707.68  4924.3  708.86  4959.4  708.14
  4973.6  707.21  4976.8  706.22  4981.1   704.9  4985.7  704.17  4987.3  703.67
  4995.8  703.67  4997.4  704.17  5008.3  705.47  5023.2  706.58  5051.5  710.68
  5136.4  712.23  5207.1  712.41  5376.8  714.81  5461.6   716.3  5560.6   719.2
#Mann= 5 ,-1 , 0
  4184.4     .05       0  4976.8     .12       0  4985.7     .07       0
  4997.4     .12       0  5008.3     .05       0
Bank Sta=4985.7,4997.4
XS Rating Curve= 0 ,0
Exp/Cntr=0.3,0.1

Type RM Length L Ch R = 1 ,26545   ,411,411,411
BEGIN DESCRIPTION:
Trail Creek 44.0
END DESCRIPTION:
XS GIS Cut Line= 3
      2324146.14      7080875.91      2323526.37      7079813.44
        2322679.        7078860.
#Sta/Elev= 30
    3806  714.51    4108  712.42  4182.4  710.61  4194.9  712.31  4321.4  710.12
  4333.8  712.74  4348.6  712.67  4380.1  709.45    4519  709.77  4781.1  706.41
  4882.8  707.72  4925.8  706.33  4970.5   707.7  4987.8  700.99  4989.5  700.49
  4999.6  700.99  5000.3  702.49  5012.7  703.83  5021.8  705.43  5079.4  704.57
  5151.9  707.25  5312.7  711.94  5355.4  710.25  5390.5  712.51  5985.9  719.87
  6106.3   724.7  6127.2  724.38  6134.7  726.42  6163.2     726  6311.6  731.62
#Mann= 5 ,-1 , 0
    3806     .05       0  4987.8    .033       0  4999.6     .05       0
  5012.7     .12       0  5151.9     .05       0
Bank Sta=4987.8,4999.6
XS Rating Curve= 0 ,0
Exp/Cntr=0.3,0.1