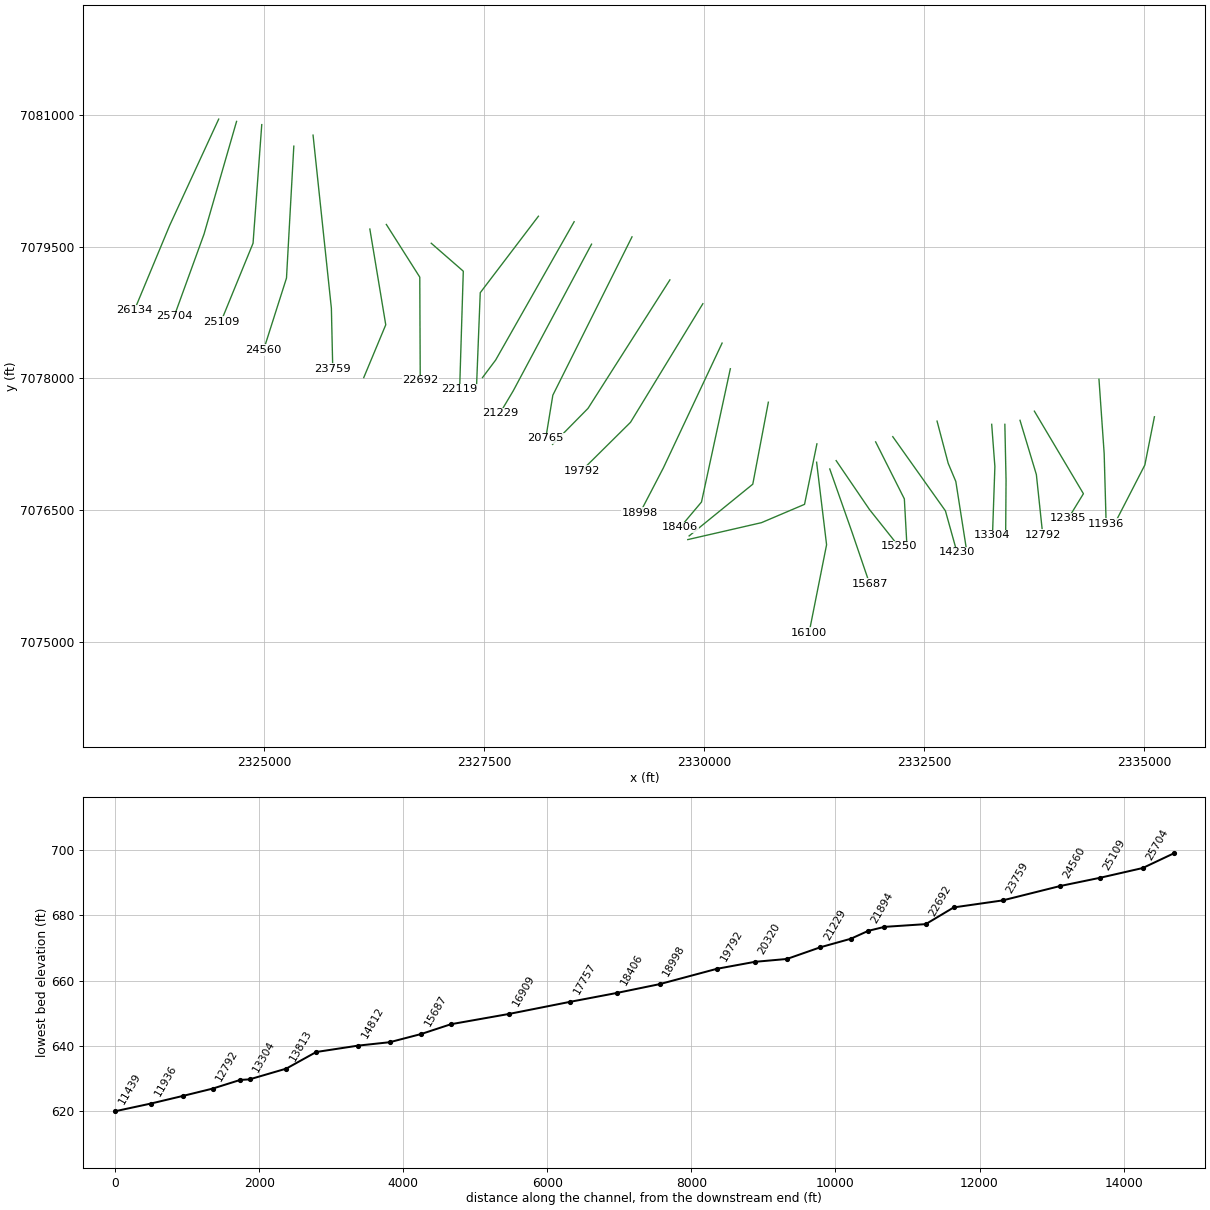
HEC-RAS study Trail Creek.prj: Trail Creek Base Level Engineering

--- Trail Creek.g01 (geometry) --- (continued)

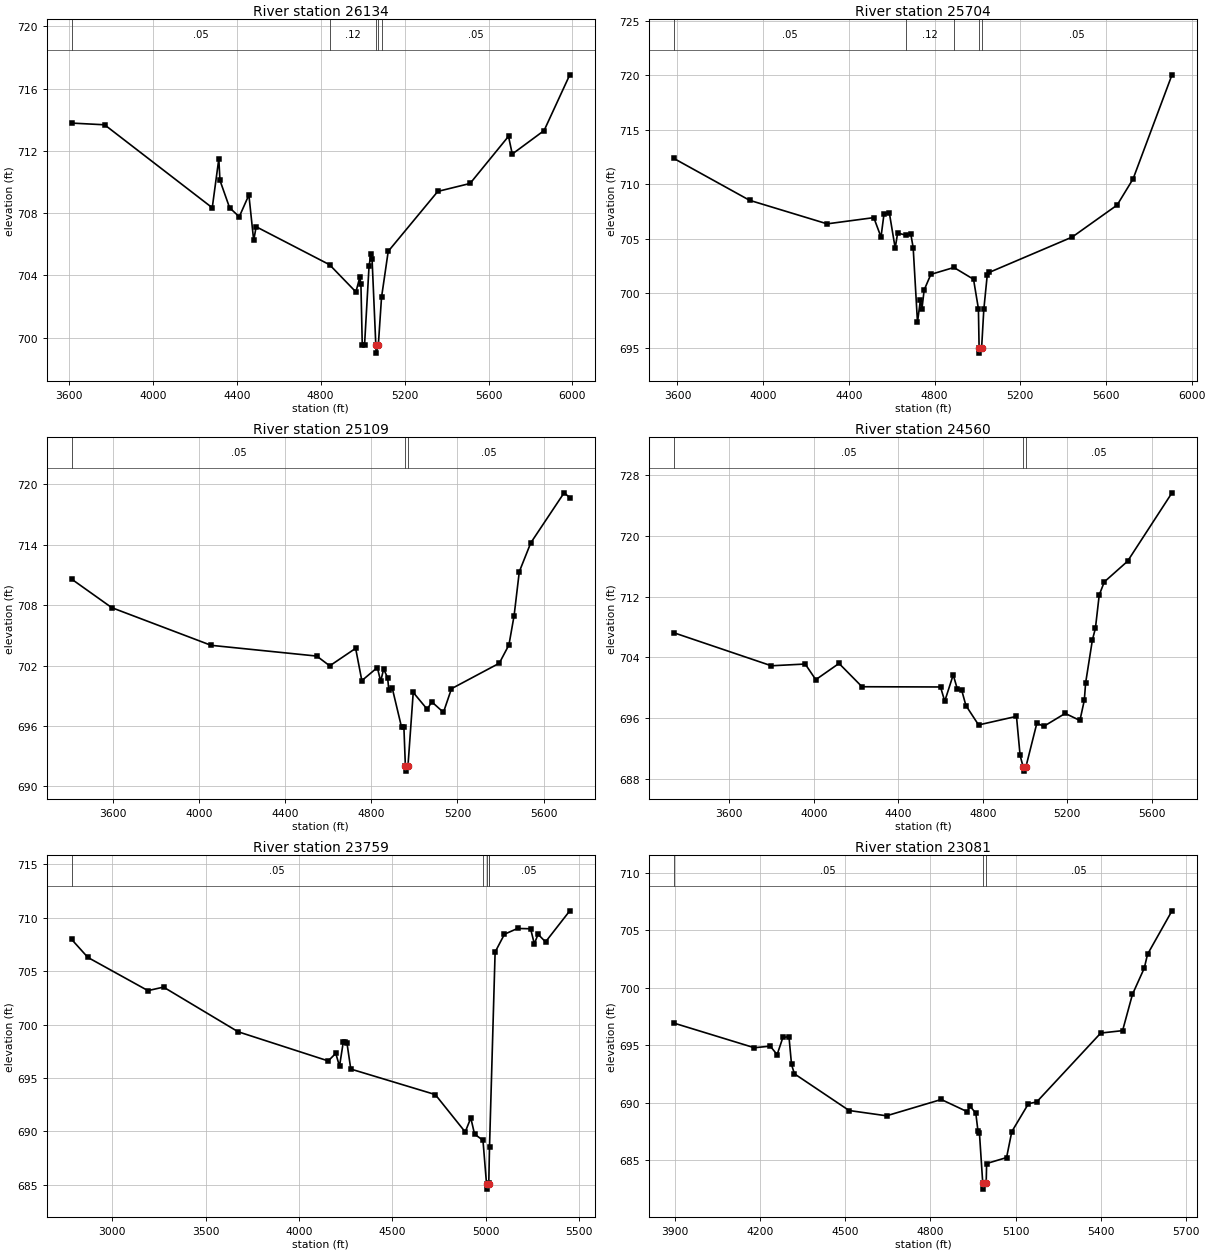
Type RM Length L Ch R = 1 ,26134   ,430,430,430
BEGIN DESCRIPTION:
Trail Creek 43.0
END DESCRIPTION:
XS GIS Cut Line= 3
      2324479.47      7080948.82       2323922.2      7079740.53
      2323521.15      7078776.96
#Sta/Elev= 30
  3612.9  713.78  3770.3  713.67  4283.3  708.34  4314.6  711.48  4320.1   710.1
    4366  708.34    4412  707.76  4457.9  709.16  4480.8  706.24  4492.6  707.12
  4842.4  704.68    4968  702.93  4986.4  703.87  4991.8  703.45  4998.2  699.54
  5009.1  699.52  5030.7  704.62  5039.5  705.35  5044.9  705.06  5062.9   699.5
  5064.5     699  5074.7   699.5    5090  702.58  5121.9  705.54  5358.2  709.39
    5512   709.9  5695.2  712.93  5713.1  711.79  5864.8   713.3  5987.2  716.88
#Mann= 5 ,-1 , 0
  3612.9     .05       0  4842.4     .12       0  5062.9     .07       0
  5074.7     .12       0    5090     .05       0
Bank Sta=5062.9,5074.7
XS Rating Curve= 0 ,0
Exp/Cntr=0.3,0.1

Type RM Length L Ch R = 1 ,25704   ,595,595,595
BEGIN DESCRIPTION:
Trail Creek 42.0
END DESCRIPTION:
XS GIS Cut Line= 3
      2324682.63      7080922.85      2324312.83      7079641.57
       2323974.3      7078709.31
#Sta/Elev= 30
  3582.8  712.37  3936.5  708.53  4298.7  706.37  4516.4  706.94    4550  705.16
  4564.1  707.29  4588.9  707.38  4616.2  704.15  4627.7  705.53  4664.6  705.34
    4689  705.45  4700.2  704.18  4720.3  697.35  4733.9  699.38  4741.1  698.58
  4751.5  700.31  4782.7  701.74  4890.4  702.37  4981.9  701.29  5004.7  698.59
  5007.9  695.02  5009.5  694.52  5019.7  695.02  5029.9  698.52  5045.7  701.64
  5055.2  701.92  5442.5  705.16  5652.1  708.09  5726.6  710.49  5908.2  720.03
#Mann= 5 ,-1 , 0
  3582.8     .05       0  4664.6     .12       0  4890.4     .05       0
  5007.9    .033       0  5019.7     .05       0
Bank Sta=5007.9,5019.7
XS Rating Curve= 0 ,0
Exp/Cntr=0.3,0.1

Type RM Length L Ch R = 1 ,25109   ,549,549,549
BEGIN DESCRIPTION:
Trail Creek 41.0
END DESCRIPTION:
XS GIS Cut Line= 3
      2324969.07      7080886.33      2324870.12       7079537.4
      2324505.54      7078646.79
#Sta/Elev= 30
  3406.9   710.6  3593.7  707.76    4055  704.02  4546.3  702.95  4606.4  701.98
  4726.8  703.72  4755.6  700.51  4827.6  701.81  4843.1  700.45    4857  701.66
  4875.5  700.79    4881  699.55  4897.1  699.75  4940.3  695.87  4951.1  695.86
  4957.9  692.02  4959.5  691.52  4969.9  692.02  4994.4  699.34  5059.2  697.67
  5080.8   698.4  5134.8  697.36  5172.1  699.71  5394.2  702.24  5439.1  704.06
  5463.1  706.97  5487.2  711.33  5540.6   714.2  5695.4  719.17  5721.8   718.7
#Mann= 3 ,-1 , 0
  3406.9     .05       0  4957.9    .033       0  4969.9     .05       0
Bank Sta=4957.9,4969.9
XS Rating Curve= 0 ,0
Exp/Cntr=0.3,0.1

Type RM Length L Ch R = 1 ,24560   ,801,801,801
BEGIN DESCRIPTION:
Trail Creek 40.5
END DESCRIPTION:
XS GIS Cut Line= 3
      2325333.66      7080641.54      2325250.33      7079141.57
      2324990.08      7078324.39
#Sta/Elev= 30
  3336.5  707.24  3798.8  702.89    3959  703.12  4009.1  701.06  4119.2   703.2
  4228.1  700.13    4600   700.1    4620  698.22  4660.1   701.7  4680.1  699.79
  4700.1   699.7  4720.2  697.66  4780.3   695.1  4959.8  696.23  4976.9   691.1
  4991.9  689.52  4993.5  689.02  5003.9  689.52  5056.5  695.35  5088.7  694.91
  5190.6  696.62  5260.3  695.69  5281.2  698.36  5287.2  700.61  5319.5  706.31
  5333.7  707.82  5351.7   712.2  5375.7  713.93  5485.8  716.65  5696.4  725.66
#Mann= 3 ,-1 , 0
  3336.5     .05       0  4991.9    .033       0  5003.9     .05       0
Bank Sta=4991.9,5003.9
XS Rating Curve= 0 ,0
Exp/Cntr=0.3,0.1

Type RM Length L Ch R = 1 ,23759   ,678,678,678
BEGIN DESCRIPTION:
Trail Creek 40.0
END DESCRIPTION:
XS GIS Cut Line= 3
       2325552.4      7080766.61      2325760.74      7078797.82
      2325776.37      7078110.28
#Sta/Elev= 30
  2782.3  707.98  2869.4  706.29  3191.2  703.18  3274.6  703.51  3673.9  699.33
  4156.5   696.6  4196.8  697.31  4216.9   696.1    4237  698.36    4247   698.4
  4257.1  698.24  4277.2  695.84  4729.7  693.45  4889.9  689.95  4919.9  691.26
  4939.9  689.75    4985  689.17    5004   685.1  5005.6   684.6    5016   685.1
  5016.1  685.19    5020  688.53    5050  706.79    5100  708.46    5170     709
    5240  708.97    5260  707.56    5280  708.46    5320  707.74  5449.8  710.65
#Mann= 5 ,-1 , 0
  2782.3     .05       0    4985     .12       0    5004     .07       0
    5016     .12       0  5016.1     .05       0
Bank Sta=5004,5016
XS Rating Curve= 0 ,0
Exp/Cntr=0.3,0.1

Type RM Length L Ch R = 1 ,23081   ,389,389,389
BEGIN DESCRIPTION:
Trail Creek 39.0
END DESCRIPTION:
XS GIS Cut Line= 3
      2326198.24      7079698.89        2326379.        7078610.
        2326129.      7078009.99
#Sta/Elev= 30
  3896.3  696.93  4179.9  694.78  4235.8  694.92  4260.1  694.18  4280.4  695.68
  4301.8  695.74  4310.8  693.32  4320.9  692.51  4513.5  689.31  4645.3  688.85
  4837.9  690.27  4929.1  689.21  4939.3  689.68  4959.5  689.08  4967.1  687.52
  4972.2  687.38    4984  682.96  4985.6  682.46    4996  682.96  4997.6  684.69
  5067.8  685.21  5086.2  687.47  5144.7   689.9    5174  690.06  5399.3  696.06
  5476.2  696.27  5510.9  699.43  5552.6  701.72    5564  702.92  5650.1  706.71
#Mann= 3 ,-1 , 0
  3896.3     .05       0    4984    .033       0    4996     .05       0
Bank Sta=4984,4996
XS Rating Curve= 0 ,0
Exp/Cntr=0.3,0.1

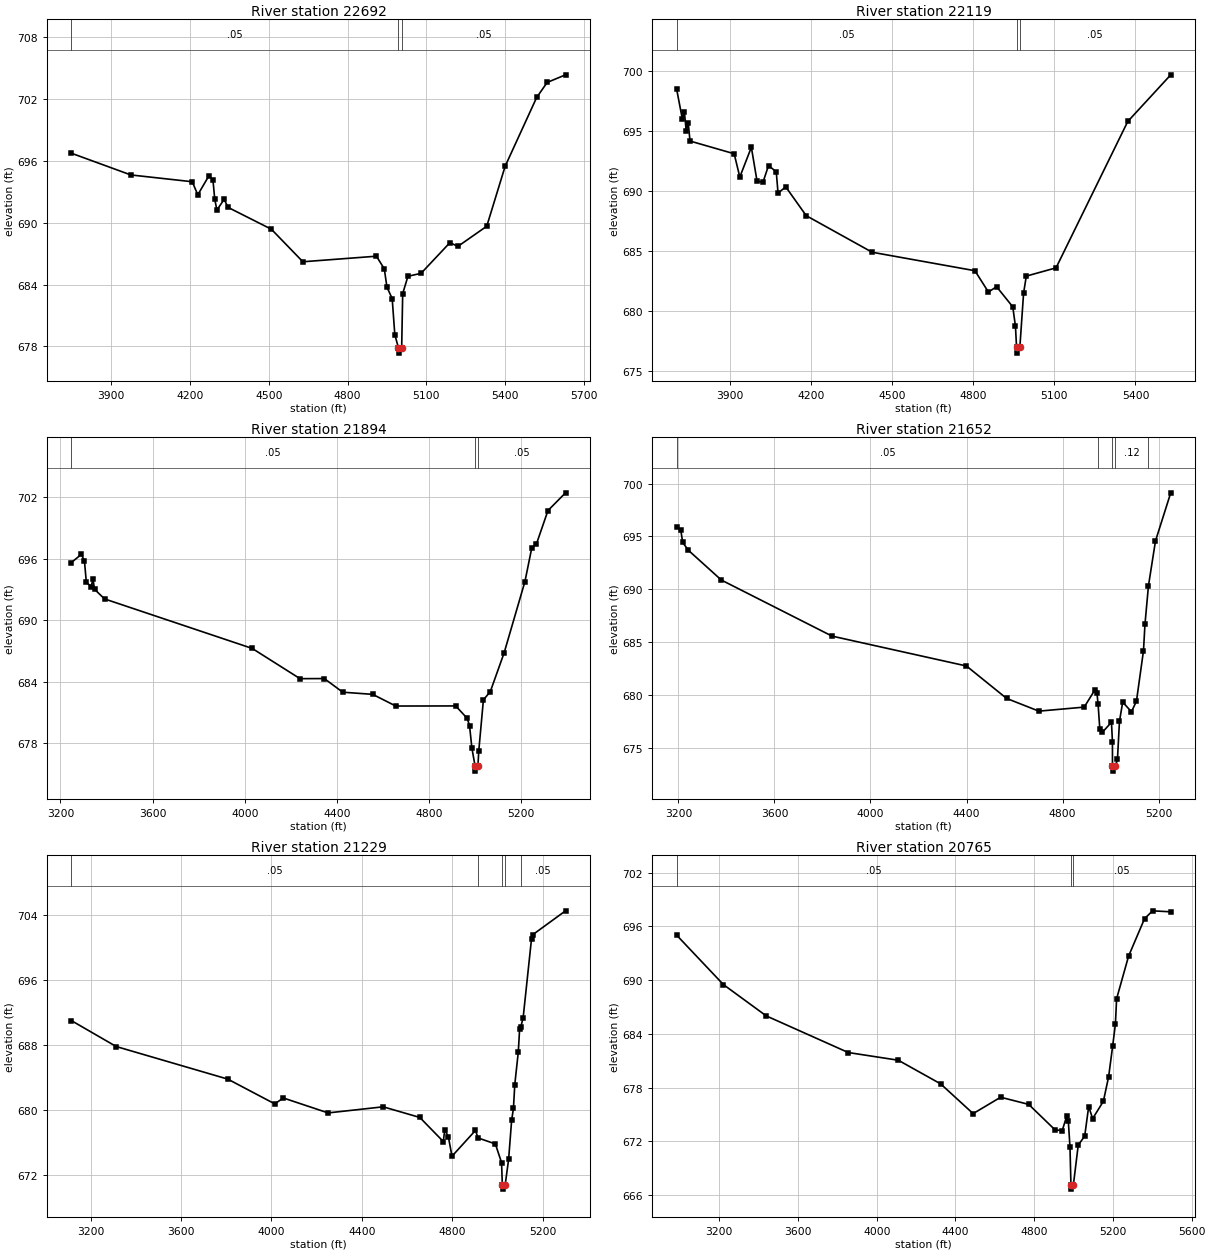
Type RM Length L Ch R = 1 ,22692   ,573,573,573
BEGIN DESCRIPTION:
Trail Creek 38.0
END DESCRIPTION:
XS GIS Cut Line= 3
      2326385.76      7079750.92      2326765.95      7079151.99
      2326771.16      7077980.12
#Sta/Elev= 30
  3748.6  696.75    3975  694.64  4208.8  693.98  4229.9  692.71  4272.3  694.56
  4287.5  694.18  4294.5  692.26  4302.8  691.23  4330.1  692.27  4345.1  691.49
    4510  689.37    4630  686.21    4910  686.75    4940  685.52    4950  683.75
    4970  682.63    4980  679.13    4994  677.84  4995.7  677.34  5006.1  677.84
    5010  683.12    5030   684.8    5080  685.09    5190  688.07    5220   687.7
    5330  689.66    5400  695.48    5520  702.16    5560  703.62  5629.9  704.36
#Mann= 3 ,-1 , 0
  3748.6     .05       0    4994    .033       0  5006.1     .05       0
Bank Sta=4994,5006.1
XS Rating Curve= 0 ,0
Exp/Cntr=0.3,0.1

Type RM Length L Ch R = 1 ,22119   ,225,225,225
BEGIN DESCRIPTION:
Trail Creek 37.3
END DESCRIPTION:
XS GIS Cut Line= 3
      2326896.19      7079537.38      2327260.74      7079219.69
      2327219.08      7077875.99
#Sta/Elev= 30
  3702.5  698.53  3723.7  696.03  3731.3  696.63    3738  695.05  3745.6  695.68
  3752.2  694.18  3915.5  693.12  3936.4  691.18  3979.1  693.66    4000  690.85
  4021.8  690.73  4042.7  692.14  4071.2  691.61  4077.8  689.84  4106.3  690.36
    4182  687.96  4425.9  684.91    4806  683.37  4856.1  681.59  4886.1  682.04
  4946.1  680.36  4956.1  678.72    4960     677  4961.7   676.5  4972.3     677
  4986.1   681.5  4996.1  682.92  5106.2  683.61  5371.4  695.81  5530.4   699.7
#Mann= 3 ,-1 , 0
  3702.5     .05       0    4960    .033       0  4972.3     .05       0
Bank Sta=4960,4972.3
XS Rating Curve= 0 ,0
Exp/Cntr=0.3,0.1

Type RM Length L Ch R = 1 ,21894   ,242,242,242
BEGIN DESCRIPTION:
Trail Creek 37.0
END DESCRIPTION:
XS GIS Cut Line= 3
      2328114.93      7079844.72      2327453.45       7078974.9
      2327411.83      7077923.89
#Sta/Elev= 30
  3247.3  695.63  3290.9  696.43  3304.1  695.75  3312.3  693.69  3333.2  693.29
  3341.2  694.01  3347.7  693.02  3391.3  692.08  4032.1  687.25  4239.7   684.3
    4345  684.31    4425  682.98  4555.1  682.77  4655.2  681.63  4915.4  681.64
  4965.5  680.42  4975.5  679.69  4985.5  677.54  4999.3  675.78    5001  675.28
  5011.7  675.78  5015.5  677.28  5035.5  682.23  5065.5  683.04  5125.6  686.83
  5215.7  693.77  5245.7  697.09  5265.7  697.44  5315.7   700.7  5391.9  702.43
#Mann= 3 ,-1 , 0
  3247.3     .05       0  4999.3    .033       0  5011.7     .05       0
Bank Sta=4999.3,5011.7
XS Rating Curve= 0 ,0
Exp/Cntr=0.3,0.1

Type RM Length L Ch R = 1 ,21652   ,423,423,423
BEGIN DESCRIPTION:
Trail Creek 36.0
END DESCRIPTION:
XS GIS Cut Line= 3
      2328521.13      7079782.15        2327629.        7078210.
      2327479.02      7078010.03
#Sta/Elev= 30
  3192.6  695.89  3209.7  695.65  3218.1  694.44  3241.1  693.71    3379  690.89
  3839.9   685.6  4399.6  682.78  4566.8  679.72    4701  678.52  4889.9   678.9
  4933.2  680.48  4942.8  680.27  4947.8  679.15  4954.8  676.85  4964.9  676.51
  5003.4  677.47  5007.5  675.62  5007.6  673.36  5009.3  672.86    5020  673.36
  5028.4  673.97  5036.7  677.56  5050.2  679.37  5086.7  678.46  5107.5  679.47
  5136.7  684.21  5142.9  686.72  5157.4  690.34  5186.7  694.58  5250.2  699.12
#Mann= 5 ,-1 , 0
  3192.6     .05       0  4947.8     .12       0  5007.6     .07       0
    5020     .12       0  5157.4     .05       0
Bank Sta=5007.6,5020
XS Rating Curve= 0 ,0
Exp/Cntr=0.3,0.1

Type RM Length L Ch R = 1 ,21229   ,464,464,464
BEGIN DESCRIPTION:
Trail Creek 35.0
END DESCRIPTION:
XS GIS Cut Line= 3
      2328719.07      7079526.97        2327829.        7077860.
      2327677.39      7077605.09
#Sta/Elev= 30
  3114.6  690.99    3313   687.8  3806.5  683.79  4014.7  680.74  4052.1  681.47
  4250.5  679.63  4494.2  680.38  4656.3  679.07  4760.4   676.1  4766.3  677.54
  4782.3  676.72  4798.6   674.3  4902.3  677.47  4914.1  676.55  4990.5  675.81
  5017.9  673.52  5021.4  670.75  5023.1  670.25  5033.8  670.75  5049.1  673.91
  5062.5  678.72  5070.5   680.2  5076.4  683.12    5092  687.14  5097.8  689.96
  5102.5  690.17  5113.4  691.34  5150.4  701.04  5156.2  701.57  5300.9   704.5
#Mann= 5 ,-1 , 0
  3114.6     .05       0  4914.1     .12       0  5021.4     .07       0
  5033.8     .12       0  5102.5     .05       0
Bank Sta=5021.4,5033.8
XS Rating Curve= 0 ,0
Exp/Cntr=0.3,0.1

Type RM Length L Ch R = 1 ,20765   ,445,445,445
BEGIN DESCRIPTION:
Trail Creek 34.0
END DESCRIPTION:
XS GIS Cut Line= 3
        2329179.      7079609.99        2328279.        7077810.
      2328198.24      7077318.65
#Sta/Elev= 30
  2983.3  695.03  3220.9  689.51  3438.9  686.01  3855.4  681.92  4109.7  681.06
  4324.9  678.42  4489.8   675.1  4629.6  676.93  4772.1  676.13  4906.3  673.28
  4942.6  673.21    4965  674.81  4973.4  674.27  4981.8  671.38  4986.7  667.17
  4988.4  666.67  4999.3  667.17  5023.8  671.59  5056.6  672.59  5076.8  675.88
  5097.1  674.55  5151.4  676.47  5178.2  679.22  5198.4   682.6  5212.6  685.09
  5218.7  687.92  5279.5  692.68  5360.6  696.86  5401.4  697.74  5493.7  697.63
#Mann= 3 ,-1 , 0
  2983.3     .05       0  4986.7    .033       0  4999.3     .05       0
Bank Sta=4986.7,4999.3
XS Rating Curve= 0 ,0
Exp/Cntr=0.3,0.1

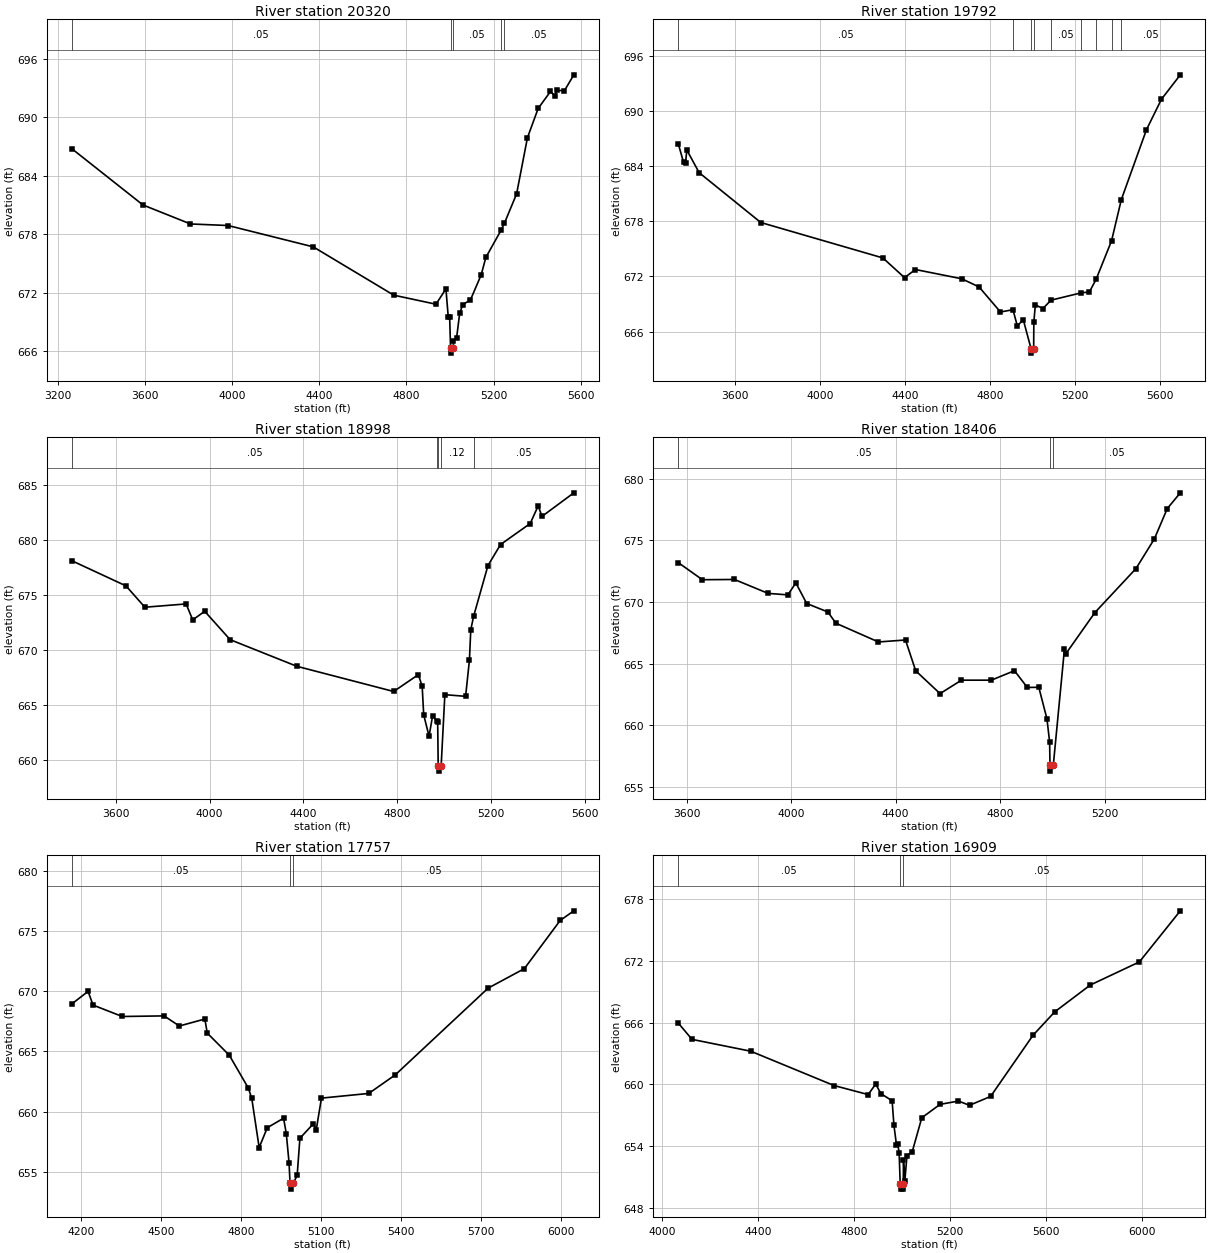
Type RM Length L Ch R = 1 ,20320   ,528,528,528
BEGIN DESCRIPTION:
Trail Creek 33.0
END DESCRIPTION:
XS GIS Cut Line= 3
      2329609.68      7079120.71        2328679.        7077660.
      2328276.35      7077250.93
#Sta/Elev= 30
    3263  686.78  3589.9     681  3808.3  679.05    3981  678.89    4372   676.7
  4741.9  671.74  4935.8  670.81  4981.5  672.39    4992  669.54  4998.5  669.54
  5002.8  666.29  5004.5  665.79  5015.4  666.29  5016.2  666.99  5030.4  667.34
  5044.5  669.86  5058.7  670.77    5094  671.25  5143.5  673.83  5164.7  675.61
  5234.6   678.4  5250.4  679.14  5306.1  682.14  5355.7  687.89  5405.1  690.91
  5461.7  692.65    5483  692.17    5490  692.78  5525.4  692.72    5569  694.36
#Mann= 5 ,-1 , 0
    3263     .05       0  5002.8    .033       0  5015.4     .05       0
  5234.6     .12       0  5250.4     .05       0
Bank Sta=5002.8,5015.4
XS Rating Curve= 0 ,0
Exp/Cntr=0.3,0.1

Type RM Length L Ch R = 1 ,19792   ,794,794,794
BEGIN DESCRIPTION:
Trail Creek 32.0
END DESCRIPTION:
XS GIS Cut Line= 3
      2329984.73      7078849.95      2329161.78      7077500.94
      2328604.46      7076948.83
#Sta/Elev= 30
  3332.3  686.47  3357.2  684.45  3366.8  684.37  3372.7  685.78  3430.8  683.31
  3721.2  677.88  4296.2  674.02  4398.2  671.87  4449.2  672.76  4667.6  671.75
  4749.2  670.86  4849.9  668.13  4908.8  668.38  4929.3  666.62  4957.6  667.28
  4993.7  664.15  4995.5  663.65  5006.3  664.15  5007.1  667.01  5014.2  668.92
  5049.5   668.5  5088.1  669.42  5230.7  670.22  5268.7  670.31  5300.2  671.68
  5373.2  675.89  5419.1  680.37  5537.4  687.98  5608.1  691.31    5697  693.97
#Mann= 9 ,-1 , 0
  3332.3     .05       0  4908.8     .12       0  4993.7     .07       0
  5006.3     .12       0  5088.1     .05       0  5230.7     .12       0
  5300.2     .05       0  5373.2     .12       0  5419.1     .05       0
Bank Sta=4993.7,5006.3
XS Rating Curve= 0 ,0
Exp/Cntr=0.3,0.1

Type RM Length L Ch R = 1 ,18998   ,592,592,592
BEGIN DESCRIPTION:
Trail Creek 31.0
END DESCRIPTION:
XS GIS Cut Line= 3
      2330203.47      7078402.03      2329536.78      7076985.32
      2329271.18      7076474.94
#Sta/Elev= 30
  3412.3  678.09  3643.5   675.8    3724  673.86  3899.8  674.16  3928.1  672.71
  3979.2  673.49  4087.7  670.91  4372.2  668.49    4785   666.2  4890.3  667.73
  4906.6  666.67  4913.1  664.08  4935.9  662.13  4950.8  663.95  4970.2  663.53
  4972.7  663.47  4974.9  659.46  4976.6  658.96  4987.6  659.46  5003.3  665.91
  5091.8  665.76    5108  669.02  5113.9  671.81  5125.7  673.02    5187  677.64
  5240.8  679.56  5367.3  681.47  5401.2  683.07  5417.7  682.12  5553.4  684.26
#Mann= 5 ,-1 , 0
  3412.3     .05       0  4970.2     .12       0  4974.9     .07       0
  4987.6     .12       0  5125.7     .05       0
Bank Sta=4974.9,4987.6
XS Rating Curve= 0 ,0
Exp/Cntr=0.3,0.1

Type RM Length L Ch R = 1 ,18406   ,649,649,649
BEGIN DESCRIPTION:
Trail Creek 30.0
END DESCRIPTION:
XS GIS Cut Line= 3
       2330297.2      7078110.32      2329969.08      7076594.69
      2329729.03      7076310.03
#Sta/Elev= 30
  3567.2  673.19  3659.6   671.8  3782.4  671.82  3911.7  670.69    3987  670.57
  4017.7  671.54  4059.3  669.87  4140.5  669.18  4171.2  668.27  4334.1  666.75
  4437.7  666.91  4476.7  664.41    4570  662.56  4652.1  663.65  4766.8  663.65
    4855  664.42  4904.2  663.06  4948.3  663.07  4979.5  660.51  4989.7  658.64
  4991.1  656.77  4992.9  656.27  5003.9  656.77  5046.7  666.21  5051.8  665.79
  5163.3  669.14  5320.3   672.7  5390.9  675.11  5440.3  677.57  5490.3  678.85
#Mann= 3 ,-1 , 0
  3567.2     .05       0  4991.1    .033       0  5003.9     .05       0
Bank Sta=4991.1,5003.9
XS Rating Curve= 0 ,0
Exp/Cntr=0.3,0.1

Type RM Length L Ch R = 1 ,17757   ,848,848,848
BEGIN DESCRIPTION:
Trail Creek 29.0
END DESCRIPTION:
XS GIS Cut Line= 3
      2330729.48      7077730.07      2330552.41      7076797.82
      2329828.46      7076209.29
#Sta/Elev= 30
  4165.3  668.95  4226.4     670    4245  668.86  4354.6  667.91  4511.3  667.96
  4568.6  667.12  4664.1   667.7  4673.1  666.53  4755.7  664.69    4827  661.96
    4840  661.09  4867.7  657.01  4898.2  658.66  4959.3  659.45  4969.5  658.14
  4979.7  655.75  4983.4  654.05  4985.2  653.55  4996.2  654.05  5010.2  654.71
  5020.4  657.78  5071.3     659  5081.5  658.47  5101.2  661.12  5278.5  661.51
  5377.6  663.05  5725.9  670.27  5861.7  671.89    5996   675.9  6047.2   676.7
#Mann= 3 ,-1 , 0
  4165.3     .05       0  4983.4     .04       0  4996.2     .05       0
Bank Sta=4983.4,4996.2
XS Rating Curve= 0 ,0
Exp/Cntr=0.3,0.1

Type RM Length L Ch R = 1 ,16909   ,809,809,809
BEGIN DESCRIPTION:
Trail Creek 28.0
END DESCRIPTION:
XS GIS Cut Line= 4
      2331281.58      7077256.16      2331140.95      7076568.65
      2330651.37      7076360.32      2329813.42      7076167.75
#Sta/Elev= 30
  4067.9  665.97  4125.2  664.38  4370.2  663.23  4717.2   659.9  4859.9  659.02
  4891.3  660.04    4913  659.11  4959.8  658.42  4967.4  656.03    4978  654.12
  4983.5  654.21  4989.1  653.36  4993.5  650.34  4995.4  649.84  5004.6  649.84
  5006.4  650.34  5007.1  652.62  5012.6  650.61  5021.7  653.09  5043.5  653.46
  5083.5  656.77  5159.8  658.07  5236.2  658.39  5282.5  657.98  5370.5  658.84
    5547  664.77  5637.8  667.05  5786.4  669.66  5990.8   671.9  6161.5  676.86
#Mann= 3 ,-1 , 0
  4067.9     .05       0  4993.5    .033       0  5006.4     .05       0
Bank Sta=4993.5,5006.4
XS Rating Curve= 0 ,0
Exp/Cntr=0.3,0.1

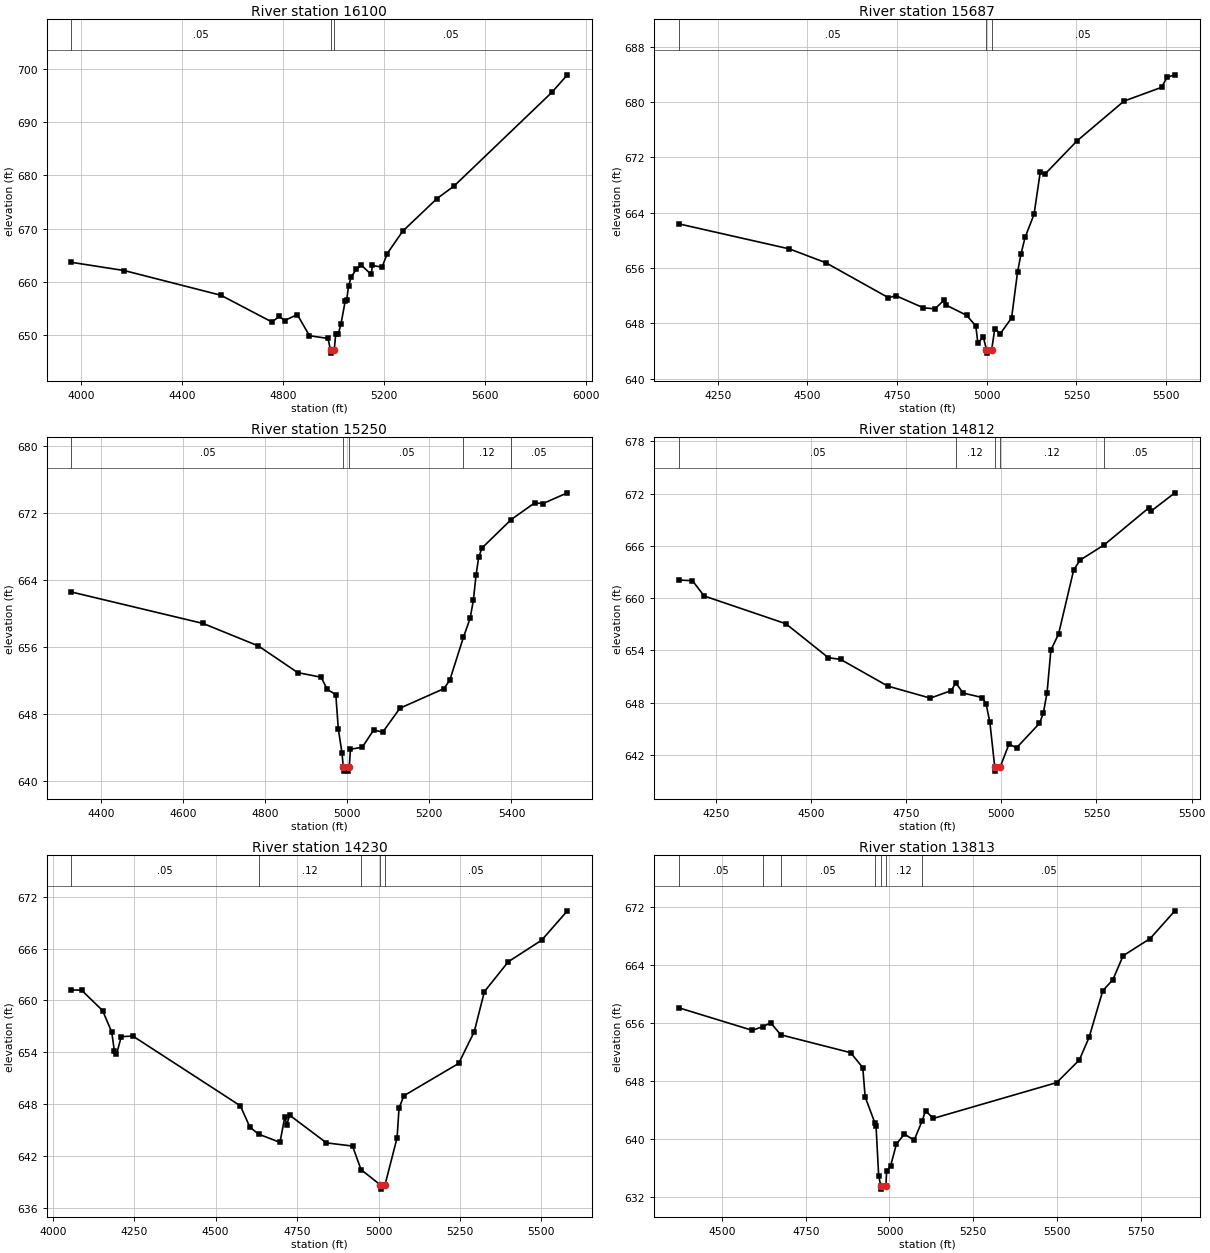
Type RM Length L Ch R = 1 ,16100   ,413,413,413
BEGIN DESCRIPTION:
Trail Creek 27.0
END DESCRIPTION:
XS GIS Cut Line= 3
      2331278.12      7077047.71       2331391.5      7076108.93
      2331193.04      7075110.36
#Sta/Elev= 30
  3961.5  663.69  4170.7  662.15  4553.5  657.52  4754.9  652.52  4785.2  653.57
  4805.3  652.78  4855.7   653.9    4904  649.94  4977.4  649.43  4987.6  647.18
  4989.6  646.68    5002  647.18    5008  650.34  5018.2  650.32  5028.4  652.07
  5045.9  656.52    5051  656.55  5058.9  659.28  5069.1  660.92  5089.5  662.41
  5109.9  663.14  5148.2  661.43  5153.3   663.1  5191.5  662.79  5211.9  665.33
  5273.1  669.52    5409  675.64    5477     678  5864.1  695.55  5925.2  698.82
#Mann= 3 ,-1 , 0
  3961.5     .05       0  4987.6    .033       0    5002     .05       0
Bank Sta=4987.6,5002
XS Rating Curve= 0 ,0
Exp/Cntr=0.3,0.1

Type RM Length L Ch R = 1 ,15687   ,437,437,437
BEGIN DESCRIPTION:
Trail Creek 26.0
END DESCRIPTION:
XS GIS Cut Line= 3
      2331427.79      7076970.55      2331681.74      7076249.52
       2331881.2      7075664.75
#Sta/Elev= 30
  4142.2  662.37  4450.2  658.75  4551.6  656.75  4725.9   651.7  4747.1  651.98
  4823.1  650.24  4855.8  650.08  4881.5  651.38  4886.8  650.63  4943.9  649.15
  4969.5  647.62  4975.2  645.19  4990.7  645.97  4999.3  644.18  5001.3  643.68
  5013.8  644.18  5022.4  647.19  5037.9   646.5  5069.2  648.76  5085.8  655.35
  5095.3  657.97  5106.9  660.42  5131.9  663.75  5149.2  669.88  5163.2  669.62
    5252  674.39  5382.6  680.13  5487.3  682.12  5502.7  683.58  5524.5  683.93
#Mann= 3 ,-1 , 0
  4142.2     .05       0  4999.3    .033       0  5013.8     .05       0
Bank Sta=4999.3,5013.8
XS Rating Curve= 0 ,0
Exp/Cntr=0.3,0.1

Type RM Length L Ch R = 1 ,15250   ,438,438,438
BEGIN DESCRIPTION:
Trail Creek 25.0
END DESCRIPTION:
XS GIS Cut Line= 3
      2331500.37      7077065.77        2331879.        7076510.
      2332212.35      7076090.77
#Sta/Elev= 30
  4328.1  662.57  4648.9  658.81  4783.7  656.12  4879.3  652.94  4936.2  652.39
  4951.2  650.95  4972.1   650.3  4978.2  646.21  4987.1  643.37  4990.3  641.67
  4992.3  641.17  5002.9  641.17  5004.9  641.67  5007.8  643.78  5036.6  644.03
  5064.5   646.1  5086.3  645.82  5128.4  648.69  5235.3  651.02  5249.7  652.03
  5283.1  657.18  5299.3  659.42  5307.2  661.58  5313.8  664.61  5320.1  666.71
  5328.2  667.83  5399.5  671.23  5456.3  673.21  5477.1  673.14  5536.2  674.42
#Mann= 5 ,-1 , 0
  4328.1     .05       0  4990.3    .033       0  5004.9     .05       0
  5283.1     .12       0  5399.5     .05       0
Bank Sta=4990.3,5004.9
XS Rating Curve= 0 ,0
Exp/Cntr=0.3,0.1

Type RM Length L Ch R = 1 ,14812   ,582,582,582
BEGIN DESCRIPTION:
Trail Creek 24.0
END DESCRIPTION:
XS GIS Cut Line= 3
      2331949.29      7077278.99      2332275.82      7076630.45
      2332307.55      7076054.73
#Sta/Elev= 30
  4153.3  662.07  4188.7  661.99  4219.3  660.24  4434.1  657.05  4545.7  653.15
  4577.6  652.96  4701.9  649.89  4813.5  648.51  4868.7  649.38  4880.3  650.26
  4899.9  649.09    4950  648.58    4960  647.85    4970  645.72  4982.7  640.63
  4984.7  640.13  4997.3  640.63  5020.1  643.23  5040.1  642.81  5100.2  645.61
  5110.2  646.76  5120.2  649.13  5130.2  654.02  5150.3  655.86  5190.3  663.25
  5207.5  664.37  5270.6  666.12  5388.5  670.39  5393.5  669.98    5456  672.08
#Mann= 5 ,-1 , 0
  4153.3     .05       0  4880.3     .12       0  4982.7     .07       0
  4997.3     .12       0  5270.6     .05       0
Bank Sta=4982.7,4997.3
XS Rating Curve= 0 ,0
Exp/Cntr=0.3,0.1

Type RM Length L Ch R = 1 ,14230   ,417,417,417
BEGIN DESCRIPTION:
Trail Creek 23.0
END DESCRIPTION:
XS GIS Cut Line= 3
      2332144.28      7077337.95      2332742.92      7076494.41
       2332873.9       7076024.7
#Sta/Elev= 30
  4057.6  661.21  4088.7  661.18  4153.2  658.82    4181  656.36  4189.6  654.09
  4195.7  653.75  4210.5  655.81  4246.2  655.87  4575.9  647.81  4605.4  645.33
    4632  644.53  4697.6  643.58  4712.4  646.52  4718.5  645.61  4727.2  646.72
  4840.3  643.52  4920.3  643.15  4946.3  640.43  5005.2  638.67  5007.2  638.17
  5019.9  638.67  5056.9  644.09    5063  647.54  5077.8  648.97    5246  652.71
  5293.8  656.38  5324.9  661.01  5398.3  664.47  5500.9  666.97  5579.6  670.36
#Mann= 5 ,-1 , 0
  4057.6     .05       0    4632     .12       0  4946.3     .05       0
  5005.2    .033       0  5019.9     .05       0
Bank Sta=5005.2,5019.9
XS Rating Curve= 0 ,0
Exp/Cntr=0.3,0.1

Type RM Length L Ch R = 1 ,13813   ,509,509,509
BEGIN DESCRIPTION:
Trail Creek 22.0
END DESCRIPTION:
XS GIS Cut Line= 4
       2332647.7      7077514.73      2332774.67      7077034.07
      2332861.18      7076828.23      2332978.74       7076077.2
#Sta/Elev= 30
  4371.5  658.07  4590.2  654.97  4621.1  655.47  4645.3  656.01  4675.5  654.35
  4883.9  651.89  4920.2  649.83  4927.3  645.78  4956.1  642.24  4959.8  641.77
  4967.7  634.89  4973.8  633.57  4975.8  633.07  4989.3  633.57  4991.5  635.58
  5003.2  636.25  5020.6  639.29  5044.4  640.66  5073.6  639.82  5097.3  642.47
  5107.7  643.88  5130.6  642.82  5499.1  647.76  5566.9  650.89  5596.2  654.04
  5636.7  660.42  5667.1  661.96  5697.4  665.25  5778.4  667.63  5852.1  671.45
#Mann= 7 ,-1 , 0
  4371.5     .05       0  4621.1     .12       0  4675.5     .05       0
  4956.1     .12       0  4973.8     .07       0  4989.3     .12       0
  5097.3     .05       0
Bank Sta=4973.8,4989.3
XS Rating Curve= 0 ,0
Exp/Cntr=0.3,0.1

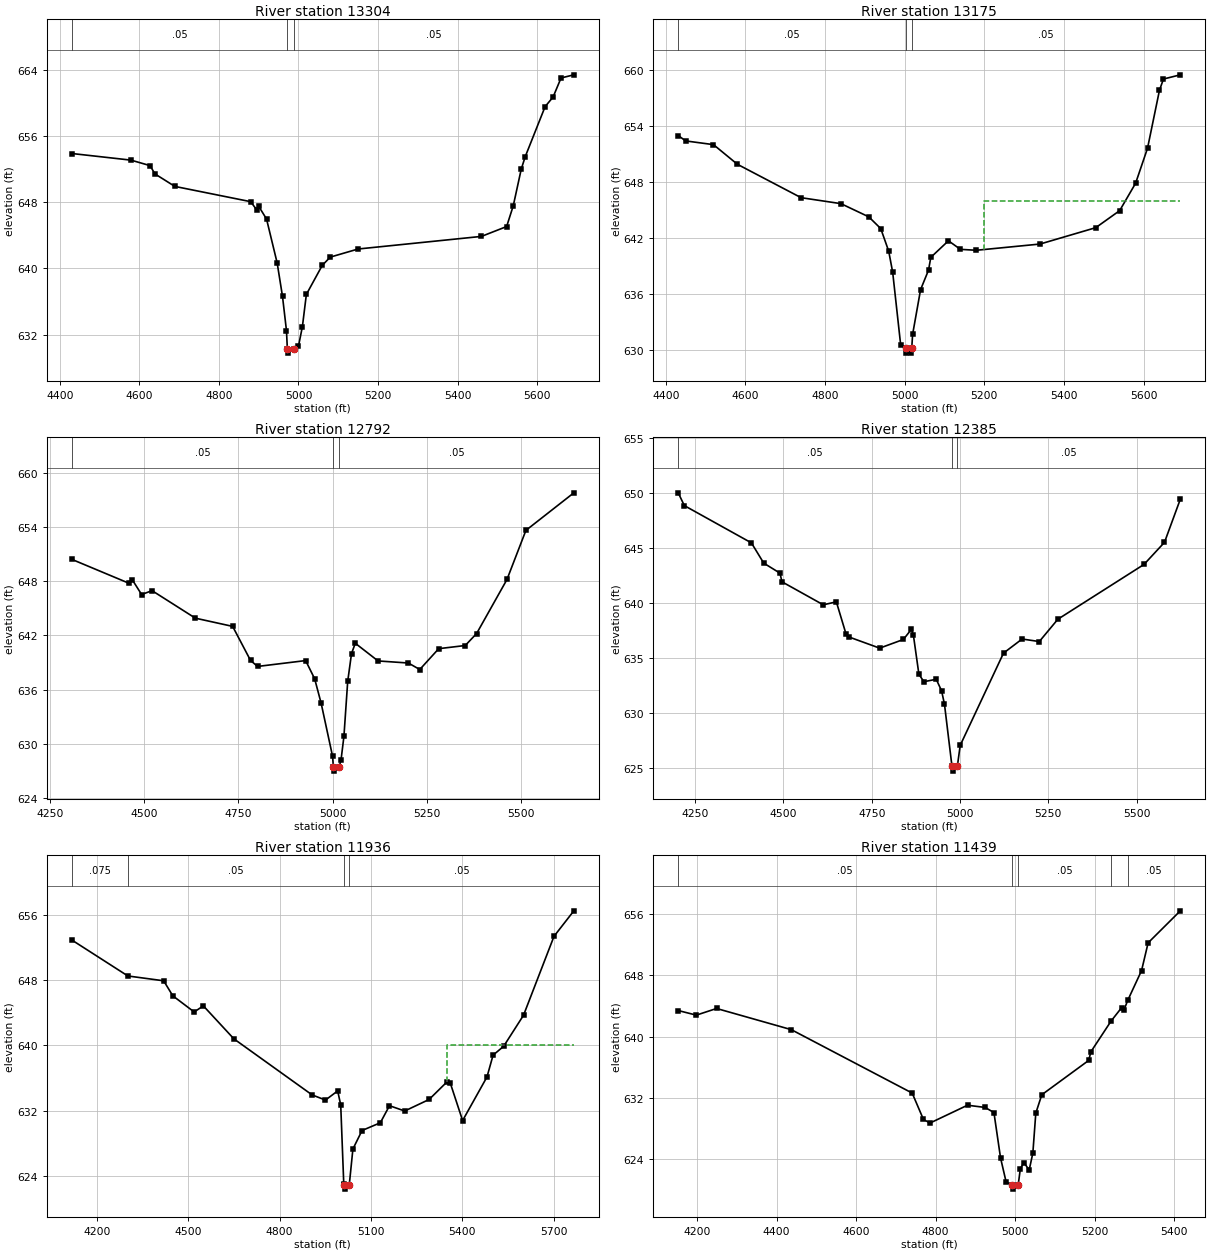
Type RM Length L Ch R = 1 ,13304   ,129,129,129
BEGIN DESCRIPTION:
Trail Creek 21.4
END DESCRIPTION:
XS GIS Cut Line= 3
      2333268.98      7077478.48      2333305.26      7076997.79
      2333278.05      7076217.82
#Sta/Elev= 30
    4430  653.87  4578.9  653.07  4626.8  652.41  4639.1  651.41  4689.2   649.9
  4879.8  648.06  4895.1  647.07  4900.1   647.5  4919.8  645.96  4946.5  640.66
  4959.9  636.63  4969.9   632.5  4972.1  630.29  4974.1  629.79  4987.7  630.29
  4999.9  630.59  5009.9  632.98  5019.9  636.87  5059.9  640.38  5079.9  641.37
    5150  642.35  5460.2  643.87  5523.5  645.06  5540.2  647.57  5560.2  651.98
  5570.2  653.48  5620.3  659.53  5640.3  660.68  5660.3  662.98  5692.5  663.36
#Mann= 3 ,-1 , 0
    4430     .05       0  4972.1    .033       0  4987.7     .05       0
Bank Sta=4972.1,4987.7
XS Rating Curve= 0 ,0
Exp/Cntr=0.3,0.1

Type RM Length L Ch R = 1 ,13175   ,383,383,383
BEGIN DESCRIPTION:
Trail Creek 21.0
END DESCRIPTION:
XS GIS Cut Line= 3
      2333418.63      7077478.48      2333432.24       7076843.6
       2333427.7      7076217.75
#Sta/Elev= 30
  4431.5     653    4450  652.42    4520  652.02    4580  649.91  4740.1  646.32
  4840.1  645.68  4910.1  644.26  4940.1     643  4960.1  640.57  4970.1  638.29
  4990.1  630.51  5002.3  630.12  5004.3  629.62  5015.9  629.62  5017.9  630.12
  5020.1  631.63  5040.1  636.44  5060.1  638.54  5065.8  639.91  5110.1  641.69
  5140.1  640.77  5180.1  640.67  5340.1  641.34  5480.1   643.1  5540.1  644.93
  5580.1  647.87  5610.1  651.64  5640.1  657.87  5650.1  659.07  5692.4  659.52
#Mann= 3 ,-1 , 0
  4431.5     .05       0  5002.3    .033       0  5017.9     .05       0
#XS Ineff= 2 , 0
       0                    5200       0     646
Permanent Ineff=
       F       F
Bank Sta=5002.3,5017.9
XS Rating Curve= 0 ,0
Exp/Cntr=0.3,0.1

Type RM Length L Ch R = 1 ,12792   ,407,407,407
BEGIN DESCRIPTION:
Trail Creek 20.0
END DESCRIPTION:
XS GIS Cut Line= 3
      2333590.97      7077523.81       2333776.9      7076907.09
      2333849.31      7076223.65
#Sta/Elev= 30
  4308.5  650.43  4460.7  647.77  4469.1  648.16  4493.7  646.53  4521.4  646.96
  4636.3  643.91  4735.1     643  4782.5  639.23  4801.1  638.56  4928.7  639.21
  4952.6  637.19  4969.8  634.48    5000  628.62  5002.2  627.46  5004.2  626.96
  5017.8  627.46  5022.6  628.22  5030.2  630.81  5040.2   636.9  5050.3  639.98
  5060.3  641.13  5120.7  639.17  5201.1  638.94  5231.3  638.22  5281.6  640.53
  5351.9  640.88  5382.1  642.21  5462.6   648.2  5512.8  653.64  5639.9   657.8
#Mann= 3 ,-1 , 0
  4308.5     .05       0  5002.2    .033       0  5017.8     .05       0
Bank Sta=5002.2,5017.8
XS Rating Curve= 0 ,0
Exp/Cntr=0.3,0.1

Type RM Length L Ch R = 1 ,12385   ,449,449,449
BEGIN DESCRIPTION:
Trail Creek 19.0
END DESCRIPTION:
XS GIS Cut Line= 3
      2333754.24      7077628.11      2334312.02      7076689.41
      2334139.69      7076408.24
#Sta/Elev= 30
  4202.2  650.05  4219.4  648.89  4409.4   645.5  4444.3  643.66  4490.2  642.75
    4496  641.96  4612.9  639.87  4649.9  640.14  4677.1  637.24  4686.9  636.93
  4772.6  635.93  4839.8  636.72  4862.3  637.64  4868.1  637.11  4883.7  633.55
  4897.9  632.88  4932.8   633.1  4947.9  632.05  4956.1  630.83  4977.1  625.25
  4979.1  624.75  4992.8  625.25  5000.6  627.09  5123.3  635.48  5175.9  636.76
  5224.6  636.53  5277.2  638.56  5521.1  643.54  5579.1  645.55  5623.9  649.47
#Mann= 3 ,-1 , 0
  4202.2     .05       0  4977.1    .033       0  4992.8     .05       0
Bank Sta=4977.1,4992.8
XS Rating Curve= 0 ,0
Exp/Cntr=0.3,0.1

Type RM Length L Ch R = 1 ,11936   ,497,497,497
BEGIN DESCRIPTION:
Trail Creek 18.0
END DESCRIPTION:
XS GIS Cut Line= 3
      2334488.89      7077990.93      2334547.84      7077147.44
      2334570.51      7076344.91
#Sta/Elev= 30
  4117.4  652.91  4301.6   648.5  4419.1  647.91  4449.1  646.07  4519.3  644.09
  4549.4  644.84  4649.6   640.8  4906.5  633.93  4950.4   633.3  4990.4  634.42
  5000.4  632.71  5010.4  623.02  5012.5  622.89  5014.5  622.39  5028.4  622.89
  5040.4   627.3  5070.4  629.57  5130.5  630.52  5160.5  632.61  5210.5  631.96
  5290.5  633.37  5350.5  635.57  5360.5  635.34  5400.6  630.79  5480.6  636.13
  5500.6   638.8  5535.4  639.89  5600.6  643.69  5700.7  653.36  5765.8  656.48
#Mann= 4 ,-1 , 0
  4117.4    .075       0  4301.6     .05       0  5012.5    .033       0
  5028.4     .05       0
#XS Ineff= 2 , 0
       0                    5348       0     640
Permanent Ineff=
       F       F
Bank Sta=5012.5,5028.4
XS Rating Curve= 0 ,0
Exp/Cntr=0.3,0.1

Type RM Length L Ch R = 1 ,11439   ,455,455,455
BEGIN DESCRIPTION:
Trail Creek 17.0
END DESCRIPTION:
XS GIS Cut Line= 3
      2335119.25      7077564.65      2335010.41      7077015.93
      2334688.43      7076390.11
#Sta/Elev= 30
  4152.7   643.4  4198.2   642.8  4249.2  643.67  4437.2   640.9  4741.3   632.6
  4769.6  629.15  4786.2  628.68  4880.5  631.01  4924.8  630.72    4947  630.05
  4963.6  624.12  4977.4  621.02  4991.9  620.53  4993.9  620.03  5007.9  620.53
  5013.5  622.72  5022.4  623.49  5035.7  622.54  5044.9  624.75  5052.3  629.97
  5067.4  632.38  5185.3  636.87  5191.1  638.02  5241.8  642.03  5268.4  643.79
    5274  643.45  5283.5  644.72  5318.4  648.63  5334.9  652.26  5415.9  656.45
#Mann= 5 ,-1 , 0
  4152.7     .05       0  4991.9    .033       0  5007.9     .05       0
  5241.8     .12       0  5283.5     .05       0
Bank Sta=4991.9,5007.9
XS Rating Curve= 0 ,0
Exp/Cntr=0.3,0.1