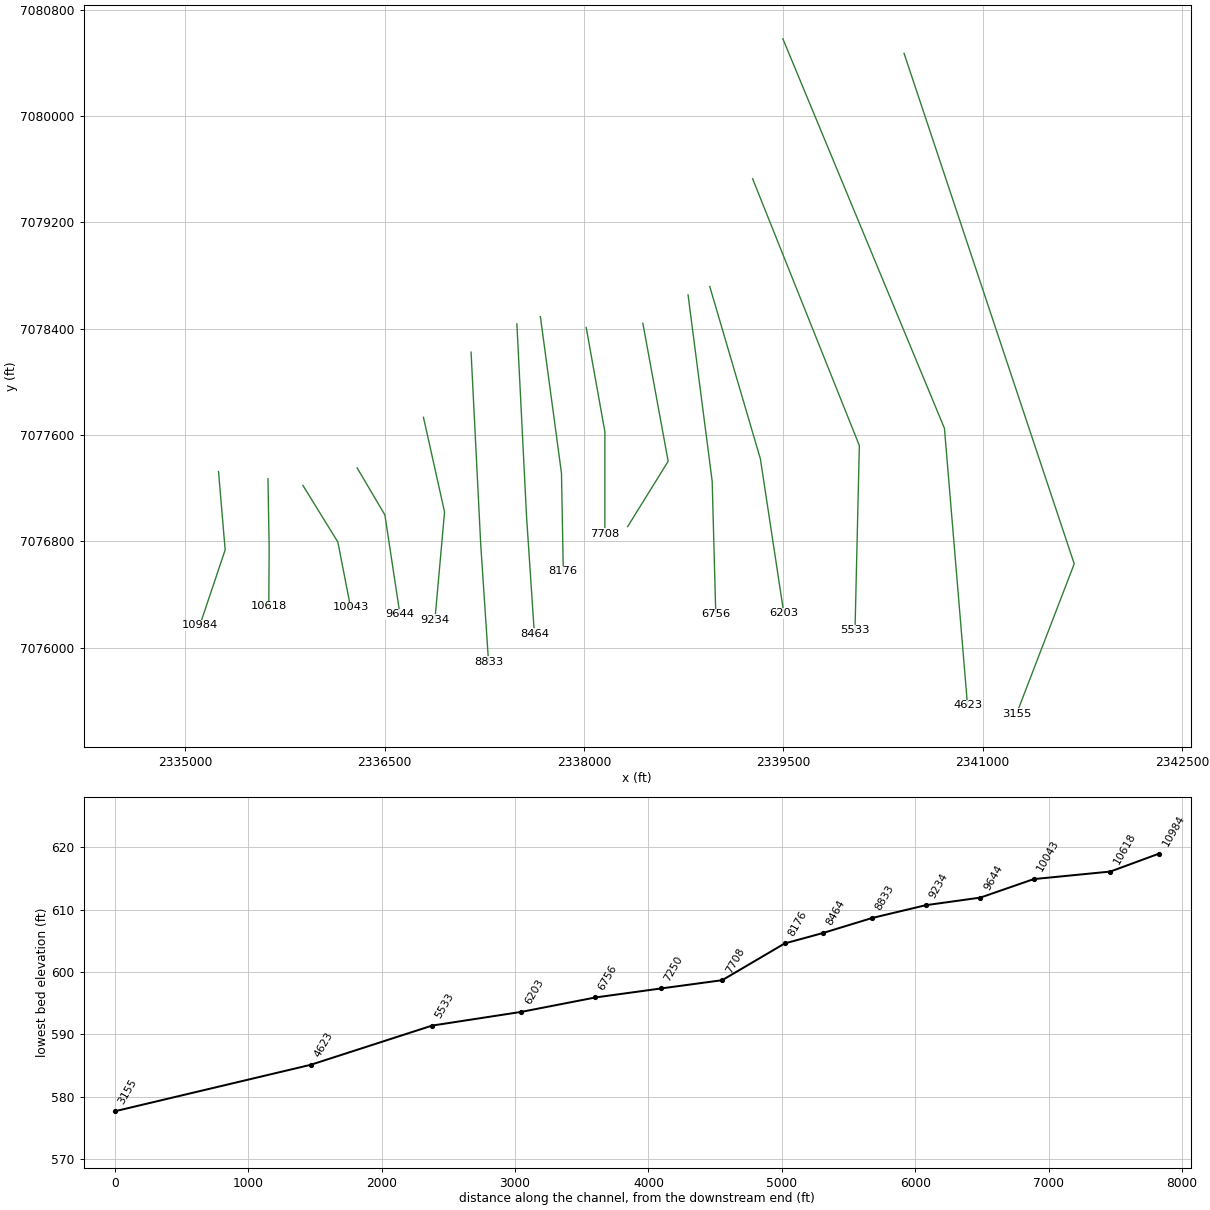
HEC-RAS study Trail Creek.prj: Trail Creek Base Level Engineering

--- Trail Creek.g01 (geometry) --- (continued)

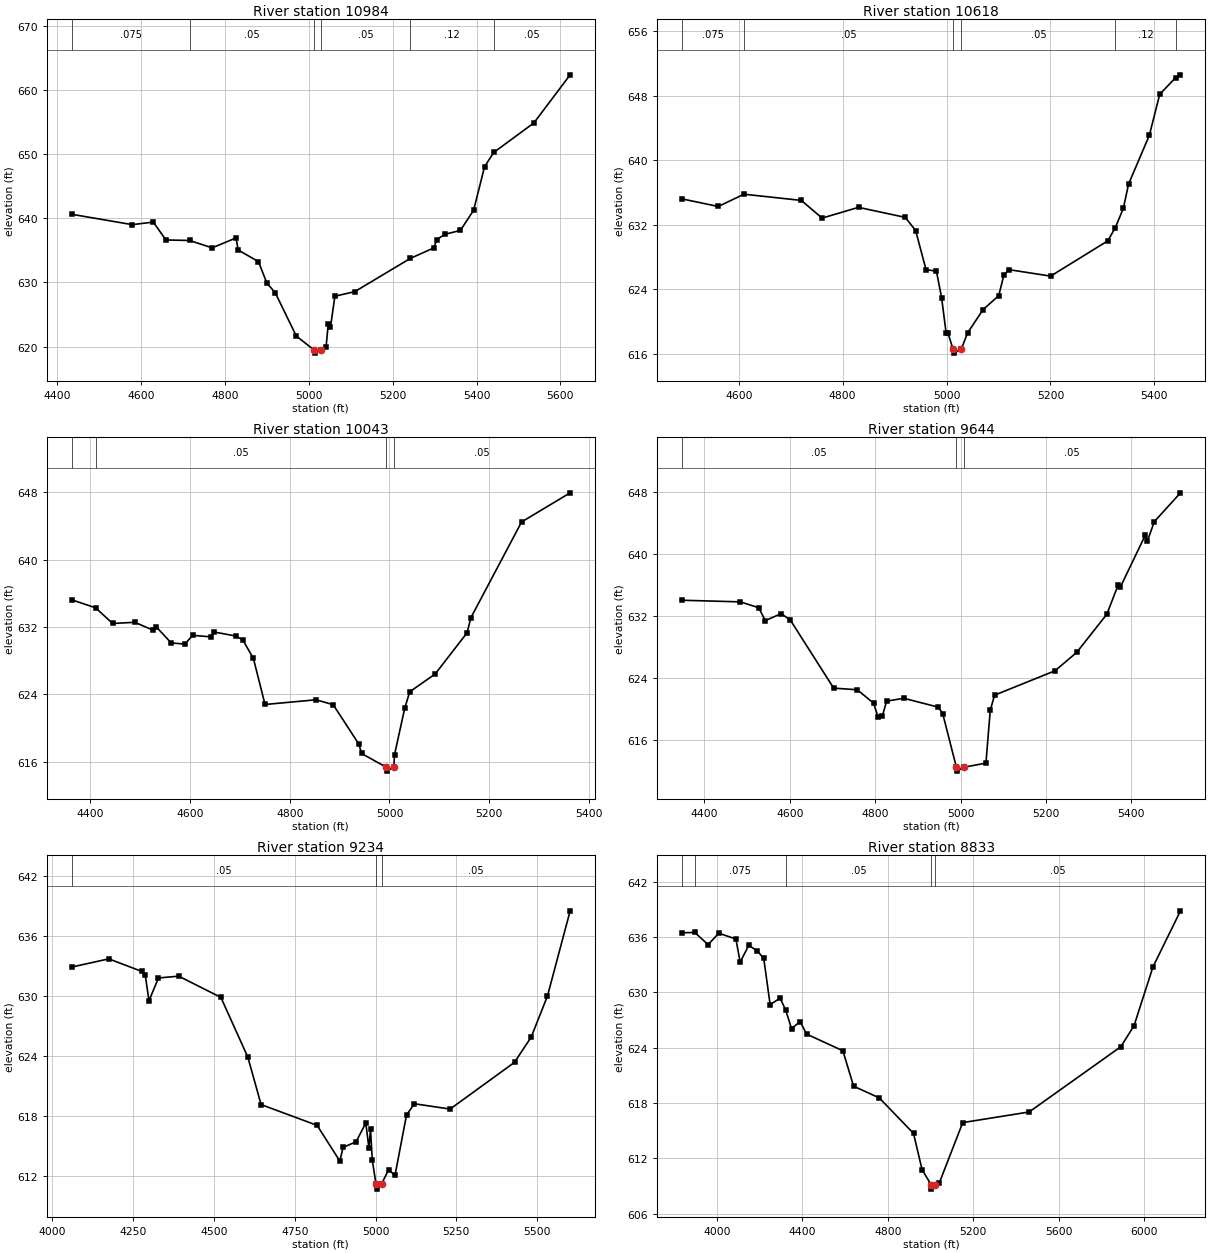
Type RM Length L Ch R = 1 ,10984   ,366,366,366
BEGIN DESCRIPTION:
Trail Creek 16.0
END DESCRIPTION:
XS GIS Cut Line= 3
      2335250.76      7077324.32      2335300.65      7076734.76
      2335110.17      7076167.87
#Sta/Elev= 30
  4433.7  640.64  4578.5  639.02  4628.7  639.42  4658.8  636.63  4715.1  636.55
  4769.2   635.4  4826.2  636.95  4831.2  635.06  4879.6  633.25  4899.7   629.9
  4919.8  628.38  4969.9  621.64  5012.1  619.47  5014.1  618.97  5028.2  619.47
  5040.9  619.88  5046.2  623.59  5051.5  623.03    5062  627.85  5109.3  628.56
    5242  633.75  5298.4   635.4  5304.7  636.67  5324.7  637.52  5361.5  638.12
    5393  641.26  5419.2  648.07  5441.1  650.29  5536.8  654.89  5623.4   662.4
#Mann= 6 ,-1 , 0
  4433.7    .075       0  4715.1     .05       0  5012.1     .04       0
  5028.2     .05       0    5242     .12       0  5441.1     .05       0
Bank Sta=5012.1,5028.2
XS Rating Curve= 0 ,0
Exp/Cntr=0.3,0.1

Type RM Length L Ch R = 1 ,10618   ,575,575,575
BEGIN DESCRIPTION:
Trail Creek 15.0
END DESCRIPTION:
XS GIS Cut Line= 3
      2335622.63       7077269.9       2335631.7      7076757.43
        2335629.      7076309.99
#Sta/Elev= 30
  4490.5   635.2  4560.4  634.26    4610  635.78  4720.4  635.01  4760.4  632.82
  4830.5  634.15  4920.5  632.91  4940.5  631.28  4960.5  626.43  4980.5  626.25
  4990.5  622.98  4999.3  618.54    5003  618.54  5012.4  616.59  5014.4  616.09
  5028.5  616.59  5040.5  618.59  5070.5  621.49  5100.5  623.21  5110.5  625.78
  5120.5  626.43  5200.5  625.63  5310.5     630    5325  631.63  5340.5  634.04
  5350.5  637.03  5390.5  643.07  5410.5  648.15  5440.9  650.21  5450.5  650.57
#Mann= 6 ,-1 , 0
  4490.5    .075       0    4610     .05       0  5012.4    .033       0
  5028.5     .05       0    5325     .12       0  5440.9     .05       0
Bank Sta=5012.4,5028.5
XS Rating Curve= 0 ,0
Exp/Cntr=0.3,0.1

Type RM Length L Ch R = 1 ,10043   ,399,399,399
BEGIN DESCRIPTION:
Trail Creek 14.0
END DESCRIPTION:
XS GIS Cut Line= 3
      2335885.68      7077219.97      2336148.69      7076793.71
      2336243.82      7076304.45
#Sta/Elev= 30
  4362.8  635.25    4411  634.29    4445  632.43  4489.5  632.57  4526.2  631.63
  4532.1  632.06  4562.5  630.11    4590  629.99  4605.4  631.02  4642.1  630.84
    4648  631.42  4691.8  630.94  4705.9  630.48  4727.2  628.28  4750.5   622.8
  4852.6  623.36  4887.1  622.78  4938.8  618.07  4943.9  616.98  4992.5  615.38
  4994.5  614.88  5008.7  615.38  5010.1  616.84  5030.5  622.35  5040.6  624.31
  5091.6  626.43  5155.6  631.33  5162.9  633.09  5264.8   644.5  5362.1  647.96
#Mann= 4 ,-1 , 0
  4362.8    .075       0    4411     .05       0  4992.5    .035       0
  5008.7     .05       0
Bank Sta=4992.5,5008.7
XS Rating Curve= 0 ,0
Exp/Cntr=0.3,0.1

Type RM Length L Ch R = 1 ,9644    ,410,410,410
BEGIN DESCRIPTION:
Trail Creek 13.0
END DESCRIPTION:
XS GIS Cut Line= 3
      2336293.79      7077351.54      2336502.42      7076997.79
      2336615.79      7076249.52
#Sta/Elev= 30
  4347.4  633.97  4484.2  633.76  4527.1  633.01  4542.7  631.34  4579.8  632.24
  4601.3  631.41  4702.7  622.63  4758.1  622.42  4796.3  620.68  4806.4  618.95
  4816.5  618.98  4826.7  620.95  4867.1  621.32    4948  620.17  4958.1  619.34
  4990.1  612.42  4992.1  611.92  5007.1  612.42  5059.3  612.95  5069.4  619.76
  5079.5  621.72  5221.1  624.87  5271.7  627.23  5342.5  632.17  5368.6   635.9
  5373.7  635.62  5432.3  642.35  5437.4  641.61  5453.7  644.12  5514.9  647.83
#Mann= 3 ,-1 , 0
  4347.4     .05       0  4990.1    .033       0  5007.1     .05       0
Bank Sta=4990.1,5007.1
XS Rating Curve= 0 ,0
Exp/Cntr=0.3,0.1

Type RM Length L Ch R = 1 ,9234    ,401,401,401
BEGIN DESCRIPTION:
Trail Creek 12.0
END DESCRIPTION:
XS GIS Cut Line= 3
      2336792.66      7077732.41      2336951.38      7077020.46
        2336879.      7076210.01
#Sta/Elev= 30
  4059.2  632.89  4174.4  633.71  4276.8  632.45  4287.1  632.09  4298.8  629.52
    4328   631.8  4390.8  631.98  4521.3  629.86  4604.7  623.89  4645.7  619.15
  4819.2  617.07  4889.5   613.5  4899.5  614.87  4939.7  615.43  4969.8  617.31
  4979.4  614.82  4984.4  616.67  4989.9  613.57  5001.5   611.2  5003.5   610.7
  5018.5   611.2  5040.1  612.63  5060.2  612.07  5095.9  618.12  5120.4  619.23
  5230.8   618.7  5430.1  623.37  5481.8   625.9    5532  629.99  5602.3  638.51
#Mann= 3 ,-1 , 0
  4059.2     .05       0  5001.5    .033       0  5018.5     .05       0
Bank Sta=5001.5,5018.5
XS Rating Curve= 0 ,0
Exp/Cntr=0.3,0.1

Type RM Length L Ch R = 1 ,8833    ,369,369,369
BEGIN DESCRIPTION:
Trail Creek 11.6
END DESCRIPTION:
XS GIS Cut Line= 3
      2337150.91      7078222.27      2337223.48      7076775.57
       2337282.3      7075893.15
#Sta/Elev= 30
  3836.7  636.48  3897.1  636.51  3959.1  635.19  4009.2  636.43  4089.3   635.8
  4109.3  633.29  4149.4  635.11  4189.4  634.51  4219.5   633.7  4249.5  628.68
    4296  629.39  4322.4  628.08  4349.6  626.07  4389.7  626.85  4419.7  625.49
  4589.9  623.67    4640  619.83  4760.1  618.56  4920.3  614.71  4960.4  610.78
  5001.9  609.16  5003.9  608.66    5019  609.16  5040.5   609.3  5150.6  615.88
  5461.2  617.03  5890.8  624.12  5952.3   626.4  6041.1  632.79  6169.6  638.86
#Mann= 5 ,-1 , 0
  3836.7     .05       0  3897.1    .075       0  4322.4     .05       0
  5001.9    .033       0    5019     .05       0
Bank Sta=5001.9,5019
XS Rating Curve= 0 ,0
Exp/Cntr=0.3,0.1

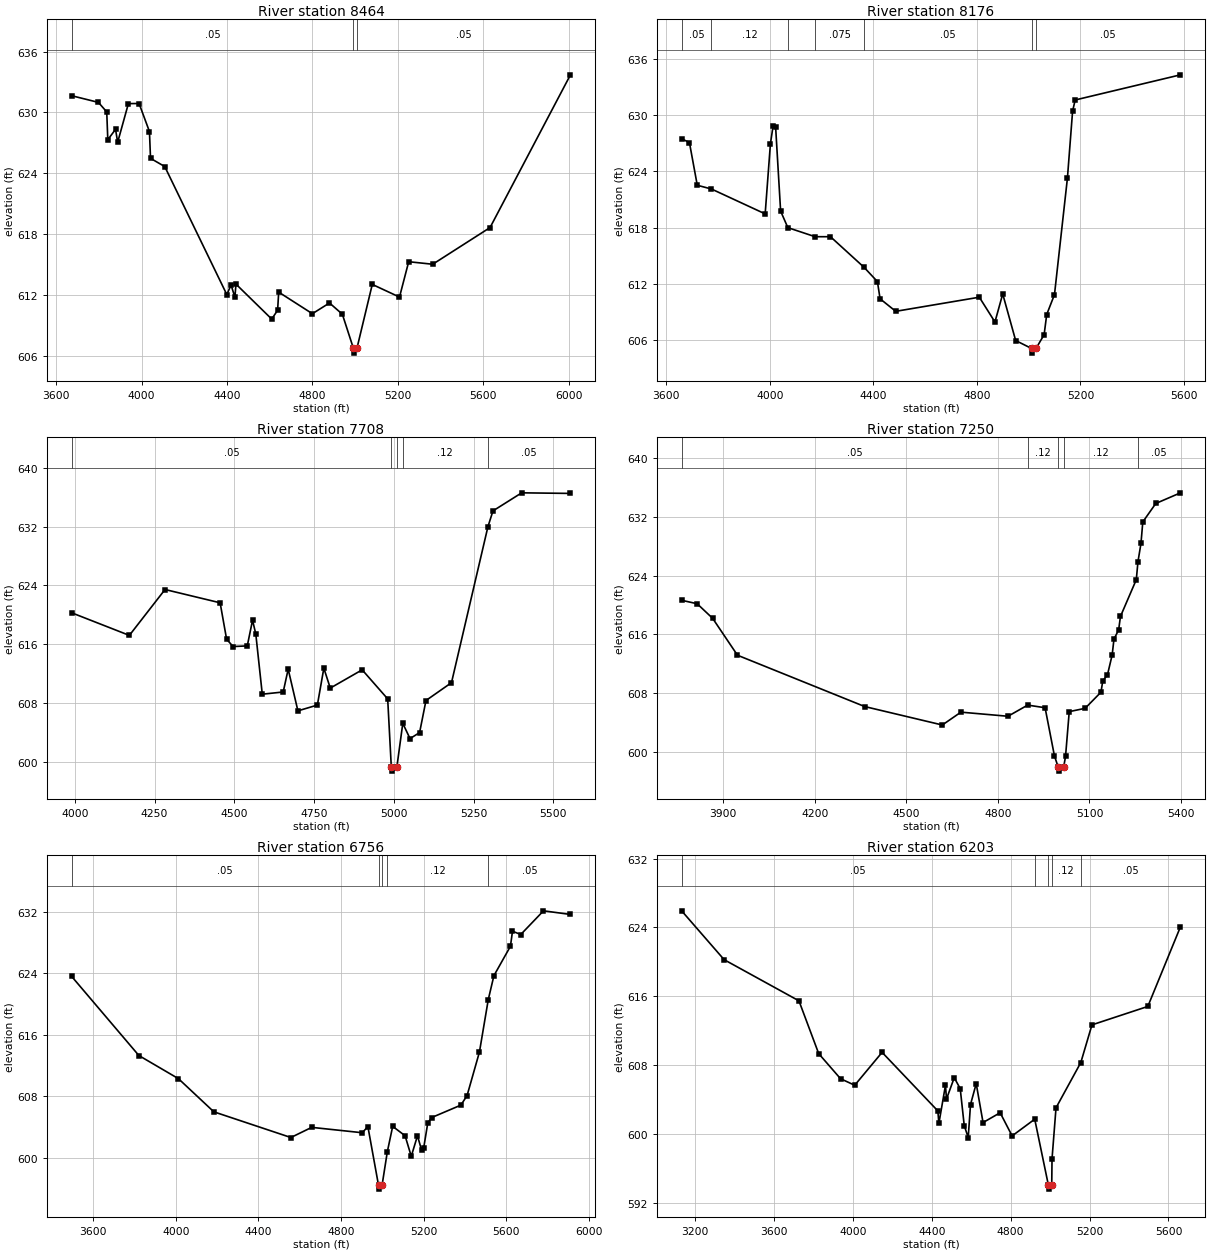
Type RM Length L Ch R = 1 ,8464    ,288,288,288
BEGIN DESCRIPTION:
Trail Creek 11.4
END DESCRIPTION:
XS GIS Cut Line= 3
      2337495.58      7078435.37      2337568.13      7076988.72
      2337627.07      7076104.65
#Sta/Elev= 30
  3672.7  631.65  3798.2  630.99  3837.1  630.05  3842.1  627.31  3878.3  628.33
  3888.3  627.06  3938.4  630.87  3988.5  630.88    4037  628.11    4042  625.47
  4108.6  624.66    4399  612.03    4419  612.97  4436.9  611.76  4441.9  613.06
  4609.2  609.61  4636.8  610.48  4641.8  612.27  4799.5  610.14  4879.6   611.2
  4939.7  610.09  4991.1  606.75  4993.1  606.25  5008.3  606.75  5079.8  613.03
  5207.2  611.78  5250.2  615.27  5362.6  615.02    5631  618.64  6007.2  633.71
#Mann= 3 ,-1 , 0
  3672.7     .05       0  4991.1    .033       0  5008.3     .05       0
Bank Sta=4991.1,5008.3
XS Rating Curve= 0 ,0
Exp/Cntr=0.3,0.1

Type RM Length L Ch R = 1 ,8176    ,468,468,468
BEGIN DESCRIPTION:
Trail Creek 11.0
END DESCRIPTION:
XS GIS Cut Line= 3
      2337672.43      7078489.84      2337831.16       7077310.7
      2337844.73       7076573.3
#Sta/Elev= 30
  3659.4  627.49  3689.5  627.09  3719.8  622.52  3774.6  622.12  3982.1  619.46
  4002.3  626.93  4012.4  628.81  4022.5  628.76  4041.8  619.76  4069.7  617.99
  4175.1  617.02  4234.4  617.02  4364.8  613.73  4415.8  612.22  4426.1  610.38
  4486.6  609.04  4809.5  610.55  4869.9   607.9  4899.9   610.9  4949.9  605.92
  5011.3  605.07  5013.3  604.57  5028.5  605.07  5059.9  606.54  5069.9   608.7
  5099.9  610.83  5149.9  623.28  5169.9  630.45  5179.9  631.64  5586.7  634.33
#Mann= 7 ,-1 , 0
  3659.4     .05       0  3774.6     .12       0  4069.7     .05       0
  4175.1    .075       0  4364.8     .05       0  5011.3    .033       0
  5028.5     .05       0
Bank Sta=5011.3,5028.5
XS Rating Curve= 0 ,0
Exp/Cntr=0.3,0.1

Type RM Length L Ch R = 1 ,7708    ,458,458,458
BEGIN DESCRIPTION:
Trail Creek 10.0
END DESCRIPTION:
XS GIS Cut Line= 3
      2338017.09       7078408.2      2338157.68      7077623.61
      2338157.68       7076857.2
#Sta/Elev= 30
  3990.1  620.26  4171.1  617.18  4282.9  623.43  4455.6  621.62  4475.9  616.66
  4496.2  615.66  4540.7  615.75  4557.2  619.25  4567.4  617.37  4587.7  609.17
  4653.3  609.47  4668.9  612.58  4699.4   606.9  4760.4  607.69  4780.7  612.72
  4800.8     610  4900.8  612.49  4980.8  608.53  4992.2  599.19  4994.2  598.69
  5009.4  599.19  5028.1   605.2  5050.8  603.12  5080.8  603.94  5100.8  608.31
  5180.8  610.74    5295  631.99  5310.8  634.14  5400.8   636.6  5553.6  636.52
#Mann= 5 ,-1 , 0
  3990.1     .05       0  4992.2    .033       0  5009.4     .05       0
  5028.1     .12       0    5295     .05       0
Bank Sta=4992.2,5009.4
XS Rating Curve= 0 ,0
Exp/Cntr=0.3,0.1

Type RM Length L Ch R = 1 ,7250    ,494,494,494
BEGIN DESCRIPTION:
Trail Creek 9.0
END DESCRIPTION:
XS GIS Cut Line= 3
      2338443.38      7078439.92      2338633.85       7077401.4
      2338329.01      7076910.02
#Sta/Elev= 30
    3764  620.63  3814.8  620.16  3865.6  618.17  3946.9  613.15  4363.8  606.16
  4617.9  603.65  4678.9   605.4    4833  604.84  4897.6  606.36  4954.6     606
  4985.3  599.43    4998  597.87    5000  597.37  5015.2  597.87  5021.6  599.38
  5033.7  605.47  5085.7  605.92  5137.7  608.12  5143.6  609.66  5158.9  610.48
  5174.3  613.18  5180.2  615.33  5195.6  616.61  5201.5  618.43  5253.4  623.44
  5258.8  625.87  5268.7  628.38  5274.7   631.3  5317.2  633.81  5398.1  635.26
#Mann= 5 ,-1 , 0
    3764     .05       0  4897.6     .12       0    4998     .07       0
  5015.2     .12       0  5258.8     .05       0
Bank Sta=4998,5015.2
XS Rating Curve= 0 ,0
Exp/Cntr=0.3,0.1

Type RM Length L Ch R = 1 ,6756    ,553,553,553
BEGIN DESCRIPTION:
Trail Creek 8.0
END DESCRIPTION:
XS GIS Cut Line= 3
      2338783.51      7078653.04      2338964.91      7077251.75
      2338992.12       7076249.5
#Sta/Elev= 30
  3495.7  623.58  3821.4  613.29    4013  610.28  4184.4  605.97  4557.5  602.63
  4658.4  603.95  4903.5  603.25  4930.4  604.06  4981.9  596.42  4983.9  595.92
  4999.1  596.42  5024.5  600.77  5050.5  604.08  5110.5  602.86  5140.5  600.19
  5170.5  602.85  5190.5     601  5200.5  601.25  5220.5  604.53  5239.7  605.23
  5380.6  606.84  5410.6  608.07  5470.6  613.74  5513.4  620.56  5540.7  623.67
  5620.7  627.49  5630.7  629.45  5670.7  629.02  5780.8   632.1  5911.3  631.63
#Mann= 5 ,-1 , 0
  3495.7     .05       0  4981.9    .033       0  4999.1     .05       0
  5024.5     .12       0  5513.4     .05       0
Bank Sta=4981.9,4999.1
XS Rating Curve= 0 ,0
Exp/Cntr=0.3,0.1

Type RM Length L Ch R = 1 ,6203    ,670,670,670
BEGIN DESCRIPTION:
Trail Creek 7.0
END DESCRIPTION:
XS GIS Cut Line= 3
      2338946.76      7078716.57       2339327.7      7077419.54
      2339504.22      7076256.37
#Sta/Elev= 30
  3132.4  625.93  3347.7  620.26    3727  615.48  3827.1  609.35  3937.7  606.44
  4009.6  605.68  4148.4   609.5    4431   602.7  4436.2  601.24  4469.6  605.68
  4474.8  604.08  4514.1  606.56  4544.4  605.28  4564.7     601  4584.9  599.61
  4596.5  603.44  4625.4  605.87  4660.1  601.35  4746.7  602.49  4807.4   599.8
    4922  601.74  4990.9  594.12  4992.9  593.62  5008.2  594.12  5009.7  597.14
  5029.9  603.06  5155.6  608.32    5212  612.69  5495.2  614.83  5660.7  624.08
#Mann= 5 ,-1 , 0
  3132.4     .05       0    4922     .12       0  4990.9     .07       0
  5008.2     .12       0  5155.6     .05       0
Bank Sta=4990.9,5008.2
XS Rating Curve= 0 ,0
Exp/Cntr=0.3,0.1

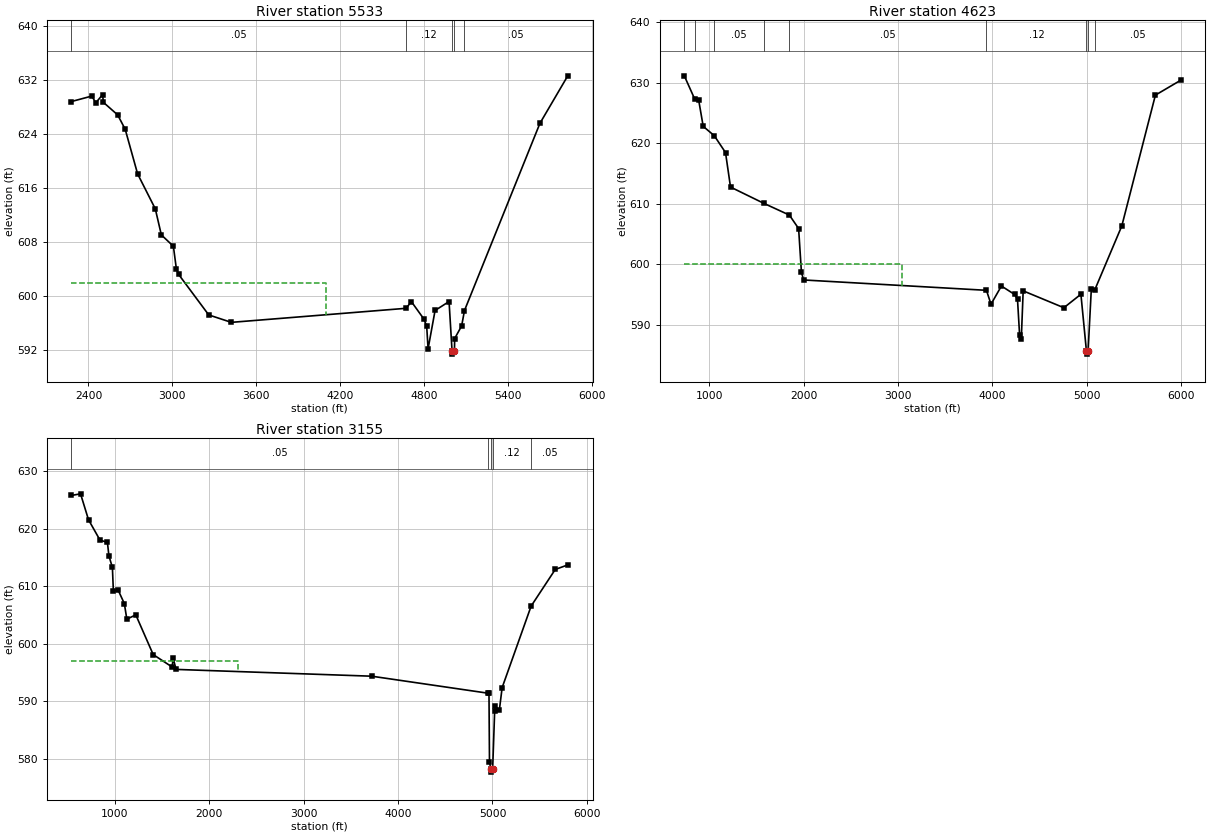
Type RM Length L Ch R = 1 ,5533    ,910,910,910
BEGIN DESCRIPTION:
Trail Creek 6.0
END DESCRIPTION:
XS GIS Cut Line= 3
      2339269.27      7079526.98      2340072.21      7077519.64
      2340039.66       7076130.8
#Sta/Elev= 30
  2278.5  628.79  2423.3  629.59  2452.9  628.61  2501.3  629.81  2506.7  628.67
    2609  626.81  2662.9  624.68  2751.7  618.08  2878.3  612.91  2921.5  609.06
  3007.6  607.38  3029.2  604.01  3045.2  603.21  3260.6  597.22  3422.2  596.12
  4673.6   598.2  4710.2   599.2  4800.2  596.61  4820.2  595.54  4830.2  592.21
  4880.2  597.88  4980.3   599.2  5001.6  591.92  5003.6  591.42    5019  591.92
  5020.3  593.73  5070.3  595.59  5090.6  597.87  5630.4  625.56  5829.7  632.59
#Mann= 5 ,-1 , 0
  2278.5     .05       0  4673.6     .12       0  5001.6     .07       0
    5019     .12       0  5090.6     .05       0
#XS Ineff= 2 , 0
       0    4100     602               0
Permanent Ineff=
       F       F
Bank Sta=5001.6,5019
XS Rating Curve= 0 ,0
Exp/Cntr=0.3,0.1

Type RM Length L Ch R = 1 ,4623    ,1468,1468,1468
BEGIN DESCRIPTION:
Trail Creek 5.0
END DESCRIPTION:
XS GIS Cut Line= 3
      2339497.12      7080579.55       2340712.4      7077649.85
      2340886.01      7075566.53
#Sta/Elev= 30
   734.6  631.15   846.7  627.24   887.1  627.12   934.8   622.8  1052.3  621.25
  1171.4  618.47  1224.5  612.76  1580.4  610.05  1848.5  608.13  1946.6   605.9
  1976.5  598.64  2000.3   597.4  3938.2  595.69  3986.5  593.39  4096.9   596.4
  4237.4     595  4267.5  594.21  4289.7   588.3  4307.6  587.59  4327.7   595.6
  4759.2  592.81  4939.8  595.04  4998.5  585.64  5000.5  585.14  5015.9  585.64
  5050.2  595.91  5085.2   595.7  5373.4  606.33  5729.7  627.96  5996.9  630.41
#Mann= 9 ,-1 , 0
   734.6     .05       0   846.7    .075       0  1052.3     .05       0
  1580.4    .075       0  1848.5     .05       0  3938.2     .12       0
  4998.5     .07       0  5015.9     .12       0  5085.2     .05       0
#XS Ineff= 2 , 0
       0    3040     600               0
Permanent Ineff=
       F       F
Bank Sta=4998.5,5015.9
XS Rating Curve= 0 ,0
Exp/Cntr=0.3,0.1

Type RM Length L Ch R = 1 ,3155    ,0,0,0
BEGIN DESCRIPTION:
Trail Creek 4.0
END DESCRIPTION:
XS GIS Cut Line= 3
      2340408.57      7080471.07      2341688.96      7076629.88
      2341255.63      7075503.21
#Sta/Elev= 30
   541.2  625.81   637.2  626.09   721.6  621.58   842.9  618.05   921.8  617.64
   937.7   615.3   974.6  613.29     985  609.12  1032.6  609.45  1101.1     607
  1127.5  604.29  1222.3  605.05  1406.7  598.14  1607.1  595.98  1617.5  597.51
  1649.1  595.56  3720.5  594.38  4954.4  591.42  4962.9  591.39  4968.3   579.4
  4984.2   578.2  4986.2   577.7  5001.7   578.2  5022.9  588.26  5029.3  589.14
  5072.2  588.42  5102.2  592.39  5409.3  606.57  5664.7  612.94  5797.3  613.73
#Mann= 5 ,-1 , 0
   541.2     .05       0  4954.4     .12       0  4984.2     .07       0
  5001.7     .12       0  5409.3     .05       0
#XS Ineff= 2 , 0
       0    2300     597               0
Permanent Ineff=
       F       F
Bank Sta=4984.2,5001.7
XS Rating Curve= 0 ,0
Exp/Cntr=0.3,0.1

Chan Stop Cuts=-1
Use User Specified Reach Order=0
Composite Channel Slope=5