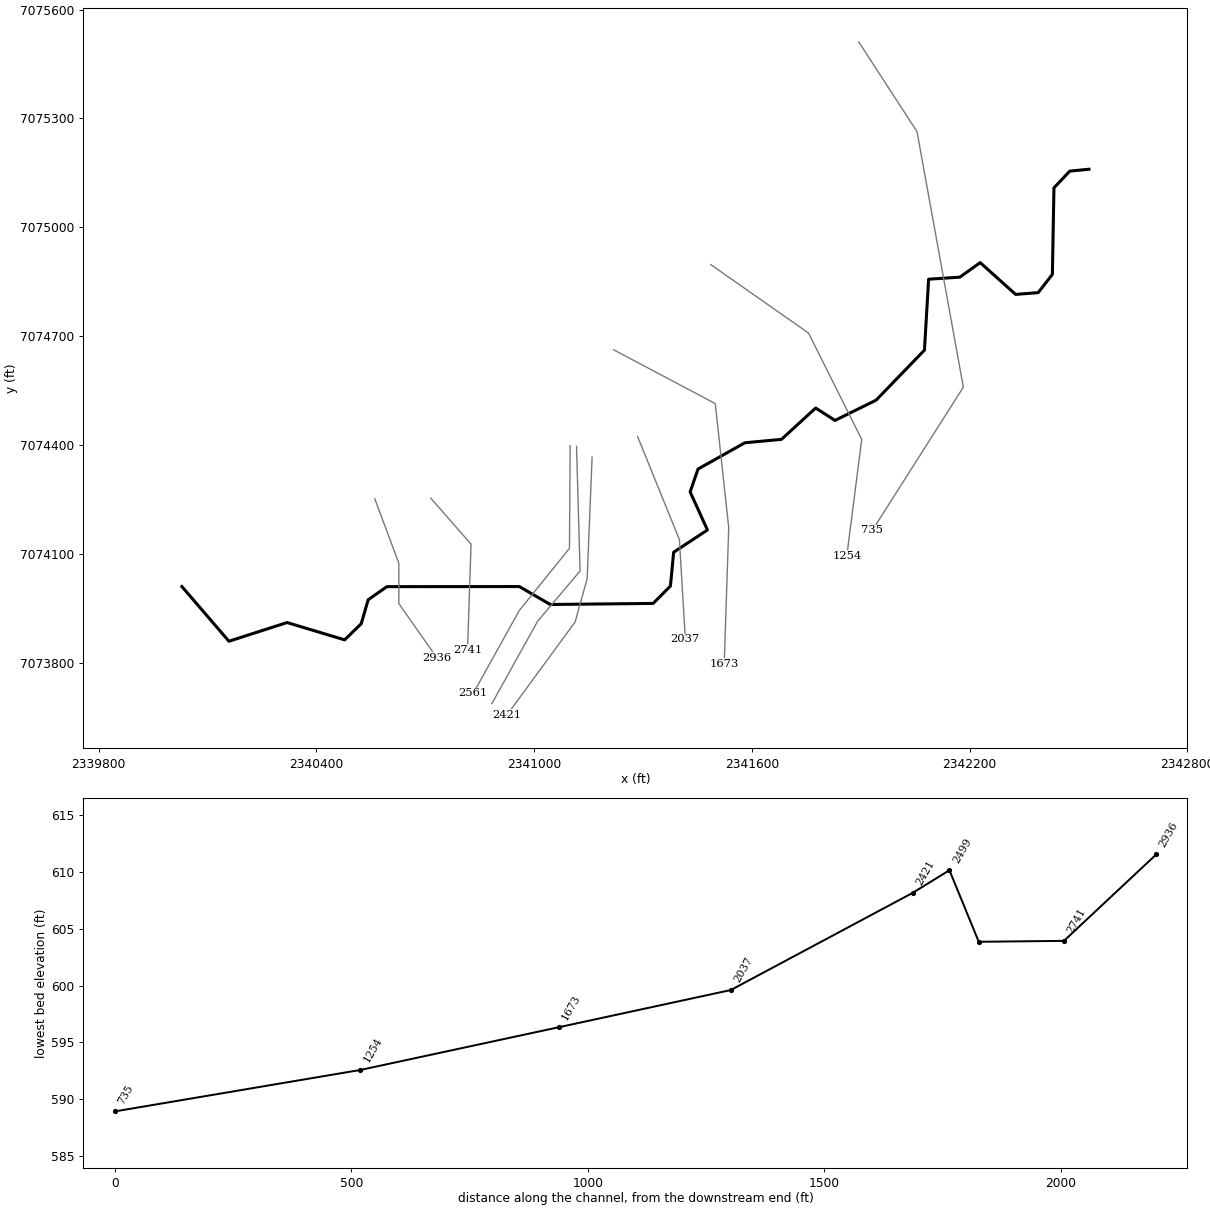
--- Trail Creek Tr 1.prj (project) ---

Proj Title=Trail Creek Tr 1 Base Level Engineering
Current Plan=p01
Default Exp/Contr=0.3,0.1
English Units
Geom File=g01
Flow File=f01
Plan File=p01
Y Axis Title=Elevation
X Axis Title(PF)=Main Channel Distance
X Axis Title(XS)=Station
BEGIN DESCRIPTION:
Trail Creek Tr 1
END DESCRIPTION:
DSS Export Rating Curves= 0
DSS Export Rating Curve Sorted= 0
DSS Export Volume Flow Curves= 0
DXF OffsetX= 0
DXF OffsetY= 0
DXF ScaleX= 1
DXF ScaleY= 10

--- Trail Creek Tr 1.p01 (plan) ---

Plan Title=Multiple Run
Program Version=4.10
Short Identifier=Multiple
Geom File=g01
Flow File=f01
Subcritical Flow
K Sum by GR= 0
Std Step Tol= 0.01
Critical Tol= 0.01
Num of Std Step Trials= 20
Max Error Tol= 0.3
Flow Tol Ratio= 0.001
Split Flow NTrial= 30
Split Flow Tol= 0.02
Split Flow Ratio= 0.02
Log Output Level= 0
Friction Slope Method= 1
Unsteady Friction Slope Method= 2
Unsteady Bridges Friction Slope Method= 1
Parabolic Critical Depth
Global Vel Dist= 1 , 1 , 1
Global Log Level= 0
CheckData=True
Encroach Param=-1 ,0,0, 0
BEGIN DESCRIPTION:
Multiple Run
END DESCRIPTION:
Computation Interval=1HOUR
Output Interval=1HOUR
Run HTab= 0
Run UNet= 0
Run PostProcess= 0
Run WQNet= 0
UNET Theta= 1
UNET Theta Warmup= 1
UNET ZTol= 0.02
UNET ZSATol= 0.05
UNET MxIter= 20
UNET MaxInSteps= 0
UNET DtIC= 0
UNET DtMin= 0
UNET MaxCRTS= 20
UNET WFStab= 2
UNET SFStab= 1
UNET WFX= 1
UNET SFX= 1
UNET DSS MLevel= 4
UNET DZMax Abort= 100
UNET Convert EG Bridges= 0
UNET Use Existing IB Tables=-1
UNET Froude Reduction=False
UNET Froude Limit= 1
UNET Froude Power= 10
UNET Time Slicing=0,0, 5
UNET Junction Losses=0
Instantaneous Interval=1HOUR
Write IC File= 0
Write IC File at Sim End=0
Echo Input=False
Echo Parameters=False
Echo Output=False
Write Detailed= 0
WQ AD Non Conservative
WQ ULTIMATE=-1
WQ Max Comp Step=1HOUR
WQ Output Interval=15MIN
WQ Output Selected Increments= 0
WQ Output face flow=0
WQ Output face velocity=0
WQ Output face area=0
WQ Output face dispersion=0
WQ Output cell volume=0
WQ Output cell surface area=0
WQ Output cell continuity=0
WQ Output cumulative cell continuity=0
WQ Output face conc=0
WQ Output face dconc_dx=0
WQ Output face courant=0
WQ Output face peclet=0
WQ Output face adv mass=0
WQ Output face disp mass=0
WQ Output cell mass=0
WQ Output cell source sink temp=0
WQ Output cell source sink nsm=0
WQ Output MaxMinRange=-1
WQ Daily Max Min Mean=-1
WQ Daily Range=0
WQ Daily Time=0
WQ Create Restart=0
WQ Fixed Restart=0
WQ System Summary=0
WQ Use Fixed Temperature=0
Sorting and Armoring Iterations= 10
XS Update Threshold= 0.02
Hydraulics Update Threshold= 0.02
Energy Slope Method= 1
Volume Change Method= 0
XS Weighting Method= 0
Number of US Weighted Cross Sections= 1
Number of DS Weighted Cross Sections= 1
Upstream XS Weight=0.25
Main XS Weight=0.5
Downstream XS Weight=0.25
Number of DS XS's Weighted with US Boundary= 1
Upstream Boundary Weight= 1
Weight of XSs Associated with US Boundary= 0
Number of US XS's Weighted with DS Boundary= 1
Downstream Boundary Weight= 0.5
Weight of XSs Associated with DS Boundary= 0.5
Sediment Output Level= 4
Mass or Volume Output= 0
Output Increment Type= 1
Profile and TS Output Increment= 10
XS Output Flag= 0
XS Output Increment= 10
Disregard all LS=0
Disregard all Conn=0
Disregard all Breaches=0
Disregard all Pumps=0

--- Trail Creek Tr 1.f01 (steady flow) ---

Flow Title=Multiple
Number of Profiles=7
Profile Names=10-year,25-year,50-year,1pct_min,100-year,1pct_plu,500-year
River Rch & RM= Trail Creek Tr 1,Reach-1,2936
     310     409     488     290     578    1154     813
Boundary for River Rch & Prof#=Trail Creek Tr 1,Reach-1,1
Up Type=0
Dn Type=3
Dn Slope=0.005
Boundary for River Rch & Prof#=Trail Creek Tr 1,Reach-1,2
Up Type=0
Dn Type=3
Dn Slope=0.005
Boundary for River Rch & Prof#=Trail Creek Tr 1,Reach-1,3
Up Type=0
Dn Type=3
Dn Slope=0.005
Boundary for River Rch & Prof#=Trail Creek Tr 1,Reach-1,4
Up Type=0
Dn Type=3
Dn Slope=0.005
Boundary for River Rch & Prof#=Trail Creek Tr 1,Reach-1,5
Up Type=0
Dn Type=3
Dn Slope=0.005
Boundary for River Rch & Prof#=Trail Creek Tr 1,Reach-1,6
Up Type=0
Dn Type=3
Dn Slope=0.005
Boundary for River Rch & Prof#=Trail Creek Tr 1,Reach-1,7
Up Type=0
Dn Type=3
Dn Slope=0.005

--- Trail Creek Tr 1.g01 (geometry) ---

Geom Title=Existing Conditions

River Reach=Trail Creek Tr 1,Reach-1
Reach XY= 30
      2340029.00      7074010.00      2340158.66      7073859.22
      2340318.95      7073910.77      2340477.58      7073863.04
      2340523.24      7073907.41      2340542.46      7073973.62
      2340594.03      7074009.67      2340958.97      7074009.93
      2341044.22      7073960.52      2341327.78      7073963.44
      2341375.46      7074011.32      2341384.30      7074104.51
      2341477.43      7074165.87      2341429.72      7074270.75
      2341451.55      7074333.84      2341580.58      7074406.17
      2341681.43      7074415.55      2341775.67      7074501.99
      2341828.91      7074467.77      2341942.21      7074523.61
      2342075.46      7074661.47      2342086.95      7074857.00
      2342173.01      7074862.60      2342229.09      7074902.67
      2342326.74      7074815.08      2342389.05      7074820.02
      2342428.01      7074870.24      2342432.37      7075108.74
      2342476.05      7075154.87      2342529.00      7075160.00

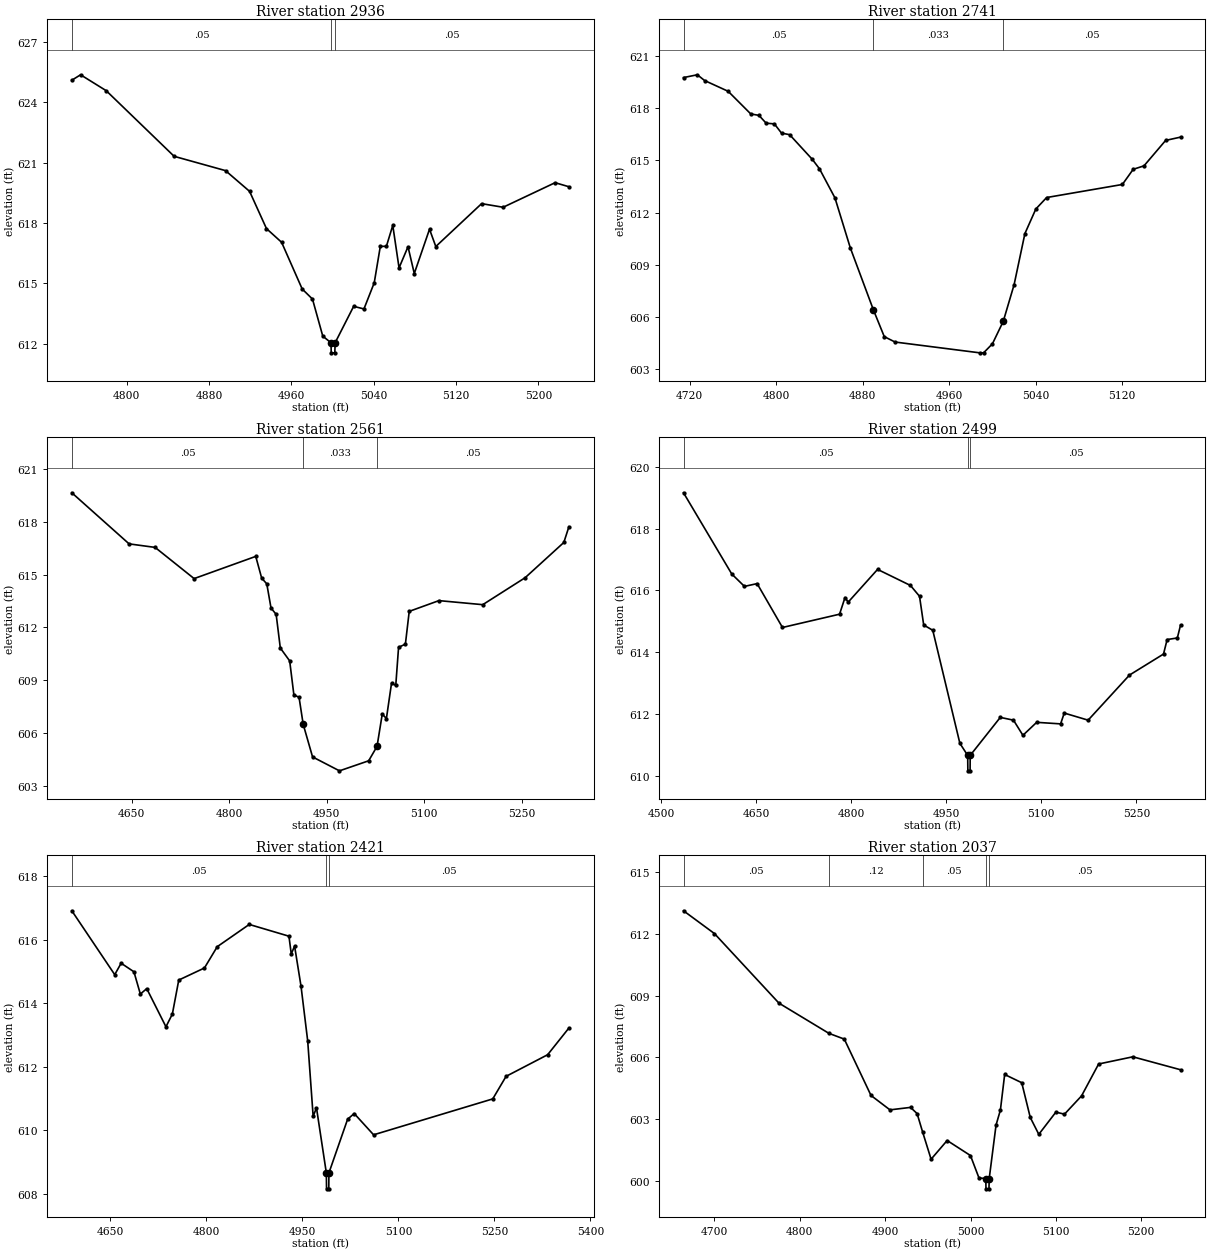
Type RM Length L Ch R = 1,2936,195,195,195
BEGIN DESCRIPTION:
Trail Creek Tr 1 4.4
END DESCRIPTION:
XS GIS Cut Line= 4
      2340560.61      7074251.77      2340626.93      7074074.25
      2340626.93      7073963.04      2340731.54      7073813.88
#Sta/Elev= 30
  4746.7  625.09  4755.2  625.36  4780.1  624.57  4846.1  621.31  4896.0  620.60
  4919.4  619.57  4935.8  617.72  4950.5  617.04  4970.5  614.72  4980.5  614.22
  4990.5  612.38  4998.5  612.05  4998.7  611.55  5002.2  611.55  5002.5  612.05
  5020.5  613.86  5030.5  613.73  5040.5  615.03  5046.4  616.84  5052.3  616.84
  5058.5  617.88  5064.6  615.77  5073.3  616.82  5079.4  615.49  5094.2  617.69
  5100.3  616.83  5144.8  618.96  5165.7  618.78  5216.2  620.00  5229.6  619.80
#Mann=3,-1,0
  4746.7    0.05       0  4998.5   0.033       0  5002.5    0.05       0
Bank Sta=4998.5,5002.5
Exp/Cntr=0.3,0.1

Type RM Length L Ch R = 1,2741,180,180,180
BEGIN DESCRIPTION:
Trail Creek Tr 1 4.0
END DESCRIPTION:
XS GIS Cut Line= 3
      2340714.76      7074253.72      2340825.95      7074126.93
      2340816.19      7073836.23
#Sta/Elev= 30
  4714.4  619.75  4727.2  619.91  4733.9  619.58  4755.7  618.96  4776.6  617.66
  4784.1  617.58  4790.8  617.13  4798.4  617.09  4805.0  616.56  4812.5  616.47
  4833.5  615.05  4840.1  614.51  4854.4  612.84  4868.6  609.97  4890.0  606.40
  4900.0  604.87  4910.0  604.56  4988.3  603.94  4991.8  603.94  5000.0  604.46
  5010.0  605.75  5020.0  607.85  5030.0  610.79  5040.1  612.20  5050.1  612.86
  5120.1  613.61  5130.1  614.48  5140.1  614.68  5160.1  616.14  5173.9  616.33
#Mann=3,-1,0
  4714.4    0.05       0  4890.0   0.033       0  5010.0    0.05       0
Bank Sta=4890,5010
Exp/Cntr=0.3,0.1

Type RM Length L Ch R = 1,2561,62,62,62
BEGIN DESCRIPTION:
Trail Creek Tr 1 3.5
END DESCRIPTION:
XS GIS Cut Line= 4
      2341099.10      7074398.11      2341097.15      7074115.22
      2340958.62      7073943.53      2340831.82      7073715.29
#Sta/Elev= 30
  4558.1  619.64  4646.2  616.74  4686.2  616.54  4746.2  614.77  4841.0  616.03
  4850.1  614.80  4858.0  614.47  4864.5  613.10  4872.4  612.74  4878.8  610.83
  4893.2  610.10  4899.7  608.16  4907.6  608.04  4914.0  606.50  4928.4  604.65
  4969.8  603.86  5014.7  604.43  5027.6  605.25  5035.6  607.08  5042.0  606.83
  5049.9  608.84  5056.4  608.71  5060.7  610.87  5071.2  611.05  5077.1  612.91
  5122.8  613.52  5190.2  613.29  5255.4  614.82  5314.9  616.82  5322.7  617.71
#Mann=3,-1,0
  4558.1    0.05       0  4914.0   0.033       0  5027.6    0.05       0
Bank Sta=4914,5027.6
Exp/Cntr=0.3,0.1

Type RM Length L Ch R = 1,2499,78,78,78
BEGIN DESCRIPTION:
Trail Creek Tr 1 3.4
END DESCRIPTION:
XS GIS Cut Line= 4
      2341116.66      7074396.17      2341126.41      7074052.79
      2341009.35      7073914.26      2340883.27      7073687.32
#Sta/Elev= 30
  4535.2  619.16  4611.4  616.53  4631.4  616.13  4651.4  616.22  4691.4  614.80
  4781.5  615.23  4790.1  615.77  4795.1  615.62  4841.5  616.68  4893.4  616.16
  4907.7  615.81  4914.3  614.88  4928.6  614.71  4971.4  611.05  4983.7  610.66
  4984.0  610.16  4987.5  610.16  4987.7  610.66  5035.2  611.89  5056.0  611.80
  5070.9  611.31  5092.6  611.73  5130.4  611.68  5136.1  612.03  5173.8  611.80
  5239.1  613.26  5292.8  613.94  5298.5  614.41  5314.6  614.46  5319.7  614.88
#Mann=3,-1,0
  4535.2    0.05       0  4983.7   0.033       0  4987.7    0.05       0
Bank Sta=4983.7,4987.7
Exp/Cntr=0.3,0.1

Type RM Length L Ch R = 1,2421,384,384,384
BEGIN DESCRIPTION:
Trail Creek Tr 1 3.3
END DESCRIPTION:
XS GIS Cut Line= 4
      2341159.58      7074366.91      2341145.92      7074031.33
      2341112.75      7073912.31      2340925.44      7073656.71
#Sta/Elev= 30
  4590.0  616.91  4657.0  614.90  4667.0  615.26  4687.0  614.99  4697.0  614.29
  4707.0  614.46  4737.0  613.26  4747.0  613.66  4757.0  614.73  4797.1  615.11
  4817.1  615.78  4867.1  616.48  4929.1  616.11  4932.7  615.55  4937.9  615.80
  4948.0  614.53  4958.4  612.81  4966.9  610.44  4972.1  610.71  4987.5  608.66
  4987.8  608.16  4991.3  608.16  4991.5  608.66  5020.7  610.35  5031.0  610.53
  5061.3  609.86  5247.4  610.99  5268.2  611.70  5333.1  612.38  5366.3  613.22
#Mann=3,-1,0
  4590.0    0.05       0  4987.5    0.04       0  4991.5    0.05       0
Bank Sta=4987.5,4991.5
Exp/Cntr=0.3,0.1

Type RM Length L Ch R = 1,2037,364,364,364
BEGIN DESCRIPTION:
Trail Creek Tr 1 3.0
END DESCRIPTION:
XS GIS Cut Line= 3
      2341284.81      7074423.59      2341400.15      7074139.37
      2341416.58      7073864.19
#Sta/Elev= 30
  4663.7  613.13  4700.0  612.02  4775.5  608.64  4834.1  607.17  4852.1  606.89
  4883.4  604.15  4905.6  603.45  4929.7  603.57  4937.4  603.27  4943.9  602.37
  4953.8  601.05  4972.6  601.96  4999.9  601.23  5009.9  600.14  5017.9  600.11
  5018.1  599.61  5021.6  599.61  5021.9  600.11  5029.9  602.71  5035.0  603.44
  5040.0  605.17  5060.0  604.77  5070.0  603.08  5080.0  602.26  5100.0  603.34
  5110.1  603.24  5130.1  604.13  5150.1  605.68  5190.2  606.03  5246.1  605.40
#Mann=5,-1,0
  4663.7    0.05       0  4834.1    0.12       0  4943.9    0.05       0
  5017.9   0.033       0  5021.9    0.05       0
Bank Sta=5017.9,5021.9
Exp/Cntr=0.3,0.1

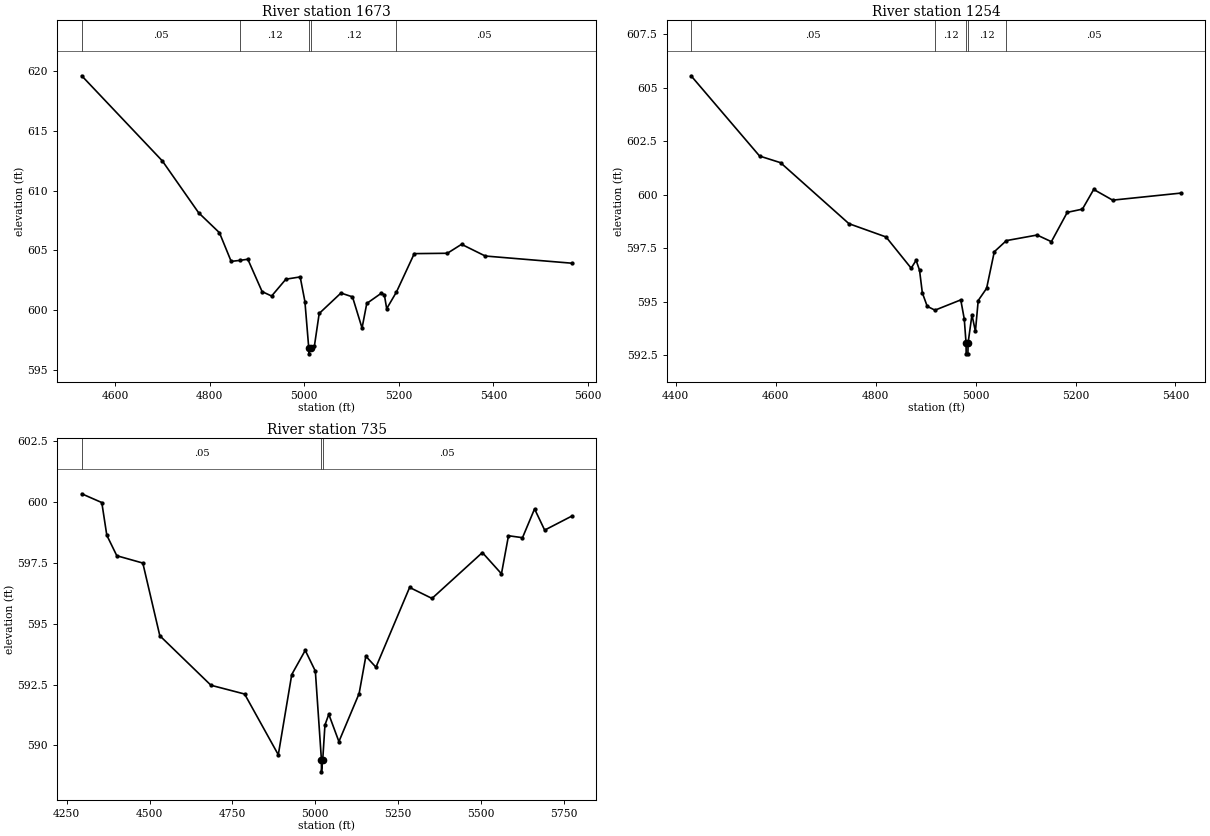
Type RM Length L Ch R = 1,1673,419,419,419
BEGIN DESCRIPTION:
Trail Creek Tr 1 2.3
END DESCRIPTION:
XS GIS Cut Line= 4
      2341218.93      7074662.42      2341498.99      7074514.15
      2341536.06      7074172.32      2341523.70      7073797.55
#Sta/Elev= 30
  4529.4  619.61  4699.9  612.48  4776.6  608.14  4820.6  606.47  4845.4  604.07
  4865.1  604.16  4880.6  604.25  4910.8  601.54  4930.9  601.17  4961.1  602.58
  4991.3  602.77  5001.3  600.71  5009.4  596.83  5009.7  596.33  5013.4  596.83
  5021.5  597.02  5031.5  599.71  5077.5  601.42  5101.9  601.10  5122.1  598.49
  5132.1  600.55  5162.3  601.39  5169.2  601.29  5174.2  600.11  5194.9  601.51
  5232.5  604.72  5302.5  604.75  5332.5  605.50  5382.6  604.52  5565.1  603.92
#Mann=5,-1,0
  4529.4    0.05       0  4865.1    0.12       0  5009.4    0.07       0
  5013.4    0.12       0  5194.9    0.05       0
Bank Sta=5009.4,5013.4
Exp/Cntr=0.3,0.1

Type RM Length L Ch R = 1,1254,519,519,519
BEGIN DESCRIPTION:
Trail Creek Tr 1 2.0
END DESCRIPTION:
XS GIS Cut Line= 4
      2341486.65      7074897.16      2341755.98      7074708.54
      2341902.60      7074415.31      2341861.47      7074094.49
#Sta/Elev= 30
  4430.8  605.56  4567.9  601.81  4609.8  601.50  4746.7  598.65  4820.9  598.03
  4871.2  596.57  4881.0  596.94  4887.9  596.48  4893.5  595.42  4903.3  594.79
  4918.8  594.61  4970.4  595.09  4977.4  594.20  4981.0  593.07  4981.2  592.57
  4984.7  592.57  4985.0  593.07  4992.8  594.39  4999.7  593.62  5005.3  595.06
  5022.1  595.63  5037.5  597.34  5061.7  597.86  5123.1  598.12  5151.7  597.81
  5183.5  599.18  5213.8  599.33  5236.4  600.25  5274.3  599.75  5410.9  600.08
#Mann=5,-1,0
  4430.8    0.05       0  4918.8    0.12       0  4981.0    0.07       0
  4985.0    0.12       0  5061.7    0.05       0
Bank Sta=4981,4985
Exp/Cntr=0.3,0.1

Type RM Length L Ch R = 1,735,0,0,0
BEGIN DESCRIPTION:
Trail Creek Tr 1 1.0
END DESCRIPTION:
XS GIS Cut Line= 4
      2341894.34      7075510.85      2342054.98      7075263.71
      2342182.65      7074559.46      2341931.71      7074164.53
#Sta/Elev= 30
  4295.2  600.32  4355.8  599.96  4370.9  598.62  4401.1  597.78  4479.6  597.48
  4530.9  594.50  4685.2  592.47  4786.8  592.11  4888.5  589.62  4929.1  592.91
  4969.8  593.90  5000.3  593.05  5018.6  589.42  5018.8  588.92  5022.6  589.42
  5029.3  590.84  5040.9  591.28  5071.4  590.16  5132.4  592.13  5152.7  593.66
  5183.2  593.21  5284.8  596.48  5352.4  596.03  5504.4  597.91  5562.0  597.04
  5583.2  598.60  5625.5  598.52  5661.9  599.70  5692.4  598.83  5773.6  599.40
#Mann=3,-1,0
  4295.2    0.05       0  5018.6   0.033       0  5022.6    0.05       0
Bank Sta=5018.6,5022.6
Exp/Cntr=0.3,0.1

Chan Stop Cuts=-1