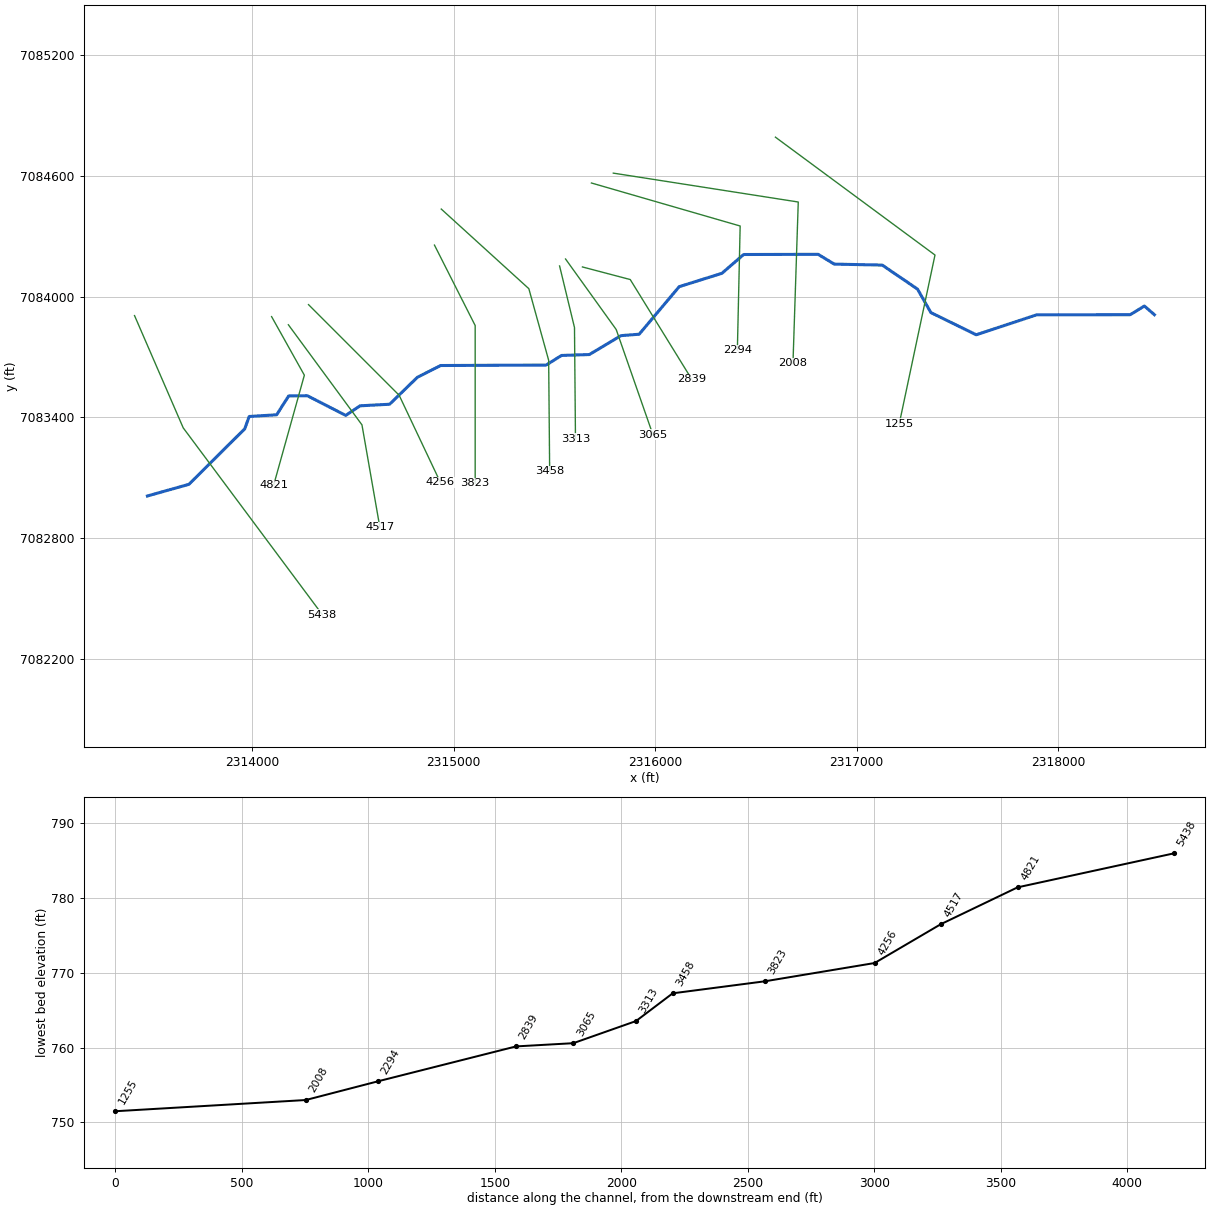
--- Trail Creek Tr 10.prj (project) ---

Proj Title=Trail Creek Tr 10 Base Level Engineering
Current Plan=p01
Default Exp/Contr=0.3,0.1
English Units
Geom File=g01
Flow File=f01
Plan File=p01
Y Axis Title=Elevation
X Axis Title(PF)=Main Channel Distance
X Axis Title(XS)=Station
BEGIN DESCRIPTION:
Trail Creek Tr 10
END DESCRIPTION:
DSS Export Rating Curves= 0
DSS Export Rating Curve Sorted= 0
DSS Export Volume Flow Curves= 0
DXF OffsetX= 0
DXF OffsetY= 0
DXF ScaleX= 1
DXF ScaleY= 10

--- Trail Creek Tr 10.p01 (plan) ---

Plan Title=Multiple Run
Program Version=4.10
Short Identifier=Multiple
Geom File=g01
Flow File=f01
Subcritical Flow
K Sum by GR= 0
Std Step Tol= 0.01
Critical Tol= 0.01
Num of Std Step Trials= 20
Max Error Tol= 0.3
Flow Tol Ratio= 0.001
Split Flow NTrial= 30
Split Flow Tol= 0.02
Split Flow Ratio= 0.02
Log Output Level= 0
Friction Slope Method= 1
Unsteady Friction Slope Method= 2
Unsteady Bridges Friction Slope Method= 1
Parabolic Critical Depth
Global Vel Dist= 1 , 1 , 1
Global Log Level= 0
CheckData=True
Encroach Param=-1 ,0,0, 0
BEGIN DESCRIPTION:
Multiple Run
END DESCRIPTION:
Computation Interval=1HOUR
Output Interval=1HOUR
Run HTab= 0
Run UNet= 0
Run PostProcess= 0
Run WQNet= 0
UNET Theta= 1
UNET Theta Warmup= 1
UNET ZTol= 0.02
UNET ZSATol= 0.05
UNET MxIter= 20
UNET MaxInSteps= 0
UNET DtIC= 0
UNET DtMin= 0
UNET MaxCRTS= 20
UNET WFStab= 2
UNET SFStab= 1
UNET WFX= 1
UNET SFX= 1
UNET DSS MLevel= 4
UNET DZMax Abort= 100
UNET Convert EG Bridges= 0
UNET Use Existing IB Tables=-1
UNET Froude Reduction=False
UNET Froude Limit= 1
UNET Froude Power= 10
UNET Time Slicing=0,0, 5
UNET Junction Losses=0
Instantaneous Interval=1HOUR
Write IC File= 0
Write IC File at Sim End=0
Echo Input=False
Echo Parameters=False
Echo Output=False
Write Detailed= 0
WQ AD Non Conservative
WQ ULTIMATE=-1
WQ Max Comp Step=1HOUR
WQ Output Interval=15MIN
WQ Output Selected Increments= 0
WQ Output face flow=0
WQ Output face velocity=0
WQ Output face area=0
WQ Output face dispersion=0
WQ Output cell volume=0
WQ Output cell surface area=0
WQ Output cell continuity=0
WQ Output cumulative cell continuity=0
WQ Output face conc=0
WQ Output face dconc_dx=0
WQ Output face courant=0
WQ Output face peclet=0
WQ Output face adv mass=0
WQ Output face disp mass=0
WQ Output cell mass=0
WQ Output cell source sink temp=0
WQ Output cell source sink nsm=0
WQ Output MaxMinRange=-1
WQ Daily Max Min Mean=-1
WQ Daily Range=0
WQ Daily Time=0
WQ Create Restart=0
WQ Fixed Restart=0
WQ System Summary=0
WQ Use Fixed Temperature=0
Sorting and Armoring Iterations= 10
XS Update Threshold= 0.02
Hydraulics Update Threshold= 0.02
Energy Slope Method= 1
Volume Change Method= 0
XS Weighting Method= 0
Number of US Weighted Cross Sections= 1
Number of DS Weighted Cross Sections= 1
Upstream XS Weight=0.25
Main XS Weight=0.5
Downstream XS Weight=0.25
Number of DS XS's Weighted with US Boundary= 1
Upstream Boundary Weight= 1
Weight of XSs Associated with US Boundary= 0
Number of US XS's Weighted with DS Boundary= 1
Downstream Boundary Weight= 0.5
Weight of XSs Associated with DS Boundary= 0.5
Sediment Output Level= 4
Mass or Volume Output= 0
Output Increment Type= 1
Profile and TS Output Increment= 10
XS Output Flag= 0
XS Output Increment= 10
Disregard all LS=0
Disregard all Conn=0
Disregard all Breaches=0
Disregard all Pumps=0

--- Trail Creek Tr 10.f01 (steady flow) ---

Flow Title=Multiple
Number of Profiles=7
Profile Names=10-year,25-year,50-year,1pct_min,100-year,1pct_plu,500-year
River Rch & RM= Trail Creek Tr 1,Reach-1,5438
     438     592     718     433     864    1724    1254
River Rch & RM= Trail Creek Tr 1,Reach-1,3313
     502     682     830     502    1002    1999    1462
Boundary for River Rch & Prof#=Trail Creek Tr 1,Reach-1,1
Up Type=0
Dn Type=3
Dn Slope=0.005
Boundary for River Rch & Prof#=Trail Creek Tr 1,Reach-1,2
Up Type=0
Dn Type=3
Dn Slope=0.005
Boundary for River Rch & Prof#=Trail Creek Tr 1,Reach-1,3
Up Type=0
Dn Type=3
Dn Slope=0.005
Boundary for River Rch & Prof#=Trail Creek Tr 1,Reach-1,4
Up Type=0
Dn Type=3
Dn Slope=0.005
Boundary for River Rch & Prof#=Trail Creek Tr 1,Reach-1,5
Up Type=0
Dn Type=3
Dn Slope=0.005
Boundary for River Rch & Prof#=Trail Creek Tr 1,Reach-1,6
Up Type=0
Dn Type=3
Dn Slope=0.005
Boundary for River Rch & Prof#=Trail Creek Tr 1,Reach-1,7
Up Type=0
Dn Type=3
Dn Slope=0.005

--- Trail Creek Tr 10.g01 (geometry) ---

Geom Title=Existing Conditions
Program Version=4.10

River Reach=Trail Creek Tr 1,Reach-1
Reach XY= 30
        2313479.        7083010.      2313685.17      7083067.86
      2313962.26      7083343.55      2313984.45      7083404.81
      2314120.68      7083413.11       2314180.3       7083506.6
      2314273.03      7083507.86       2314463.6      7083410.09
      2314534.93       7083457.7      2314681.45      7083465.47
      2314819.32      7083599.24      2314934.93      7083657.76
      2315458.97      7083660.07      2315534.94      7083707.73
      2315673.07      7083712.25      2315830.66      7083806.14
      2315920.66      7083813.16      2316119.32      7084049.24
      2316331.42      7084115.54      2316439.44      7084208.94
      2316808.97      7084209.93       2316889.5      7084161.22
      2317127.53      7084156.45      2317302.83      7084037.13
        2317369.      7083920.63      2317594.27      7083810.37
      2317894.22      7083909.48      2318359.02      7083910.14
      2318429.14      7083953.09        2318479.        7083910.

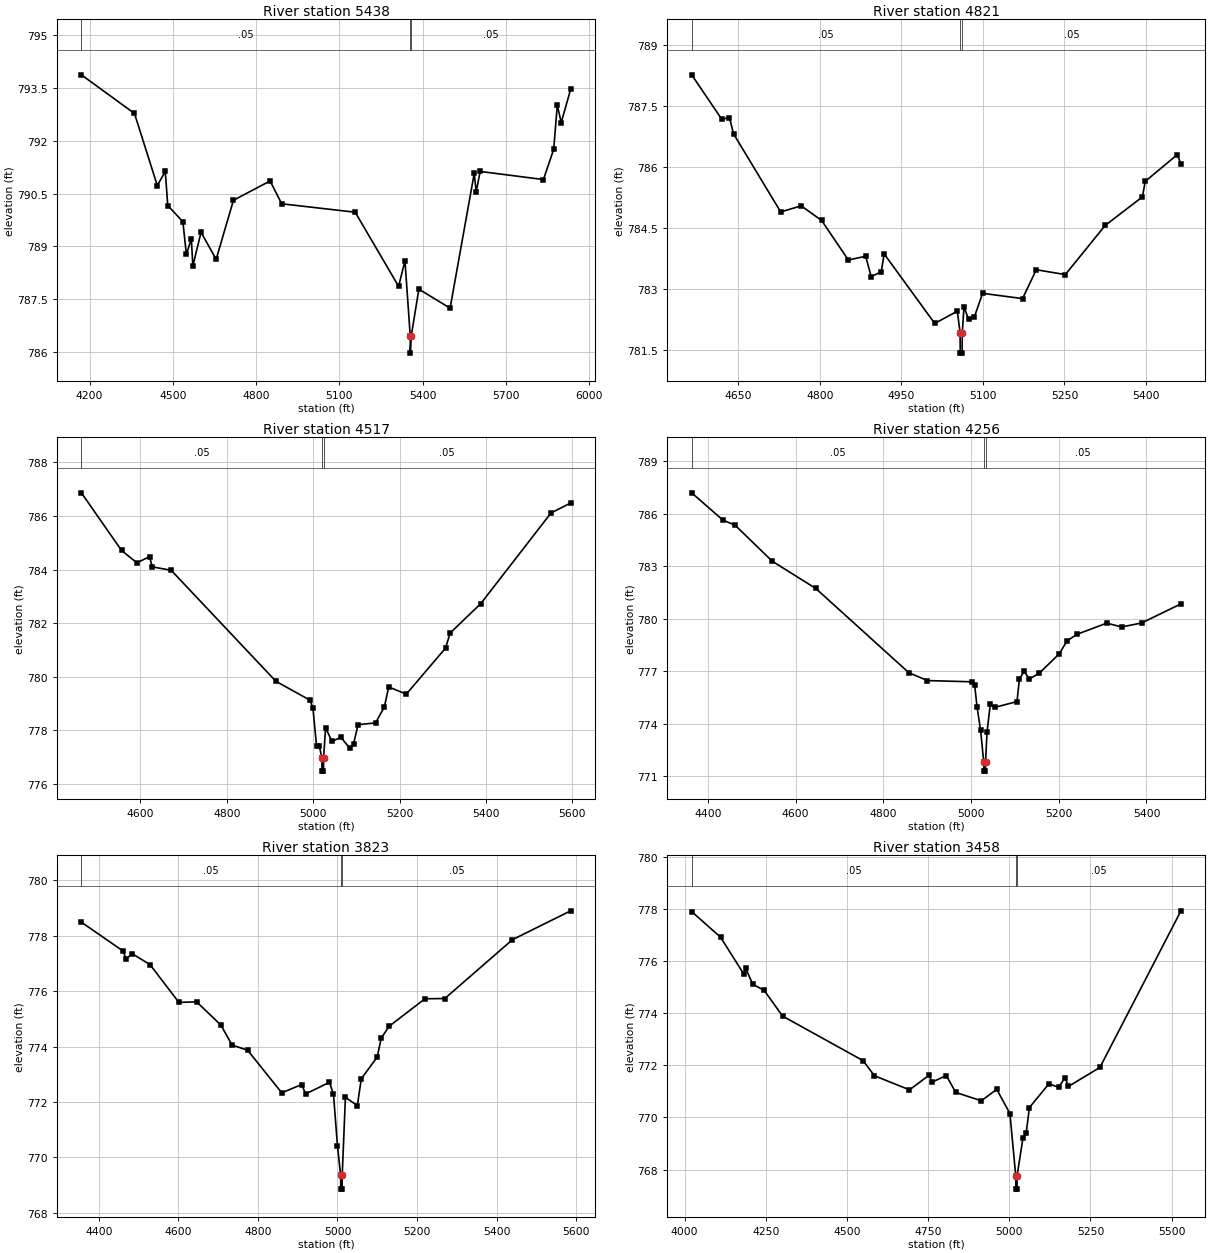
Type RM Length L Ch R = 1 ,5438    ,617,617,617
BEGIN DESCRIPTION:
Trail Creek Tr 10 7.0
END DESCRIPTION:
XS GIS Cut Line= 3
      2313415.05       7083905.6      2313656.68      7083348.37
      2314347.03      7082421.34
#Sta/Elev= 30
  4170.6  793.88    4362  792.78  4444.1  790.73    4473  791.13  4481.9  790.16
  4536.4   789.7  4548.9  788.77  4566.9  789.21  4572.3  788.44  4601.8   789.4
  4656.3  788.63  4718.6  790.31  4850.7  790.86  4892.5  790.21  5157.4  789.97
  5313.8  787.86  5336.7  788.59  5355.6  786.46  5355.8  785.96  5359.6  786.46
  5386.8  787.78  5499.4  787.24  5586.4  791.08  5593.2  790.55  5607.8  791.13
  5835.7   790.9  5872.7  791.76  5885.6  793.02  5899.8  792.52  5933.8  793.47
#Mann= 3 ,-1 , 0
  4170.6     .05       0  5355.6     .04       0  5359.6     .05       0
Bank Sta=5355.6,5359.6
XS Rating Curve= 0 ,0
Exp/Cntr=0.3,0.1

Type RM Length L Ch R = 1 ,4821    ,304,304,304
BEGIN DESCRIPTION:
Trail Creek Tr 10 6.0
END DESCRIPTION:
XS GIS Cut Line= 3
      2314095.55      7083900.64      2314258.27      7083609.72
      2314105.76      7083063.65
#Sta/Elev= 30
    4564  788.26  4619.3  787.17  4633.5  787.21    4641  786.81  4727.8  784.89
  4765.5  785.04  4803.1  784.68  4852.3  783.71  4884.2   783.8  4894.3   783.3
  4912.9  783.42  4918.1  783.86  5011.2  782.15  5052.8  782.45  5057.9  781.92
  5058.2  781.42  5061.7  781.42  5061.9  781.92  5065.1  782.56  5073.5  782.25
  5083.9   782.3  5099.3  782.89  5172.8  782.76  5198.1  783.47  5251.5  783.35
    5325  784.56  5393.4  785.26  5398.5  785.64  5457.7   786.3  5464.3  786.06
#Mann= 3 ,-1 , 0
    4564     .05       0  5057.9    .033       0  5061.9     .05       0
Bank Sta=5057.9,5061.9
XS Rating Curve= 0 ,0
Exp/Cntr=0.3,0.1

Type RM Length L Ch R = 1 ,4517    ,261,261,261
BEGIN DESCRIPTION:
Trail Creek Tr 10 5.0
END DESCRIPTION:
XS GIS Cut Line= 3
      2314178.98      7083860.02      2314544.26      7083363.17
      2314633.03      7082855.24
#Sta/Elev= 30
  4463.6  786.86  4556.6  784.71  4592.1  784.25  4621.4  784.48  4627.6   784.1
  4671.5  783.97  4913.8  779.83  4993.3  779.12  4999.5  778.82  5007.9  777.41
  5014.1  777.42  5020.2  776.98  5020.4  776.48  5023.9  776.48  5024.2  776.98
  5028.8   778.1  5043.4  777.59  5064.3  777.74  5084.4  777.34  5093.6   777.5
  5103.8  778.21  5144.4  778.28  5164.7  778.87  5174.9  779.62  5215.5  779.35
  5306.4  781.07    5317  781.63    5388  782.73  5550.5  786.11  5595.9  786.48
#Mann= 3 ,-1 , 0
  4463.6     .05       0  5020.2    .033       0  5024.2     .05       0
Bank Sta=5020.2,5024.2
XS Rating Curve= 0 ,0
Exp/Cntr=0.3,0.1

Type RM Length L Ch R = 1 ,4256    ,433,433,433
BEGIN DESCRIPTION:
Trail Creek Tr 10 4.0
END DESCRIPTION:
XS GIS Cut Line= 3
      2314278.97      7083960.03        2314729.        7083510.
      2314933.82      7083077.15
#Sta/Elev= 30
  4363.3  787.19  4434.1  785.64  4462.3  785.34  4547.2  783.28  4646.2  781.73
  4858.3  776.92  4900.7  776.47  5002.5   776.4  5008.3  776.22  5013.9  774.95
  5021.9  773.63  5029.1   771.8  5029.4   771.3  5032.9   771.3  5033.1   771.8
  5036.6  773.54    5044  775.12  5053.9  774.94  5104.9  775.27  5110.4  776.58
  5121.4  776.99  5133.2  776.56  5155.9   776.9  5201.4     778  5218.7  778.73
  5241.4  779.11  5309.5  779.75  5343.5  779.53    5389  779.76  5478.6  780.85
#Mann= 3 ,-1 , 0
  4363.3     .05       0  5029.1    .035       0  5033.1     .05       0
Bank Sta=5029.1,5033.1
XS Rating Curve= 0 ,0
Exp/Cntr=0.3,0.1

Type RM Length L Ch R = 1 ,3823    ,365,365,365
BEGIN DESCRIPTION:
Trail Creek Tr 10 3.0
END DESCRIPTION:
XS GIS Cut Line= 3
      2314904.24      7084255.66       2315106.4      7083856.27
       2315106.4      7083073.61
#Sta/Elev= 30
  4356.1  778.48    4462  777.43  4467.6  777.15  4484.3  777.34  4528.8  776.95
  4601.3  775.59  4645.8  775.61  4707.1  774.77    4735  774.05  4773.9  773.87
    4860  772.33    4910  772.63    4920  772.29    4980  772.71    4990  772.28
    5000  770.43    5008  769.36  5008.3  768.86  5011.8  768.86    5012  769.36
    5020  772.17    5050  771.87    5060  772.84    5100  773.62    5110   774.3
    5130  774.73    5220  775.72    5270  775.73    5440  777.85  5586.4  778.89
#Mann= 3 ,-1 , 0
  4356.1     .05       0    5008    .035       0    5012     .05       0
Bank Sta=5008,5012
XS Rating Curve= 0 ,0
Exp/Cntr=0.3,0.1

Type RM Length L Ch R = 1 ,3458    ,145,145,145
BEGIN DESCRIPTION:
Trail Creek Tr 10 2.2
END DESCRIPTION:
XS GIS Cut Line= 4
      2314938.12      7084434.54      2315372.87       7084039.2
      2315471.29      7083683.68      2315476.21      7083133.22
#Sta/Elev= 30
  4021.7   777.9  4110.5  776.92  4181.4  775.52  4188.2  775.72  4209.8  775.11
  4244.9  774.88  4301.7  773.89  4549.7  772.18  4584.8   771.6  4692.6  771.06
  4753.8  771.63  4761.2  771.35  4805.9  771.61    4835  770.96    4914  770.64
  4961.3  771.08  5001.9  770.15  5019.9  767.75  5020.2  767.25  5023.7  767.25
  5023.9  767.75  5041.9   769.2  5051.9  769.39  5061.9  770.38  5121.9  771.29
  5151.9  771.16  5171.9  771.53  5181.9  771.19  5279.1  771.92  5528.7  777.93
#Mann= 3 ,-1 , 0
  4021.7     .05       0  5019.9    .035       0  5023.9     .05       0
Bank Sta=5019.9,5023.9
XS Rating Curve= 0 ,0
Exp/Cntr=0.3,0.1

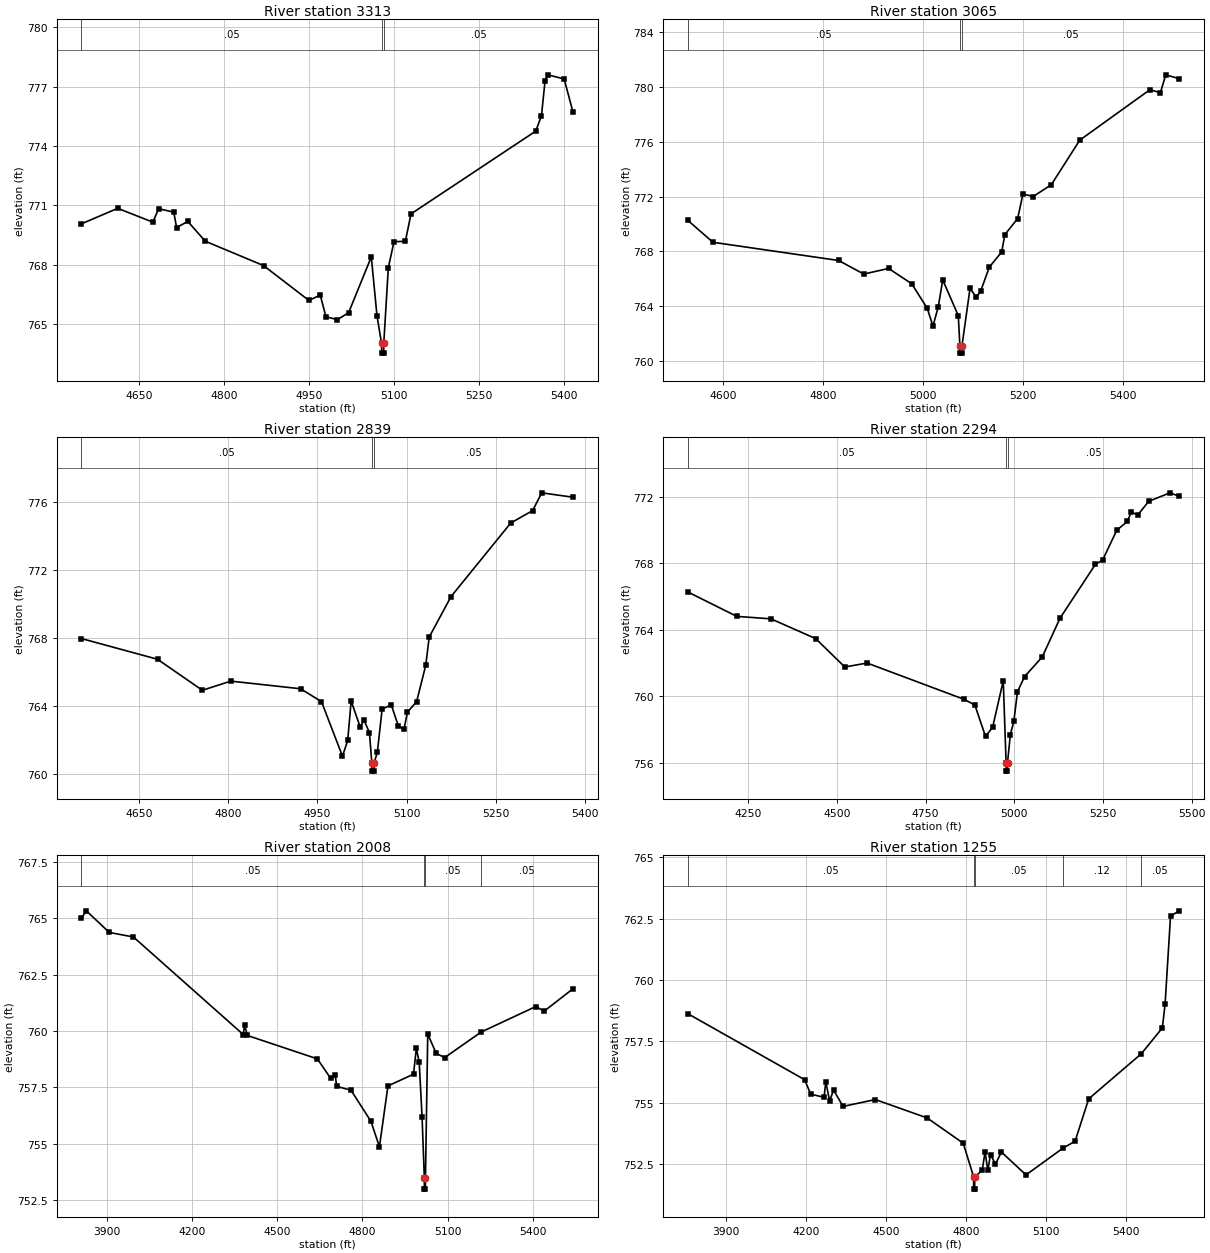
Type RM Length L Ch R = 1 ,3313    ,248,248,248
BEGIN DESCRIPTION:
Trail Creek Tr 10 2.0
END DESCRIPTION:
XS GIS Cut Line= 3
      2315525.54      7084152.11       2315599.5      7083846.41
      2315604.43      7083294.55
#Sta/Elev= 30
  4549.1  770.07    4613  770.85    4675  770.15    4685  770.83  4711.7  770.66
  4716.8  769.88  4736.5  770.19  4767.3  769.19    4870  767.96    4950   766.2
    4970  766.47    4980  765.38    5000  765.23    5020  765.58    5060   768.4
    5070  765.43    5078  764.04  5078.3  763.54  5081.8  763.54    5082  764.04
    5090  767.85    5100  769.17    5120  769.18    5130  770.57    5350  774.75
    5360  775.53  5366.3  777.29  5371.3  777.59    5400  777.38  5415.5  775.71
#Mann= 3 ,-1 , 0
  4549.1     .05       0    5078    .033       0    5082     .05       0
Bank Sta=5078,5082
XS Rating Curve= 0 ,0
Exp/Cntr=0.3,0.1

Type RM Length L Ch R = 1 ,3065    ,226,226,226
BEGIN DESCRIPTION:
Trail Creek Tr 10 1.0
END DESCRIPTION:
XS GIS Cut Line= 3
      2315555.12      7084186.64       2315806.6      7083836.54
      2315988.86       7083314.4
#Sta/Elev= 30
  4529.5  770.27  4579.9  768.67  4831.6  767.34  4881.9  766.35  4931.7  766.76
  4977.9  765.64    5009  763.85  5020.4  762.55    5031  763.95    5040  765.92
  5071.1  763.32  5074.4  761.08  5074.6  760.58  5078.1  760.58  5078.4  761.08
  5094.6   765.3  5107.4  764.66  5115.8  765.09  5133.2  766.85  5158.1  767.97
  5164.3  769.23  5189.9  770.39  5200.6  772.19  5221.1  772.01  5257.4  772.87
  5314.3  776.12  5454.7   779.8  5475.9  779.59  5486.5  780.89  5513.6  780.61
#Mann= 3 ,-1 , 0
  4529.5     .05       0  5074.4    .035       0  5078.4     .05       0
Bank Sta=5074.4,5078.4
XS Rating Curve= 0 ,0
Exp/Cntr=0.3,0.1

Type RM Length L Ch R = 1 ,2839    ,545,545,545
BEGIN DESCRIPTION:
Trail Creek Tr 10 0.9
END DESCRIPTION:
XS GIS Cut Line= 3
       2315638.9      7084147.21      2315876.31      7084084.66
      2316181.37      7083589.97
#Sta/Elev= 30
  4553.1  767.97    4681  766.75  4756.4  764.92  4804.3  765.46  4921.6  765.01
  4956.8  764.25  4992.1  761.03  5000.9  761.96  5006.7  764.29  5022.1  762.73
    5028  763.18  5037.5  762.42  5041.4  760.65  5041.7  760.15  5045.2  760.15
  5045.4  760.65  5050.8  761.27  5058.8  763.81  5074.2  764.06  5086.1  762.81
  5095.5  762.61  5101.4  763.63  5116.8  764.25  5132.2   766.4    5138  768.06
  5174.7  770.45  5275.2  774.79  5311.9  775.52  5327.3  776.57  5379.8  776.31
#Mann= 3 ,-1 , 0
  4553.1     .05       0  5041.4    .035       0  5045.4     .05       0
Bank Sta=5041.4,5045.4
XS Rating Curve= 0 ,0
Exp/Cntr=0.3,0.1

Type RM Length L Ch R = 1 ,2294    ,286,286,286
BEGIN DESCRIPTION:
Trail Creek Tr 10 0.7
END DESCRIPTION:
XS GIS Cut Line= 3
      2315683.69      7084564.03      2316422.11      7084350.45
      2316408.21        7083734.
#Sta/Elev= 30
  4079.9  766.28    4218  764.81  4314.4  764.66  4440.4  763.47  4522.6  761.76
  4585.3     762    4859  759.81  4889.1  759.47  4919.1  757.58  4939.1  758.13
  4969.1  760.93  4977.1  755.99  4977.3  755.49  4980.8  755.49  4981.1  755.99
  4989.1  757.69  4999.1  758.51  5009.1  760.27  5029.1  761.18  5079.1  762.37
  5129.1   764.7  5229.1  767.95  5249.1   768.2  5289.2     770  5319.2  770.53
  5329.2  771.07  5349.2  770.94  5379.2  771.74  5439.2  772.25  5465.2  772.04
#Mann= 3 ,-1 , 0
  4079.9     .05       0  4977.1    .035       0  4981.1     .05       0
Bank Sta=4977.1,4981.1
XS Rating Curve= 0 ,0
Exp/Cntr=0.3,0.1

Type RM Length L Ch R = 1 ,2008    ,753,753,753
BEGIN DESCRIPTION:
Trail Creek Tr 10 0.5
END DESCRIPTION:
XS GIS Cut Line= 3
       2315792.2      7084613.04      2316710.58       7084469.6
      2316684.32      7083668.84
#Sta/Elev= 30
  3810.8     765  3827.8  765.33  3908.8  764.37  3993.6  764.17  4380.4  759.84
  4385.4  760.27  4394.6   759.8  4641.5  758.76  4688.1   757.9  4704.3  758.04
  4709.4  757.54  4759.9  757.37    4830  755.99    4860  754.86    4890  757.56
    4980  758.08    4990  759.23  5000.1   758.6  5010.1   756.2  5018.1  753.48
  5018.3  752.98  5021.8  752.98  5022.1  753.48  5030.1  759.86  5060.1     759
  5090.1  758.82    5218  759.95  5410.3  761.08  5440.3  760.88  5541.5  761.87
#Mann= 4 ,-1 , 0
  3810.8     .05       0  5018.1    .035       0  5022.1     .05       0
    5218     .05       0
Bank Sta=5018.1,5022.1
XS Rating Curve= 0 ,0
Exp/Cntr=0.3,0.1

Type RM Length L Ch R = 1 ,1255    ,0,0,0
BEGIN DESCRIPTION:
Trail Creek Tr 10 0.3
END DESCRIPTION:
XS GIS Cut Line= 3
      2316597.24      7084791.54      2317389.46      7084206.37
      2317211.93      7083368.06
#Sta/Elev= 30
  3758.2  758.63  4195.9  755.94  4218.9  755.35    4269  755.22  4275.2  755.86
  4289.9  755.07  4304.5  755.52    4340  754.85    4461  755.13  4655.3  754.38
  4790.5  753.35  4829.4  751.98  4829.6  751.48  4833.1  751.48  4833.4  751.98
  4861.5  752.24  4872.3     753  4882.5  752.24  4892.7  752.89  4911.1   752.5
  4933.6  752.99  5025.6  752.06  5165.4  753.16  5209.6  753.43  5260.7  755.16
  5457.2  756.99  5536.7  758.05  5546.9  759.02  5567.3  762.61    5600  762.82
#Mann= 5 ,-1 , 0
  3758.2     .05       0  4829.4    .035       0  4833.4     .05       0
  5165.4     .12       0  5457.2     .05       0
Bank Sta=4829.4,4833.4
XS Rating Curve= 0 ,0
Exp/Cntr=0.3,0.1

Chan Stop Cuts=-1
Use User Specified Reach Order=0
Composite Channel Slope=5