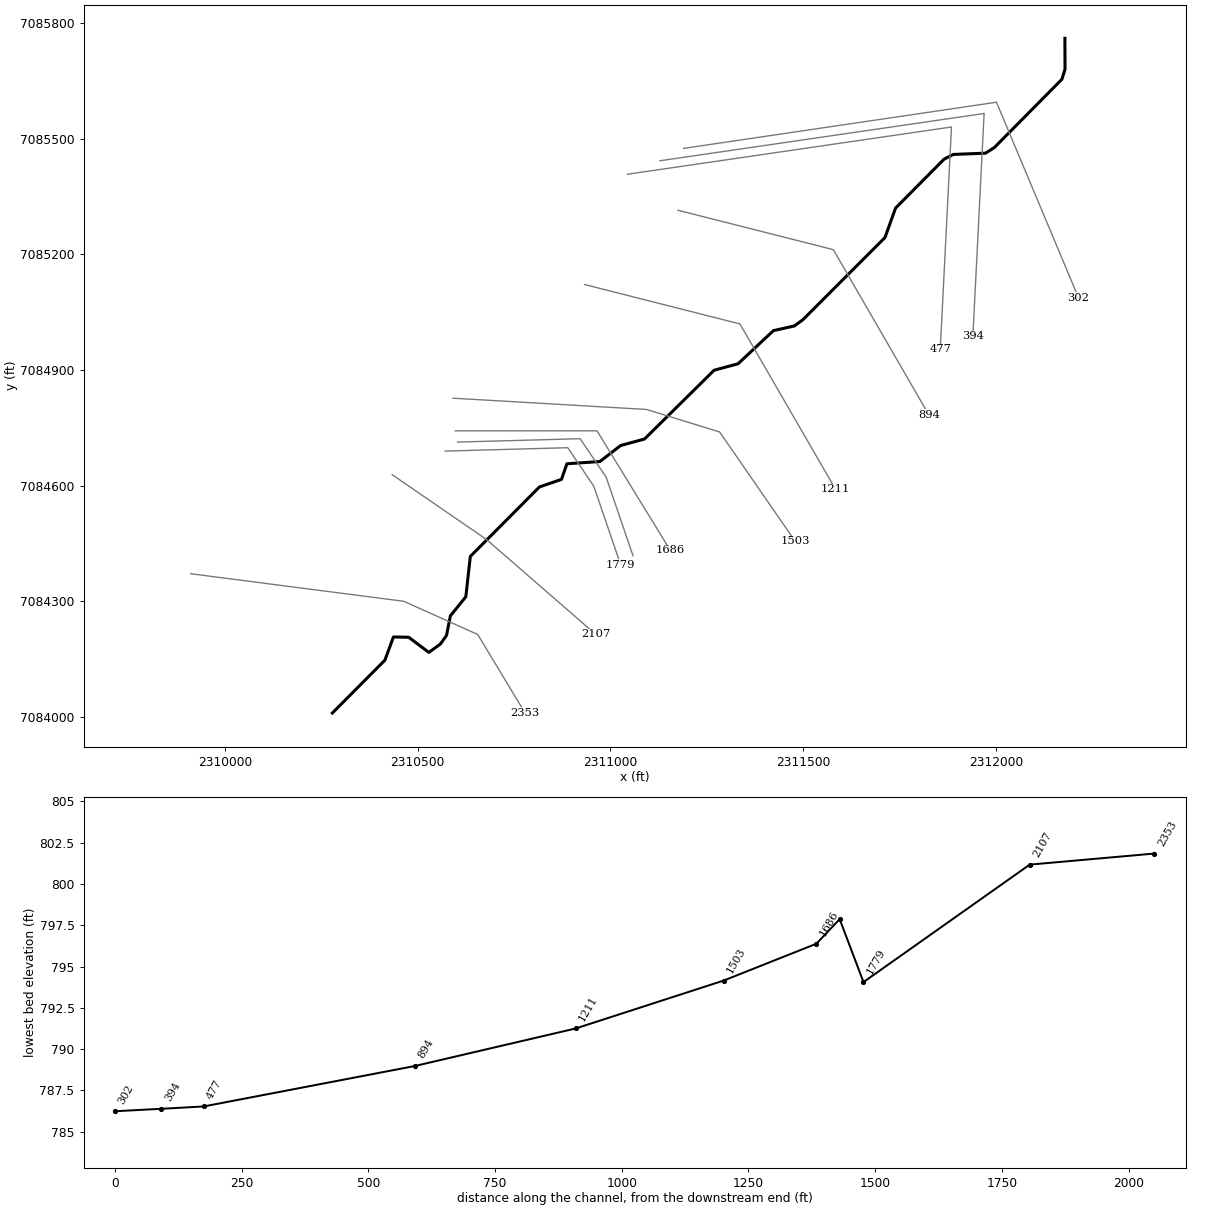
--- Trail Creek Tr 12.prj (project) ---

Proj Title=Trail Creek Tr 12 Base Level Engineering
Current Plan=p01
Default Exp/Contr=0.3,0.1
English Units
Geom File=g01
Flow File=f01
Plan File=p01
BEGIN DESCRIPTION:
Trail Creek Tr 12
END DESCRIPTION:

--- Trail Creek Tr 12.p01 (plan) ---

Plan Title=Multiple Run
Short Identifier=Multiple
Geom File=g01
Flow File=f01
Subcritical Flow
K Sum by GR= 0
Std Step Tol= 0.01
Critical Tol= 0.01
Num of Std Step Trials= 20
Max Error Tol= 0.3
Flow Tol Ratio= 0.001
Split Flow NTrial= 30
Split Flow Tol= 0.02
Split Flow Ratio= 0.02
Log Output Level= 0
Friction Slope Method= 1
Unsteady Friction Slope Method= 2
Unsteady Bridges Friction Slope Method= 1
Parabolic Critical Depth
Global Vel Dist=  1 , 1 , 1
Global Log Level= 0
CheckData=True
Encroach Param= -1, 0, 0, 0
BEGIN DESCRIPTION:
Multiple Run
END DESCRIPTION:

--- Trail Creek Tr 12.f01 (steady flow) ---

Flow Title=Multiple
Number of Profiles=7
Profile Names=10-year,25-year,50-year,1pct_min,100-year,1pct_plu,500-year
River Rch & RM= Trail Creek Tr 1,Reach-1,2353
     337     447     535     319     636    1269     901
Boundary for River Rch & Prof#=Trail Creek Tr 1,Reach-1,1
Up Type=0
Dn Type=3
Dn Slope=0.005
Boundary for River Rch & Prof#=Trail Creek Tr 1,Reach-1,2
Up Type=0
Dn Type=3
Dn Slope=0.005
Boundary for River Rch & Prof#=Trail Creek Tr 1,Reach-1,3
Up Type=0
Dn Type=3
Dn Slope=0.005
Boundary for River Rch & Prof#=Trail Creek Tr 1,Reach-1,4
Up Type=0
Dn Type=3
Dn Slope=0.005
Boundary for River Rch & Prof#=Trail Creek Tr 1,Reach-1,5
Up Type=0
Dn Type=3
Dn Slope=0.005
Boundary for River Rch & Prof#=Trail Creek Tr 1,Reach-1,6
Up Type=0
Dn Type=3
Dn Slope=0.005
Boundary for River Rch & Prof#=Trail Creek Tr 1,Reach-1,7
Up Type=0
Dn Type=3
Dn Slope=0.005

--- Trail Creek Tr 12.g01 (geometry) ---

Geom Title=Existing Conditions

River Reach=Trail Creek Tr 1,Reach-1
Reach XY= 30
      2310279.00      7084010.00      2310415.28      7084147.08
      2310437.50      7084207.33      2310477.00      7084206.56
      2310529.27      7084167.27      2310559.23      7084188.98
      2310575.06      7084211.16      2310585.14      7084262.12
      2310625.17      7084311.58      2310636.86      7084416.17
      2310816.00      7084596.31      2310873.20      7084616.05
      2310887.48      7084656.51      2310972.95      7084662.36
      2311026.83      7084703.86      2311088.68      7084720.76
      2311269.32      7084899.22      2311331.28      7084915.87
      2311422.96      7085001.82      2311477.35      7085013.97
      2311499.09      7085029.79      2311712.35      7085243.33
      2311739.78      7085319.68      2311865.70      7085446.60
      2311889.48      7085458.83      2311973.11      7085462.15
      2311995.75      7085476.46      2312171.26      7085653.78
      2312179.33      7085679.86      2312179.00      7085760.00

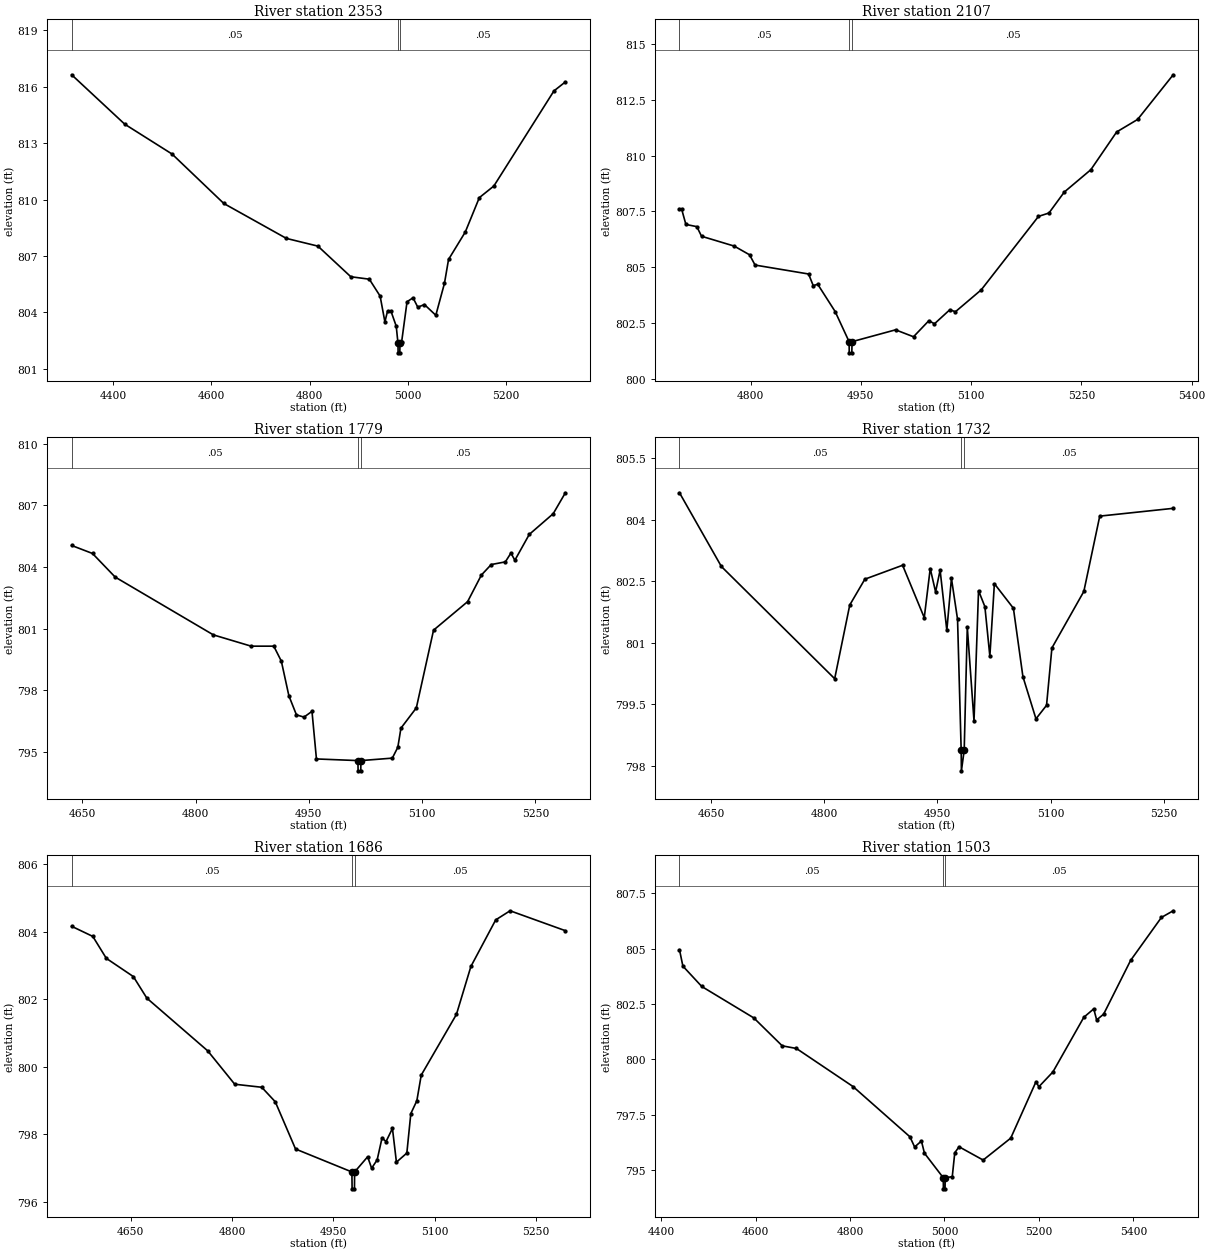
Type RM Length L Ch R = 1,2353,246,246,246
BEGIN DESCRIPTION:
Trail Creek Tr 12 4.0
END DESCRIPTION:
XS GIS Cut Line= 4
      2309911.78      7084371.30      2310464.39      7084299.82
      2310656.06      7084213.69      2310779.02      7084009.97
#Sta/Elev= 30
  4315.5  816.64  4423.6  814.01  4520.0  812.42  4625.3  809.79  4752.8  807.93
  4816.9  807.52  4883.9  805.89  4921.6  805.76  4943.6  804.86  4953.3  803.49
  4958.8  804.07  4965.5  804.07  4976.4  803.26  4980.0  802.34  4980.2  801.84
  4983.7  801.84  4984.0  802.34  4987.5  802.44  4998.4  804.56  5010.6  804.77
  5020.3  804.27  5033.8  804.41  5057.0  803.84  5074.6  805.54  5082.9  806.81
  5117.0  808.27  5145.6  810.10  5175.2  810.72  5297.5  815.78  5320.8  816.26
#Mann=3,-1,0
  4315.5    0.05       0  4980.0   0.033       0  4984.0    0.05       0
Bank Sta=4980,4984
Exp/Cntr=0.3,0.1

Type RM Length L Ch R = 1,2107,328,328,328
BEGIN DESCRIPTION:
Trail Creek Tr 12 3.0
END DESCRIPTION:
XS GIS Cut Line= 3
      2310434.23      7084628.14      2310679.00      7084460.00
      2310961.74      7084214.36
#Sta/Elev= 30
  4703.3  807.62  4706.1  807.62  4712.0  806.92  4726.9  806.82  4733.3  806.39
  4777.7  805.95  4798.6  805.56  4806.1  805.10  4878.9  804.70  4885.2  804.18
  4891.3  804.24  4915.0  803.02  4934.0  801.67  4934.2  801.17  4937.7  801.17
  4938.0  801.67  4997.2  802.20  5021.6  801.89  5042.5  802.61  5050.1  802.47
  5071.0  803.10  5078.6  803.01  5113.7  803.99  5191.6  807.28  5205.8  807.43
  5226.7  808.37  5262.8  809.37  5297.9  811.06  5326.4  811.62  5374.8  813.62
#Mann=3,-1,0
  4703.3    0.05       0  4934.0   0.033       0  4938.0    0.05       0
Bank Sta=4934,4938
Exp/Cntr=0.3,0.1

Type RM Length L Ch R = 1,1779,47,47,47
BEGIN DESCRIPTION:
Trail Creek Tr 12 2.2
END DESCRIPTION:
XS GIS Cut Line= 4
      2310571.42      7084689.43      2310889.55      7084698.19
      2310957.12      7084598.30      2311026.67      7084394.81
#Sta/Elev= 30
  4635.9  805.05  4663.5  804.66  4693.5  803.51  4823.6  800.69  4873.6  800.14
  4903.6  800.14  4913.6  799.41  4923.6  797.72  4933.6  796.79  4943.6  796.68
  4954.2  796.96  4960.1  794.64  5015.0  794.56  5015.3  794.06  5018.8  794.06
  5019.0  794.56  5060.6  794.68  5067.9  795.21  5072.0  796.14  5092.4  797.13
  5115.2  800.92  5160.3  802.31  5178.6  803.61  5191.6  804.12  5210.3  804.25
  5217.7  804.68  5222.9  804.33  5242.0  805.59  5273.7  806.60  5289.8  807.62
#Mann=3,-1,0
  4635.9    0.05       0  5015.0   0.033       0  5019.0    0.05       0
Bank Sta=5015,5019
Exp/Cntr=0.3,0.1

Type RM Length L Ch R = 1,1732,46,46,46
BEGIN DESCRIPTION:
Trail Creek Tr 12 2.1
END DESCRIPTION:
XS GIS Cut Line= 4
      2310603.52      7084712.78      2310921.66      7084721.54
      2310989.23      7084621.65      2311058.84      7084417.98
#Sta/Elev= 30
  4608.2  804.66  4663.7  802.86  4813.8  800.12  4833.8  801.92  4853.8  802.55
  4903.8  802.89  4932.5  801.61  4940.4  802.81  4947.5  802.24  4953.5  802.77
  4962.4  801.30  4968.5  802.57  4976.6  801.57  4981.4  798.37  4981.7  797.87
  4985.4  798.37  4989.5  801.38  4998.4  799.09  5004.4  802.27  5012.8  801.88
  5019.4  800.67  5025.4  802.44  5050.6  801.84  5063.2  800.17  5080.5  799.14
  5094.5  799.47  5101.6  800.87  5143.9  802.25  5165.0  804.09  5262.3  804.28
#Mann=3,-1,0
  4608.2    0.05       0  4981.4   0.033       0  4985.4    0.05       0
Bank Sta=4981.4,4985.4
Exp/Cntr=0.3,0.1

Type RM Length L Ch R = 1,1686,183,183,183
BEGIN DESCRIPTION:
Trail Creek Tr 12 2.0
END DESCRIPTION:
XS GIS Cut Line= 3
      2310597.72      7084741.97      2310965.44      7084741.97
      2311155.14      7084432.62
#Sta/Elev= 30
  4562.8  804.16  4594.1  803.86  4614.1  803.21  4654.1  802.67  4674.1  802.03
  4764.1  800.47  4804.1  799.48  4844.1  799.39  4864.1  798.96  4894.1  797.56
  4977.5  796.88  4977.8  796.38  4981.3  796.38  4981.5  796.88  5000.8  797.33
  5006.7  796.99  5014.9  797.24  5022.1  797.89  5028.0  797.78  5037.5  798.17
  5043.4  797.17  5058.8  797.44  5064.7  798.61  5073.6  798.99  5080.1  799.75
  5132.2  801.55  5153.6  802.97  5190.3  804.35  5211.6  804.62  5293.4  804.03
#Mann=3,-1,0
  4562.8    0.05       0  4977.5   0.033       0  4981.5    0.05       0
Bank Sta=4977.5,4981.5
Exp/Cntr=0.3,0.1

Type RM Length L Ch R = 1,1503,292,292,292
BEGIN DESCRIPTION:
Trail Creek Tr 12 1.0
END DESCRIPTION:
XS GIS Cut Line= 4
      2310591.84      7084826.61      2311093.86      7084797.42
      2311283.54      7084738.94      2311479.14      7084455.92
#Sta/Elev= 30
  4439.0  804.95  4446.2  804.21  4486.2  803.29  4596.4  801.87  4656.5  800.61
  4686.6  800.49  4806.5  798.77  4927.0  796.50  4936.9  796.04  4951.3  796.31
  4957.7  795.76  4997.6  794.65  4997.8  794.15  5001.3  794.15  5001.6  794.65
  5016.6  794.70  5021.9  795.78  5031.0  796.05  5082.0  795.45  5140.4  796.44
  5193.9  798.99  5199.9  798.76  5229.7  799.43  5295.2  801.90  5316.2  802.28
  5322.3  801.78  5337.1  802.04  5394.3  804.47  5459.5  806.41  5484.4  806.71
#Mann=3,-1,0
  4439.0    0.05       0  4997.6   0.033       0  5001.6    0.05       0
Bank Sta=4997.6,5001.6
Exp/Cntr=0.3,0.1

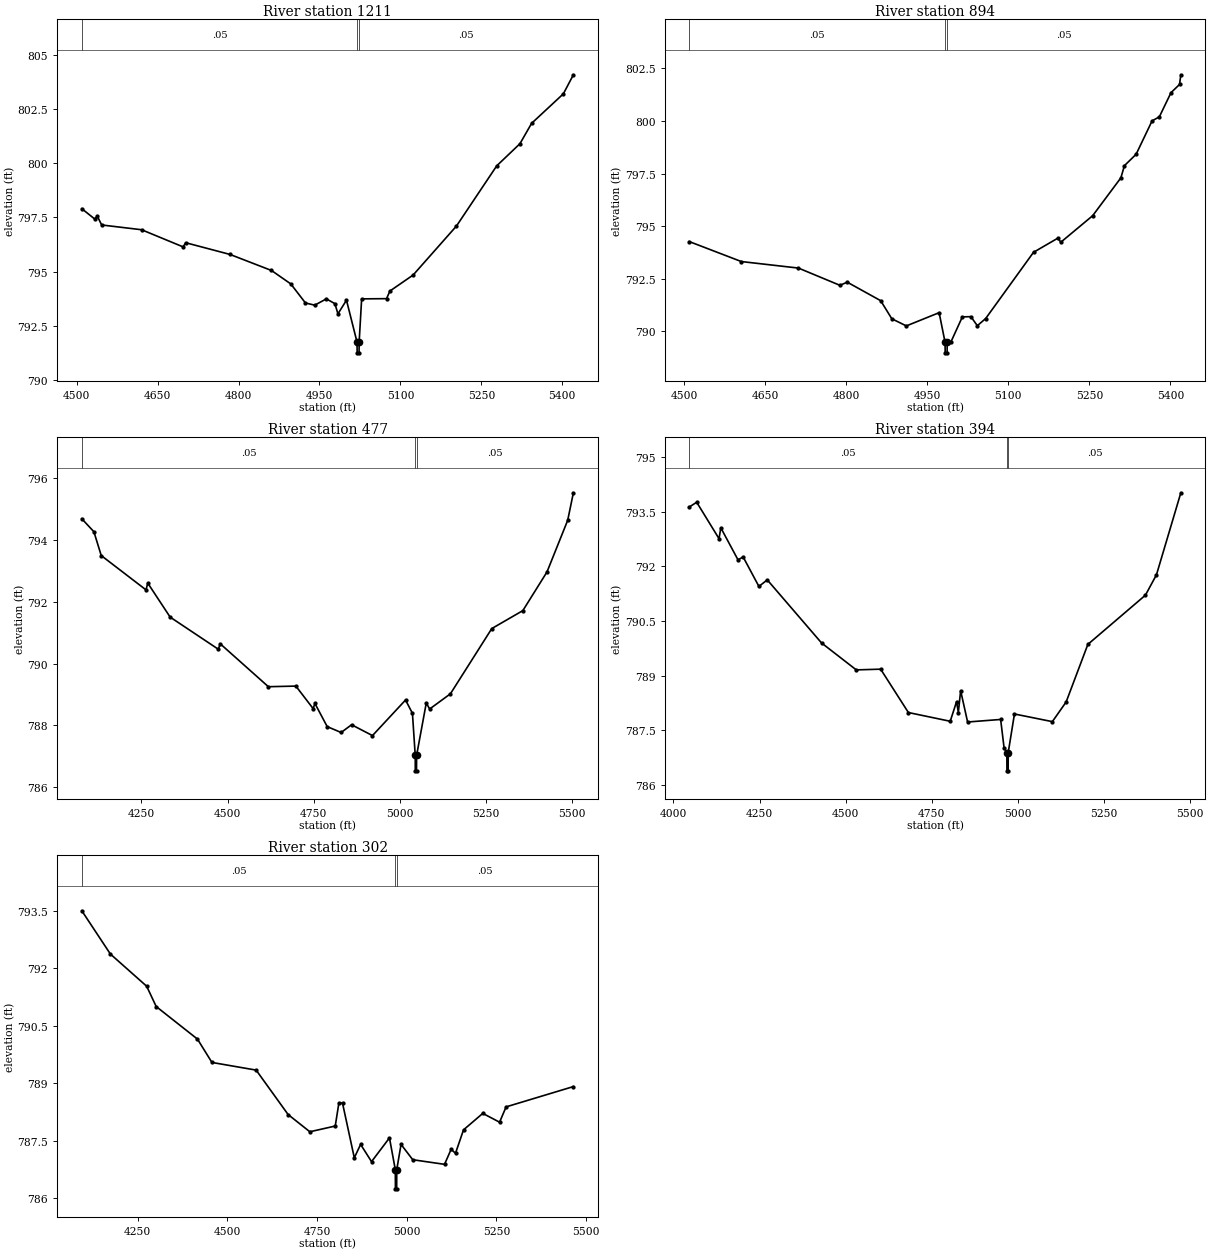
Type RM Length L Ch R = 1,1211,317,317,317
BEGIN DESCRIPTION:
Trail Creek Tr 12 0.8
END DESCRIPTION:
XS GIS Cut Line= 3
      2310933.31      7085121.40      2311336.11      7085019.24
      2311584.12      7084590.34
#Sta/Elev= 30
  4509.6  797.90  4533.3  797.43  4538.4  797.55  4546.4  797.15  4620.4  796.93
  4697.2  796.14  4702.3  796.33  4784.3  795.79  4861.1  795.05  4896.9  794.43
  4924.1  793.55  4941.3  793.45  4962.8  793.74  4978.6  793.52  4984.3  793.05
  5000.1  793.68  5019.6  791.75  5019.9  791.25  5023.4  791.25  5023.6  791.75
  5028.2  793.74  5074.4  793.75  5080.5  794.10  5123.6  794.84  5203.9  797.10
  5278.6  799.88  5321.6  800.90  5343.2  801.84  5402.0  803.20  5420.6  804.08
#Mann=3,-1,0
  4509.6    0.05       0  5019.6    0.04       0  5023.6    0.05       0
Bank Sta=5019.6,5023.6
Exp/Cntr=0.3,0.1

Type RM Length L Ch R = 1,894,417,417,417
BEGIN DESCRIPTION:
Trail Creek Tr 12 0.7
END DESCRIPTION:
XS GIS Cut Line= 3
      2311175.57      7085314.03      2311578.36      7085211.88
      2311825.82      7084783.92
#Sta/Elev= 30
  4509.4  794.27  4605.8  793.32  4711.5  793.01  4788.3  792.19  4801.8  792.34
  4863.7  791.46  4884.3  790.60  4911.2  790.26  4971.9  790.89  4982.9  789.48
  4983.1  788.98  4986.6  788.98  4986.9  789.48  4993.4  789.48  5014.9  790.69
  5030.7  790.70  5042.6  790.27  5058.0  790.61  5146.6  793.76  5191.5  794.43
  5197.2  794.24  5256.1  795.50  5308.3  797.30  5314.9  797.88  5336.5  798.42
  5366.1  800.01  5379.5  800.20  5401.1  801.35  5416.9  801.74  5419.3  802.20
#Mann=3,-1,0
  4509.4    0.05       0  4982.9    0.04       0  4986.9    0.05       0
Bank Sta=4982.9,4986.9
Exp/Cntr=0.3,0.1

Type RM Length L Ch R = 1,477,83,83,83
BEGIN DESCRIPTION:
Trail Creek Tr 12 0.5
END DESCRIPTION:
XS GIS Cut Line= 3
      2311044.23      7085407.43      2311884.83      7085530.01
      2311855.71      7084953.53
#Sta/Elev= 30
  4077.0  794.68  4112.1  794.26  4133.4  793.49  4263.4  792.38  4268.4  792.60
  4333.4  791.50  4473.4  790.46  4478.5  790.64  4618.5  789.25  4698.3  789.27
  4748.5  788.54  4753.5  788.71  4789.2  787.96  4829.6  787.77  4860.0  788.02
  4920.6  787.67  5016.6  788.82  5036.6  788.39  5044.7  787.03  5044.9  786.53
  5048.4  786.53  5048.7  787.03  5076.7  788.72  5086.7  788.53  5146.8  789.02
  5266.9  791.13  5357.0  791.71  5427.1  792.96  5487.2  794.63  5503.7  795.52
#Mann=3,-1,0
  4077.0    0.05       0  5044.7   0.033       0  5048.7    0.05       0
Bank Sta=5044.7,5048.7
Exp/Cntr=0.3,0.1

Type RM Length L Ch R = 1,394,92,92,92
BEGIN DESCRIPTION:
Trail Creek Tr 12 0.4
END DESCRIPTION:
XS GIS Cut Line= 3
      2311128.85      7085442.45      2311969.47      7085565.04
      2311940.28      7084987.18
#Sta/Elev= 30
  4045.9  793.63  4067.5  793.76  4132.4  792.76  4137.5  793.06  4187.5  792.18
  4202.4  792.26  4248.2  791.45  4272.5  791.63  4430.1  789.90  4531.1  789.16
  4601.9  789.18  4682.5  787.99  4804.0  787.75  4822.5  788.29  4827.6  787.99
  4834.3  788.59  4854.5  787.73  4950.5  787.80  4960.5  787.02  4968.5  786.89
  4968.8  786.39  4972.3  786.39  4972.5  786.89  4990.6  787.95  5100.7  787.74
  5140.8  788.28  5203.9  789.86  5371.1  791.21  5403.2  791.77  5474.0  794.02
#Mann=3,-1,0
  4045.9    0.05       0  4968.5   0.033       0  4972.5    0.05       0
Bank Sta=4968.5,4972.5
Exp/Cntr=0.3,0.1

Type RM Length L Ch R = 1,302,0,0,0
BEGIN DESCRIPTION:
Trail Creek Tr 12 0.3
END DESCRIPTION:
XS GIS Cut Line= 3
      2311190.18      7085474.56      2312001.57      7085594.22
      2312214.32      7085087.12
#Sta/Elev= 30
  4094.3  793.50  4174.0  792.37  4275.1  791.53  4301.6  791.00  4416.6  790.15
  4457.0  789.54  4580.2  789.34  4669.3  788.18  4729.9  787.73  4800.7  787.88
  4810.8  788.48  4820.9  788.48  4853.8  787.05  4871.4  787.40  4901.8  786.95
  4951.8  787.57  4968.1  786.74  4968.4  786.24  4971.9  786.24  4972.1  786.74
  4984.1  787.40  5016.7  787.00  5105.3  786.88  5123.6  787.27  5135.9  787.17
  5158.2  787.78  5211.9  788.21  5258.7  787.98  5276.9  788.38  5464.4  788.91
#Mann=3,-1,0
  4094.3    0.05       0  4968.1   0.033       0  4972.1    0.05       0
Bank Sta=4968.1,4972.1
Exp/Cntr=0.3,0.1

Chan Stop Cuts=-1