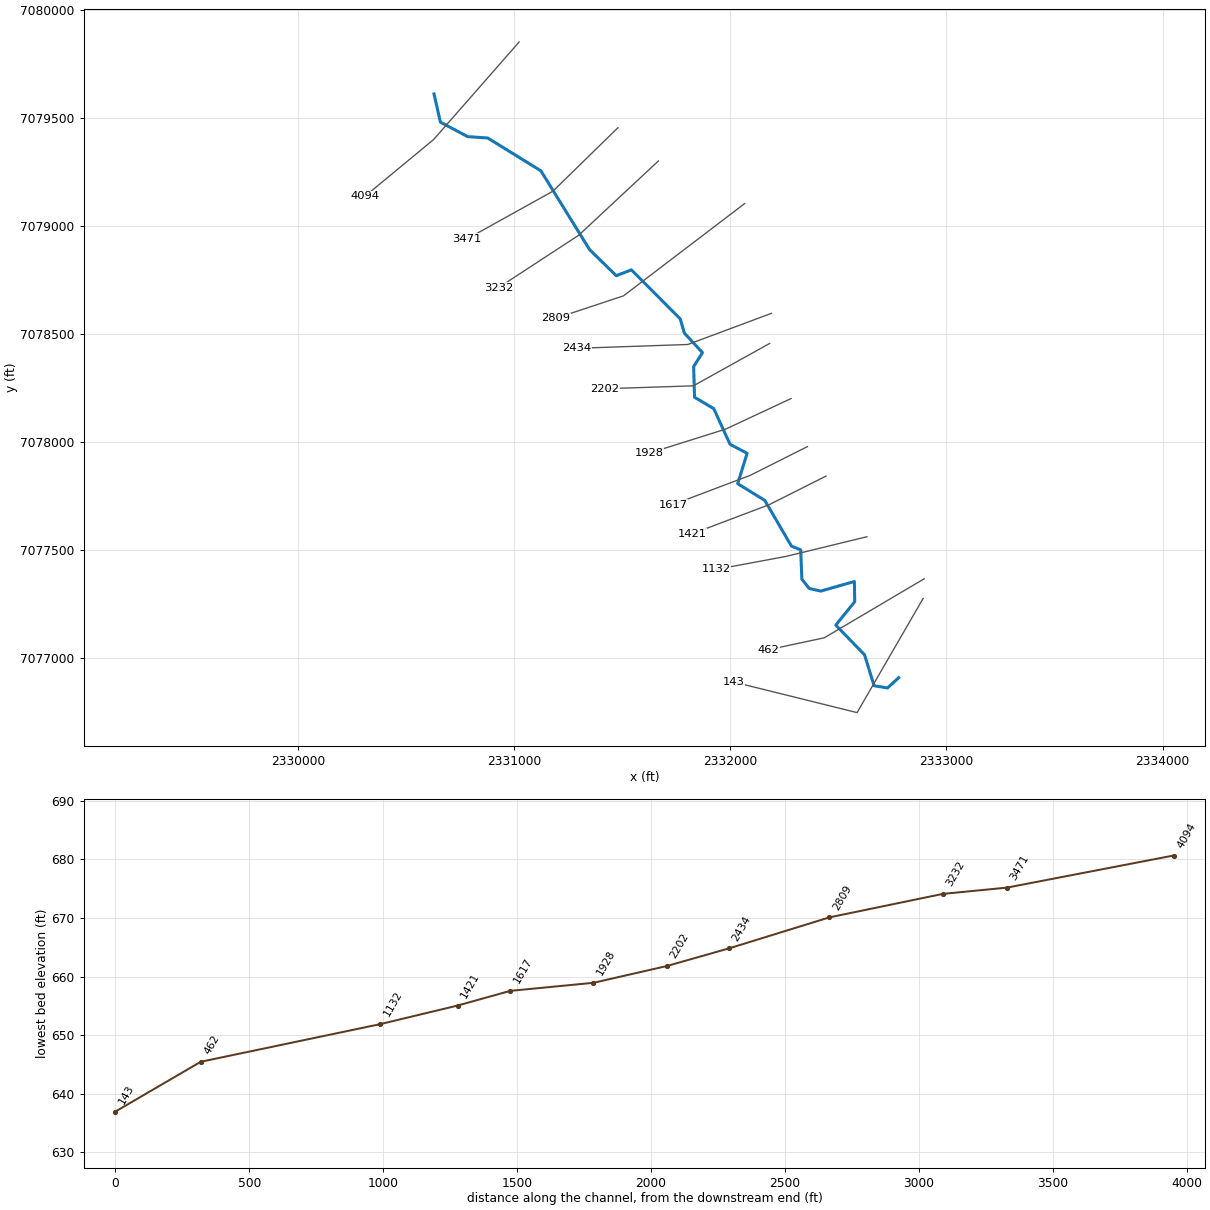
--- Trail Creek Tr 4.prj (project) ---

Proj Title=Trail Creek Tr 4 Base Level Engineering
Current Plan=p01
Default Exp/Contr=0.3,0.1
English Units
Geom File=g01
Flow File=f01
Plan File=p01
Y Axis Title=Elevation
X Axis Title(PF)=Main Channel Distance
X Axis Title(XS)=Station
BEGIN DESCRIPTION:
Trail Creek Tr 4
END DESCRIPTION:
DSS Export Rating Curves= 0
DSS Export Rating Curve Sorted= 0
DSS Export Volume Flow Curves= 0
DXF OffsetX= 0
DXF OffsetY= 0
DXF ScaleX= 1
DXF ScaleY= 10

--- Trail Creek Tr 4.p01 (plan) ---

Plan Title=Multiple Run
Program Version=4.10
Short Identifier=Multiple
Geom File=g01
Flow File=f01
Subcritical Flow
K Sum by GR= 0
Std Step Tol= 0.01
Critical Tol= 0.01
Num of Std Step Trials= 20
Max Error Tol= 0.3
Flow Tol Ratio= 0.001
Split Flow NTrial= 30
Split Flow Tol= 0.02
Split Flow Ratio= 0.02
Log Output Level= 0
Friction Slope Method= 1
Unsteady Friction Slope Method= 2
Unsteady Bridges Friction Slope Method= 1
Parabolic Critical Depth
Global Vel Dist= 1 , 1 , 1
Global Log Level= 0
CheckData=True
Encroach Param=-1 ,0,0, 0
BEGIN DESCRIPTION:
Multiple Run
END DESCRIPTION:
Computation Interval=1HOUR
Output Interval=1HOUR
Run HTab= 0
Run UNet= 0
Run PostProcess= 0
Run WQNet= 0
UNET Theta= 1
UNET Theta Warmup= 1
UNET ZTol= 0.02
UNET ZSATol= 0.05
UNET MxIter= 20
UNET MaxInSteps= 0
UNET DtIC= 0
UNET DtMin= 0
UNET MaxCRTS= 20
UNET WFStab= 2
UNET SFStab= 1
UNET WFX= 1
UNET SFX= 1
UNET DSS MLevel= 4
UNET DZMax Abort= 100
UNET Convert EG Bridges= 0
UNET Use Existing IB Tables=-1
UNET Froude Reduction=False
UNET Froude Limit= 1
UNET Froude Power= 10
UNET Time Slicing=0,0, 5
UNET Junction Losses=0
Instantaneous Interval=1HOUR
Write IC File= 0
Write IC File at Sim End=0
Echo Input=False
Echo Parameters=False
Echo Output=False
Write Detailed= 0
WQ AD Non Conservative
WQ ULTIMATE=-1
WQ Max Comp Step=1HOUR
WQ Output Interval=15MIN
WQ Output Selected Increments= 0
WQ Output face flow=0
WQ Output face velocity=0
WQ Output face area=0
WQ Output face dispersion=0
WQ Output cell volume=0
WQ Output cell surface area=0
WQ Output cell continuity=0
WQ Output cumulative cell continuity=0
WQ Output face conc=0
WQ Output face dconc_dx=0
WQ Output face courant=0
WQ Output face peclet=0
WQ Output face adv mass=0
WQ Output face disp mass=0
WQ Output cell mass=0
WQ Output cell source sink temp=0
WQ Output cell source sink nsm=0
WQ Output MaxMinRange=-1
WQ Daily Max Min Mean=-1
WQ Daily Range=0
WQ Daily Time=0
WQ Create Restart=0
WQ Fixed Restart=0
WQ System Summary=0
WQ Use Fixed Temperature=0
Sorting and Armoring Iterations= 10
XS Update Threshold= 0.02
Hydraulics Update Threshold= 0.02
Energy Slope Method= 1
Volume Change Method= 0
XS Weighting Method= 0
Number of US Weighted Cross Sections= 1
Number of DS Weighted Cross Sections= 1
Upstream XS Weight=0.25
Main XS Weight=0.5
Downstream XS Weight=0.25
Number of DS XS's Weighted with US Boundary= 1
Upstream Boundary Weight= 1
Weight of XSs Associated with US Boundary= 0
Number of US XS's Weighted with DS Boundary= 1
Downstream Boundary Weight= 0.5
Weight of XSs Associated with DS Boundary= 0.5
Sediment Output Level= 4
Mass or Volume Output= 0
Output Increment Type= 1
Profile and TS Output Increment= 10
XS Output Flag= 0
XS Output Increment= 10
Disregard all LS=0
Disregard all Conn=0
Disregard all Breaches=0
Disregard all Pumps=0

--- Trail Creek Tr 4.f01 (steady flow) ---

Flow Title=Multiple
Number of Profiles=7
Profile Names=10-year,25-year,50-year,1pct_min,100-year,1pct_plu,500-year
River Rch & RM= Trail Creek Tr 4,Reach-1,4094
     388     518     624     374     746    1488    1066
Boundary for River Rch & Prof#=Trail Creek Tr 4,Reach-1,1
Up Type=0
Dn Type=3
Dn Slope=0.005
Boundary for River Rch & Prof#=Trail Creek Tr 4,Reach-1,2
Up Type=0
Dn Type=3
Dn Slope=0.005
Boundary for River Rch & Prof#=Trail Creek Tr 4,Reach-1,3
Up Type=0
Dn Type=3
Dn Slope=0.005
Boundary for River Rch & Prof#=Trail Creek Tr 4,Reach-1,4
Up Type=0
Dn Type=3
Dn Slope=0.005
Boundary for River Rch & Prof#=Trail Creek Tr 4,Reach-1,5
Up Type=0
Dn Type=3
Dn Slope=0.005
Boundary for River Rch & Prof#=Trail Creek Tr 4,Reach-1,6
Up Type=0
Dn Type=3
Dn Slope=0.005
Boundary for River Rch & Prof#=Trail Creek Tr 4,Reach-1,7
Up Type=0
Dn Type=3
Dn Slope=0.005

--- Trail Creek Tr 4.g01 (geometry) ---

Geom Title=Existing Conditions
Program Version=4.10

River Reach=Trail Creek Tr 4,Reach-1
Reach XY= 30
        2330629.        7079610.      2330658.43      7079479.55
      2330784.96      7079412.33      2330877.42      7079406.17
      2331123.38      7079254.38      2331348.79      7078889.91
      2331472.33       7078769.3      2331542.33      7078796.35
      2331768.22      7078569.68       2331787.2      7078503.95
      2331871.19      7078413.41      2331830.38      7078349.56
      2331834.39      7078207.32      2331923.37      7078154.38
      2331998.74      7077989.57       2332077.8      7077947.98
      2332033.99      7077807.46      2332159.36      7077730.47
      2332282.94      7077518.66      2332325.59      7077501.56
      2332330.99      7077365.63      2332365.36      7077322.95
      2332418.24       7077310.7      2332574.05      7077355.04
      2332575.55      7077261.58      2332487.96      7077153.33
      2332621.14      7077016.17      2332665.33      7076872.95
      2332727.34      7076862.65        2332779.        7076910.

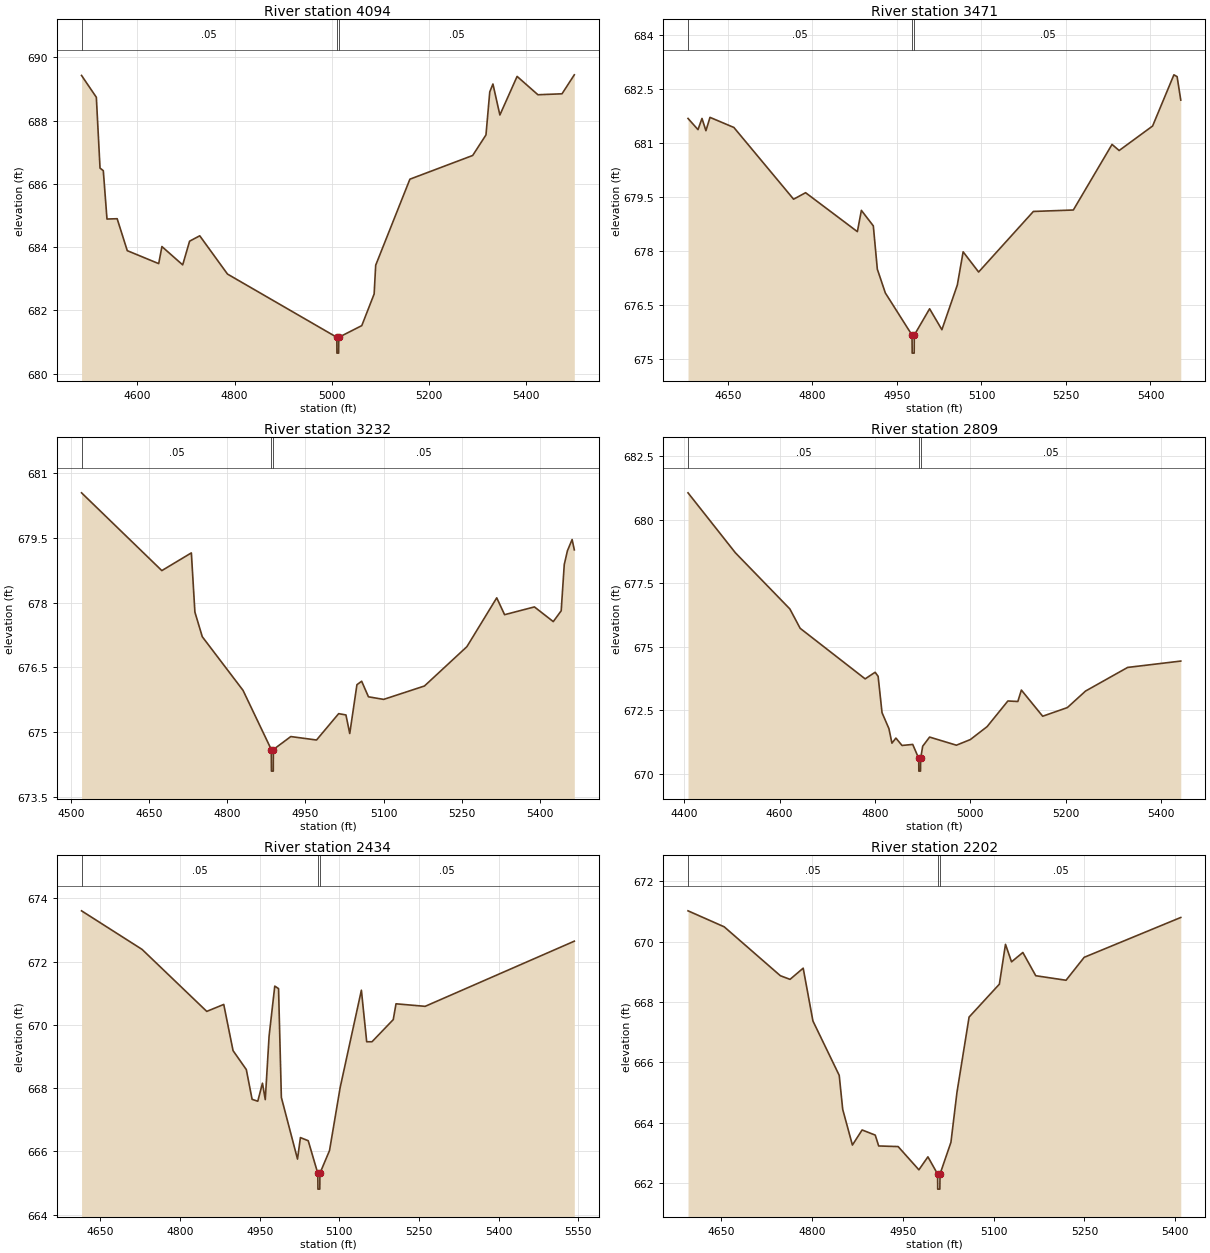
Type RM Length L Ch R = 1 ,4094    ,623,623,623
BEGIN DESCRIPTION:
Trail Creek Tr 4 9.0
END DESCRIPTION:
XS GIS Cut Line= 3
      2331022.44      7079849.76      2330627.26      7079399.12
      2330308.37      7079135.68
#Sta/Elev= 30
  4485.5  689.43  4515.9  688.74  4523.5   686.5  4530.2  686.42  4537.8  684.89
  4558.7   684.9  4579.5  683.89  4644.1  683.48  4650.7  684.02  4693.4  683.44
  4707.6  684.19  4728.5  684.36  4785.5  683.15  5010.3  681.15  5010.5  680.65
    5014  680.65  5014.3  681.15  5061.6  681.52    5087  682.52  5090.2  683.43
  5160.5  686.15  5289.6   686.9  5316.9  687.55  5324.7  688.91  5331.2  689.16
  5345.5  688.18  5380.9   689.4  5423.7  688.82  5473.2  688.85  5498.5  689.45
#Mann= 3 ,-1 , 0
  4485.5     .05       0  5010.3    .035       0  5014.3     .05       0
Bank Sta=5010.3,5014.3
XS Rating Curve= 0 ,0
Exp/Cntr=0.3,0.1

Type RM Length L Ch R = 1 ,3471    ,239,239,239
BEGIN DESCRIPTION:
Trail Creek Tr 4 8.0
END DESCRIPTION:
XS GIS Cut Line= 3
      2331480.19      7079453.89        2331179.        7079160.
      2330782.33      7078939.63
#Sta/Elev= 30
  4579.2  681.68  4596.9  681.37    4604  681.68    4611  681.34  4618.2  681.71
  4660.6  681.43  4766.6  679.44  4787.9  679.62  4879.8  678.54  4886.9  679.13
  4908.1   678.7  4915.2   677.5  4929.4  676.84  4976.8  675.67  4977.1  675.17
  4980.6  675.17  4980.8  675.67    5008   676.4  5029.8  675.82  5057.2  677.06
  5067.5  677.98    5095  677.42  5192.2   679.1  5263.1  679.14  5331.8  680.96
  5344.4  680.79  5403.8  681.47  5441.6  682.89  5447.3  682.84  5453.8  682.19
#Mann= 3 ,-1 , 0
  4579.2     .05       0  4976.8    .033       0  4980.8     .05       0
Bank Sta=4976.8,4980.8
XS Rating Curve= 0 ,0
Exp/Cntr=0.3,0.1

Type RM Length L Ch R = 1 ,3232    ,423,423,423
BEGIN DESCRIPTION:
Trail Creek Tr 4 7.0
END DESCRIPTION:
XS GIS Cut Line= 3
      2331667.12      7079299.84      2331298.35      7078956.33
      2330927.92      7078714.42
#Sta/Elev= 30
  4519.9  680.54  4674.1  678.74  4730.8  679.15  4737.6  677.78  4751.8  677.21
    4830  675.97  4884.3   674.6  4884.6   674.1  4888.1   674.1  4888.3   674.6
  4921.8   674.9  4971.2  674.82  5013.7  675.43  5027.7   675.4    5035  674.97
  5048.8   676.1  5057.9  676.18  5070.9  675.82  5100.1  675.76  5178.5  676.07
    5260  676.98  5317.3  678.11  5332.4  677.72  5389.7   677.9  5425.9  677.56
  5441.1  677.81    5447  678.88  5453.1   679.2  5462.1  679.46  5466.3  679.22
#Mann= 3 ,-1 , 0
  4519.9     .05       0  4884.3    .033       0  4888.3     .05       0
Bank Sta=4884.3,4888.3
XS Rating Curve= 0 ,0
Exp/Cntr=0.3,0.1

Type RM Length L Ch R = 1 ,2809    ,375,375,375
BEGIN DESCRIPTION:
Trail Creek Tr 4 6.0
END DESCRIPTION:
XS GIS Cut Line= 3
      2332066.17      7079102.81      2331505.47      7078675.97
      2331193.09      7078572.68
#Sta/Elev= 30
  4407.9  681.05  4507.3  678.69  4621.6  676.48  4643.1  675.72  4779.5  673.73
  4800.4  673.99  4806.7  673.83  4814.9   672.4  4829.4  671.77  4835.7   671.2
    4844   671.4  4856.8  671.11  4879.3  671.15  4891.9   670.6  4892.1   670.1
  4895.6   670.1  4895.9   670.6  4900.2  671.08  4914.7  671.44  4970.9  671.12
    5000  671.34  5035.3  671.85  5078.9  672.86  5099.8  672.84  5107.2  673.29
  5151.9  672.26  5203.7   672.6  5241.8  673.25  5330.1  674.18  5441.6  674.43
#Mann= 3 ,-1 , 0
  4407.9     .05       0  4891.9    .033       0  4895.9     .05       0
Bank Sta=4891.9,4895.9
XS Rating Curve= 0 ,0
Exp/Cntr=0.3,0.1

Type RM Length L Ch R = 1 ,2434    ,232,232,232
BEGIN DESCRIPTION:
Trail Creek Tr 4 5.0
END DESCRIPTION:
XS GIS Cut Line= 3
      2332189.98      7078595.15      2331803.51      7078451.17
      2331288.23      7078433.49
#Sta/Elev= 30
  4614.4  673.61  4728.4  672.39  4850.2  670.43  4882.2  670.65  4899.7  669.19
  4924.7  668.59  4935.6  667.65  4946.3  667.59  4955.1  668.16  4960.4  667.64
  4967.6  669.65  4978.3  671.23  4985.4  671.15  4990.7  667.71  5021.1  665.76
  5026.6  666.44  5041.3  666.34  5059.3  665.31  5059.6  664.81  5063.1  664.81
  5063.3  665.31  5081.4  666.03  5101.4  668.02  5141.4   671.1  5151.4  669.47
  5161.4  669.47  5201.4  670.17  5206.6  670.67  5261.5  670.59  5542.4  672.65
#Mann= 3 ,-1 , 0
  4614.4     .05       0  5059.3    .033       0  5063.3     .05       0
Bank Sta=5059.3,5063.3
XS Rating Curve= 0 ,0
Exp/Cntr=0.3,0.1

Type RM Length L Ch R = 1 ,2202    ,274,274,274
BEGIN DESCRIPTION:
Trail Creek Tr 4 4.0
END DESCRIPTION:
XS GIS Cut Line= 3
      2332182.37      7078456.21        2331829.        7078260.
      2331419.61      7078246.58
#Sta/Elev= 30
  4595.3  671.02  4655.1  670.49  4747.8  668.87  4763.8  668.75  4785.5  669.12
  4801.6  667.37    4845  665.57  4850.8  664.44  4866.8  663.26  4882.8  663.76
  4904.5  663.59  4910.2  663.23  4942.3  663.21  4976.6  662.44  4991.5  662.87
  5007.5   662.3  5007.7   661.8  5011.2   661.8  5011.5   662.3  5029.5  663.35
  5039.5  665.01  5059.5   667.5  5109.5  668.59  5119.6  669.91  5129.6  669.33
  5148.3  669.64  5169.6  668.87  5219.6  668.72  5249.6  669.48  5409.1   670.8
#Mann= 3 ,-1 , 0
  4595.3     .05       0  5007.5    .033       0  5011.5     .05       0
Bank Sta=5007.5,5011.5
XS Rating Curve= 0 ,0
Exp/Cntr=0.3,0.1

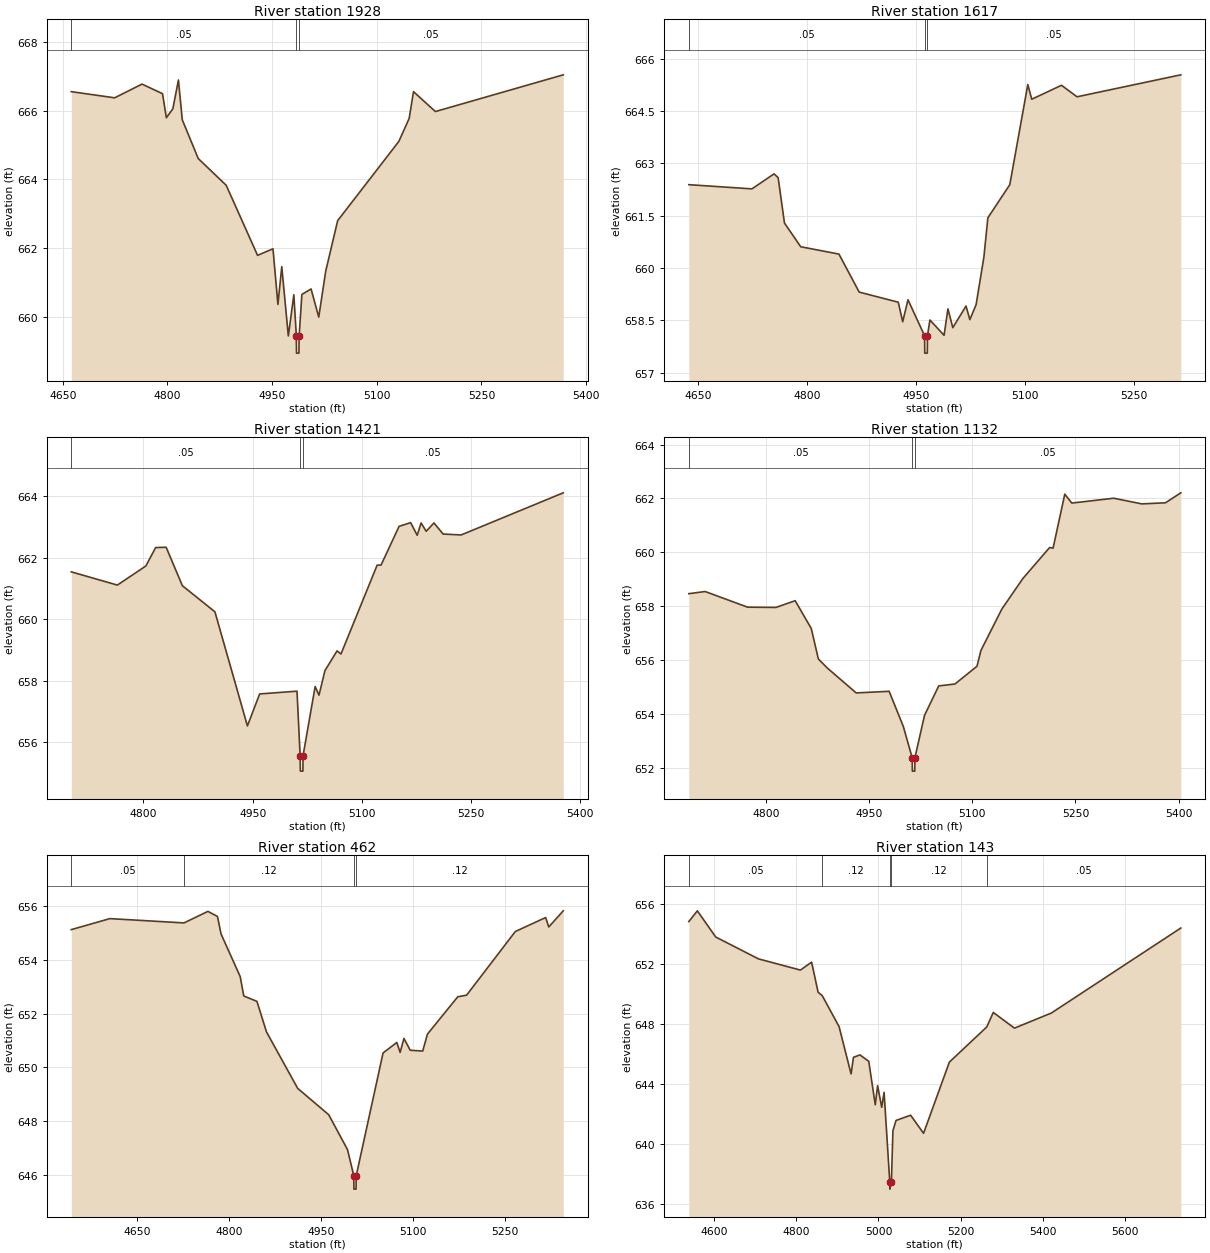
Type RM Length L Ch R = 1 ,1928    ,311,311,311
BEGIN DESCRIPTION:
Trail Creek Tr 4 3.0
END DESCRIPTION:
XS GIS Cut Line= 3
      2332280.87      7078201.11        2331979.        7078060.
      2331624.22      7077948.55
#Sta/Elev= 30
  4662.2  666.56  4724.4  666.38  4763.6  666.78    4793   666.5  4798.5   665.8
  4807.8  666.06  4815.8   666.9  4821.3  665.74  4844.2  664.61  4884.3  663.83
  4929.2  661.79  4951.3  661.98  4958.4  660.36  4963.9  661.46  4973.3  659.44
  4981.2  660.64  4984.8  659.44    4985  658.94  4988.5  658.94  4988.8  659.44
  4992.7  660.65  5005.9  660.81  5016.9  659.99  5026.9  661.33    5044   662.8
  5131.7  665.11  5146.5  665.78  5152.7  666.56  5184.1  665.98  5367.3  667.05
#Mann= 3 ,-1 , 0
  4662.2     .05       0  4984.8    .033       0  4988.8     .05       0
Bank Sta=4984.8,4988.8
XS Rating Curve= 0 ,0
Exp/Cntr=0.3,0.1

Type RM Length L Ch R = 1 ,1617    ,196,196,196
BEGIN DESCRIPTION:
Trail Creek Tr 4 2.5
END DESCRIPTION:
XS GIS Cut Line= 3
      2332356.68      7077978.86      2332093.12      7077846.39
      2331735.31      7077711.11
#Sta/Elev= 30
  4636.8  662.39  4723.7  662.27  4754.2   662.7  4759.8  662.59  4768.5  661.29
  4790.9  660.61  4843.5   660.4  4871.4  659.31  4925.2  659.02  4931.3  658.46
  4938.6  659.09  4961.4  658.06  4961.7  657.56  4965.2  657.56  4965.4  658.06
  4968.8  658.51  4988.3  658.07  4993.6  658.83  5000.3  658.29  5018.5  658.91
  5023.8  658.52  5032.4  658.95  5043.1  660.31  5048.6  661.44  5078.8  662.39
  5103.6  665.26    5109  664.84    5150  665.24  5171.4  664.91  5314.3  665.54
#Mann= 3 ,-1 , 0
  4636.8     .05       0  4961.4    .033       0  4965.4     .05       0
Bank Sta=4961.4,4965.4
XS Rating Curve= 0 ,0
Exp/Cntr=0.3,0.1

Type RM Length L Ch R = 1 ,1421    ,289,289,289
BEGIN DESCRIPTION:
Trail Creek Tr 4 2.0
END DESCRIPTION:
XS GIS Cut Line= 3
      2332442.54      7077842.46        2332179.        7077710.
      2331822.95      7077575.39
#Sta/Elev= 30
  4700.9  661.54  4764.2  661.11  4803.3  661.73  4816.8  662.33  4831.2  662.34
  4853.5  661.09  4898.2  660.24  4942.8  656.53  4959.6  657.57  5010.9  657.66
  5015.2  655.56  5015.5  655.06    5019  655.06  5019.2  655.56  5035.8  657.81
  5041.1  657.53  5049.3  658.33  5065.9  658.97  5071.3  658.87    5121  661.76
  5126.3  661.76  5151.1  663.02  5166.9  663.14    5176  662.73  5181.3  663.13
  5188.3  662.86    5199  663.13  5211.5  662.77  5236.3  662.74  5376.5  664.11
#Mann= 3 ,-1 , 0
  4700.9     .05       0  5015.2    .033       0  5019.2     .05       0
Bank Sta=5015.2,5019.2
XS Rating Curve= 0 ,0
Exp/Cntr=0.3,0.1

Type RM Length L Ch R = 1 ,1132    ,670,670,670
BEGIN DESCRIPTION:
Trail Creek Tr 4 1.0
END DESCRIPTION:
XS GIS Cut Line= 3
        2332632.       7077562.1      2332258.15      7077471.16
      2331933.17       7077410.7
#Sta/Elev= 30
    4688  658.47  4711.7  658.55  4773.4  657.97  4814.6  657.96  4842.6  658.21
    4866  657.18  4876.3  656.05  4889.5  655.71  4931.3  654.79  4979.2  654.85
  4999.8  653.55  5012.7  652.39    5013  651.89  5016.5  651.89  5016.7  652.39
  5030.7  653.96  5051.3  655.05  5074.9  655.12    5107  655.78  5112.6  656.36
  5143.1   657.9  5173.6  659.03  5212.5  660.18  5217.6  660.16  5234.6  662.16
  5244.8  661.83  5305.8  662.01  5346.5   661.8    5381  661.84  5403.3  662.21
#Mann= 3 ,-1 , 0
    4688     .05       0  5012.7    .033       0  5016.7     .05       0
Bank Sta=5012.7,5016.7
XS Rating Curve= 0 ,0
Exp/Cntr=0.3,0.1

Type RM Length L Ch R = 1 ,462     ,319,319,319
BEGIN DESCRIPTION:
Trail Creek Tr 4 0.7
END DESCRIPTION:
XS GIS Cut Line= 3
      2332897.22      7077367.63      2332434.96      7077094.82
      2332174.79      7077039.25
#Sta/Elev= 30
  4542.3  655.13  4605.3  655.54  4726.3  655.38  4765.3  655.81  4780.9  655.62
  4786.7  654.97    4818  653.38  4823.8  652.66  4845.3  652.46  4860.9  651.32
  4911.8  649.22  4962.4  648.24  4993.1  646.94  5003.3  645.97  5003.5  645.47
    5007  645.47  5007.3  645.97  5051.1  650.54  5073.6  650.93  5078.9  650.56
  5085.2  651.08  5095.4  650.64  5115.8  650.61  5123.5  651.24    5173  652.63
  5187.4  652.69  5266.9  655.06  5316.4  655.58  5321.5  655.23  5345.1  655.83
#Mann= 4 ,-1 , 0
  4542.3     .05       0  4726.3     .12       0  5003.3     .07       0
  5007.3     .12       0
Bank Sta=5003.3,5007.3
XS Rating Curve= 0 ,0
Exp/Cntr=0.3,0.1

Type RM Length L Ch R = 1 ,143     ,0,0,0
BEGIN DESCRIPTION:
Trail Creek Tr 4 0.4
END DESCRIPTION:
XS GIS Cut Line= 3
      2332892.14      7077276.69      2332586.51      7076748.79
      2332015.67      7076890.23
#Sta/Elev= 30
  4538.2  654.85  4558.9  655.57  4603.7  653.82  4707.7  652.36  4809.9  651.61
  4837.2  652.14    4853  650.13  4863.1   649.9  4904.1  647.83  4933.3  644.67
  4939.1  645.78  4954.9  645.94  4976.4  645.51  4992.2  642.61  4997.9  643.88
  5007.9  642.44  5013.7  643.44  5027.5  637.47  5027.7  636.97  5031.5  637.47
  5035.2  640.87  5042.8  641.56  5078.3  641.91  5109.8   640.7  5172.7  645.46
  5263.8  647.81  5279.6  648.78  5331.1  647.73  5421.1  648.74  5736.3  654.42
#Mann= 5 ,-1 , 0
  4538.2     .05       0  4863.1     .12       0  5027.5     .07       0
  5031.5     .12       0  5263.8     .05       0
Bank Sta=5027.5,5031.5
XS Rating Curve= 0 ,0
Exp/Cntr=0.3,0.1

Chan Stop Cuts=-1
Use User Specified Reach Order=0
Composite Channel Slope=5