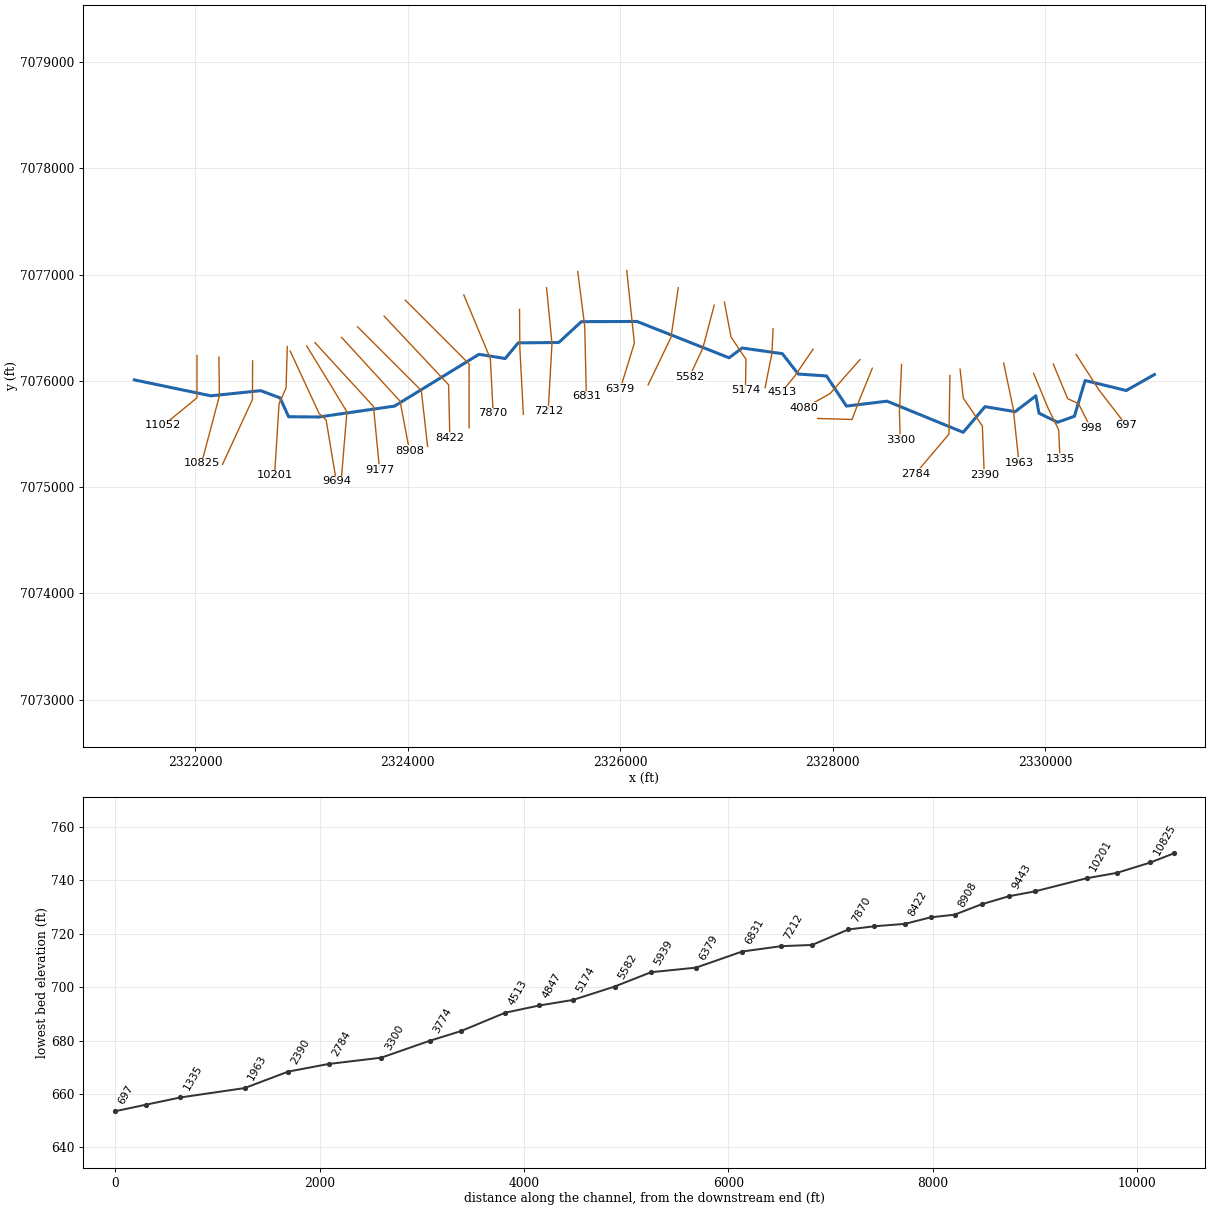
--- Trail Creek Tr 5.prj (project) ---

Proj Title=Trail Creek Tr 5 Base Level Engineering
Current Plan=p01
Default Exp/Contr=0.3,0.1
English Units
Geom File=g01
Flow File=f01
Plan File=p01
Y Axis Title=Elevation
X Axis Title(PF)=Main Channel Distance
X Axis Title(XS)=Station
BEGIN DESCRIPTION:
Trail Creek Tr 5
END DESCRIPTION:
DSS Export Rating Curves= 0
DSS Export Rating Curve Sorted= 0
DSS Export Volume Flow Curves= 0
DXF OffsetX= 0
DXF OffsetY= 0
DXF ScaleX= 1
DXF ScaleY= 10

--- Trail Creek Tr 5.p01 (plan) ---

Plan Title=Multiple Run
Program Version=4.10
Short Identifier=Multiple
Geom File=g01
Flow File=f01
Subcritical Flow
K Sum by GR= 0
Std Step Tol= 0.01
Critical Tol= 0.01
Num of Std Step Trials= 20
Max Error Tol= 0.3
Flow Tol Ratio= 0.001
Split Flow NTrial= 30
Split Flow Tol= 0.02
Split Flow Ratio= 0.02
Log Output Level= 0
Friction Slope Method= 1
Unsteady Friction Slope Method= 2
Unsteady Bridges Friction Slope Method= 1
Parabolic Critical Depth
Global Vel Dist= 1 , 1 , 1
Global Log Level= 0
CheckData=True
Encroach Param=-1 ,0,0, 0
BEGIN DESCRIPTION:
Multiple Run
END DESCRIPTION:
Computation Interval=1HOUR
Output Interval=1HOUR
Run HTab= 0
Run UNet= 0
Run PostProcess= 0
Run WQNet= 0
UNET Theta= 1
UNET Theta Warmup= 1
UNET ZTol= 0.02
UNET ZSATol= 0.05
UNET MxIter= 20
UNET MaxInSteps= 0
UNET DtIC= 0
UNET DtMin= 0
UNET MaxCRTS= 20
UNET WFStab= 2
UNET SFStab= 1
UNET WFX= 1
UNET SFX= 1
UNET DSS MLevel= 4
UNET DZMax Abort= 100
UNET Convert EG Bridges= 0
UNET Use Existing IB Tables=-1
UNET Froude Reduction=False
UNET Froude Limit= 1
UNET Froude Power= 10
UNET Time Slicing=0,0, 5
UNET Junction Losses=0
Instantaneous Interval=1HOUR
Write IC File= 0
Write IC File at Sim End=0
Echo Input=False
Echo Parameters=False
Echo Output=False
Write Detailed= 0
WQ AD Non Conservative
WQ ULTIMATE=-1
WQ Max Comp Step=1HOUR
WQ Output Interval=15MIN
WQ Output Selected Increments= 0
WQ Output face flow=0
WQ Output face velocity=0
WQ Output face area=0
WQ Output face dispersion=0
WQ Output cell volume=0
WQ Output cell surface area=0
WQ Output cell continuity=0
WQ Output cumulative cell continuity=0
WQ Output face conc=0
WQ Output face dconc_dx=0
WQ Output face courant=0
WQ Output face peclet=0
WQ Output face adv mass=0
WQ Output face disp mass=0
WQ Output cell mass=0
WQ Output cell source sink temp=0
WQ Output cell source sink nsm=0
WQ Output MaxMinRange=-1
WQ Daily Max Min Mean=-1
WQ Daily Range=0
WQ Daily Time=0
WQ Create Restart=0
WQ Fixed Restart=0
WQ System Summary=0
WQ Use Fixed Temperature=0
Sorting and Armoring Iterations= 10
XS Update Threshold= 0.02
Hydraulics Update Threshold= 0.02
Energy Slope Method= 1
Volume Change Method= 0
XS Weighting Method= 0
Number of US Weighted Cross Sections= 1
Number of DS Weighted Cross Sections= 1
Upstream XS Weight=0.25
Main XS Weight=0.5
Downstream XS Weight=0.25
Number of DS XS's Weighted with US Boundary= 1
Upstream Boundary Weight= 1
Weight of XSs Associated with US Boundary= 0
Number of US XS's Weighted with DS Boundary= 1
Downstream Boundary Weight= 0.5
Weight of XSs Associated with DS Boundary= 0.5
Sediment Output Level= 4
Mass or Volume Output= 0
Output Increment Type= 1
Profile and TS Output Increment= 10
XS Output Flag= 0
XS Output Increment= 10
Disregard all LS=0
Disregard all Conn=0
Disregard all Breaches=0
Disregard all Pumps=0

--- Trail Creek Tr 5.f01 (steady flow) ---

Flow Title=Multiple
Number of Profiles=7
Profile Names=10-year,25-year,50-year,1pct_min,100-year,1pct_plu,500-year
River Rch & RM= Trail Creek Tr 5,Reach-1,11052
     365     485     582     347     693    1383     984
River Rch & RM= Trail Creek Tr 5,Reach-1,6379
     415     557     672     403     804    1605    1154
River Rch & RM= Trail Creek Tr 5,Reach-1,3300
     758    1057    1307     803    1602    3196    2410
River Rch & RM= Trail Creek Tr 5,Reach-1,2390
     937    1321    1647    1018    2032    4054    3101
River Rch & RM= Trail Creek Tr 5,Reach-1,998
     974    1375    1717    1062    2120    4230    3242
Boundary for River Rch & Prof#=Trail Creek Tr 5,Reach-1,1
Up Type=0
Dn Type=3
Dn Slope=0.005
Boundary for River Rch & Prof#=Trail Creek Tr 5,Reach-1,2
Up Type=0
Dn Type=3
Dn Slope=0.005
Boundary for River Rch & Prof#=Trail Creek Tr 5,Reach-1,3
Up Type=0
Dn Type=3
Dn Slope=0.005
Boundary for River Rch & Prof#=Trail Creek Tr 5,Reach-1,4
Up Type=0
Dn Type=3
Dn Slope=0.005
Boundary for River Rch & Prof#=Trail Creek Tr 5,Reach-1,5
Up Type=0
Dn Type=3
Dn Slope=0.005
Boundary for River Rch & Prof#=Trail Creek Tr 5,Reach-1,6
Up Type=0
Dn Type=3
Dn Slope=0.005
Boundary for River Rch & Prof#=Trail Creek Tr 5,Reach-1,7
Up Type=0
Dn Type=3
Dn Slope=0.005

--- Trail Creek Tr 5.g01 (geometry) ---

Geom Title=Existing Conditions
Program Version=4.10

River Reach=Trail Creek Tr 5,Reach-1
Reach XY= 30
        2321429.        7076010.      2322149.03      7075860.07
       2322618.5      7075908.78      2322799.64      7075840.57
      2322880.22      7075663.44      2323163.78      7075660.52
      2323877.53      7075763.55      2324672.26      7076250.87
      2324918.57      7076211.04      2325040.83      7076358.38
      2325423.15      7076362.06      2325634.85      7076557.94
      2326159.12      7076560.07      2327025.78      7076217.88
      2327149.05       7076310.2      2327527.55      7076256.47
       2327676.3      7076065.36      2327942.67      7076046.78
      2328130.45      7075763.52      2328512.99      7075809.76
        2329229.      7075516.59      2329434.97      7075758.07
      2329718.56      7075711.05      2329913.25      7075859.95
      2329942.36      7075696.66      2330118.45       7075611.1
      2330276.07      7075667.97      2330376.46       7076004.3
      2330763.61      7075910.07        2331029.        7076060.

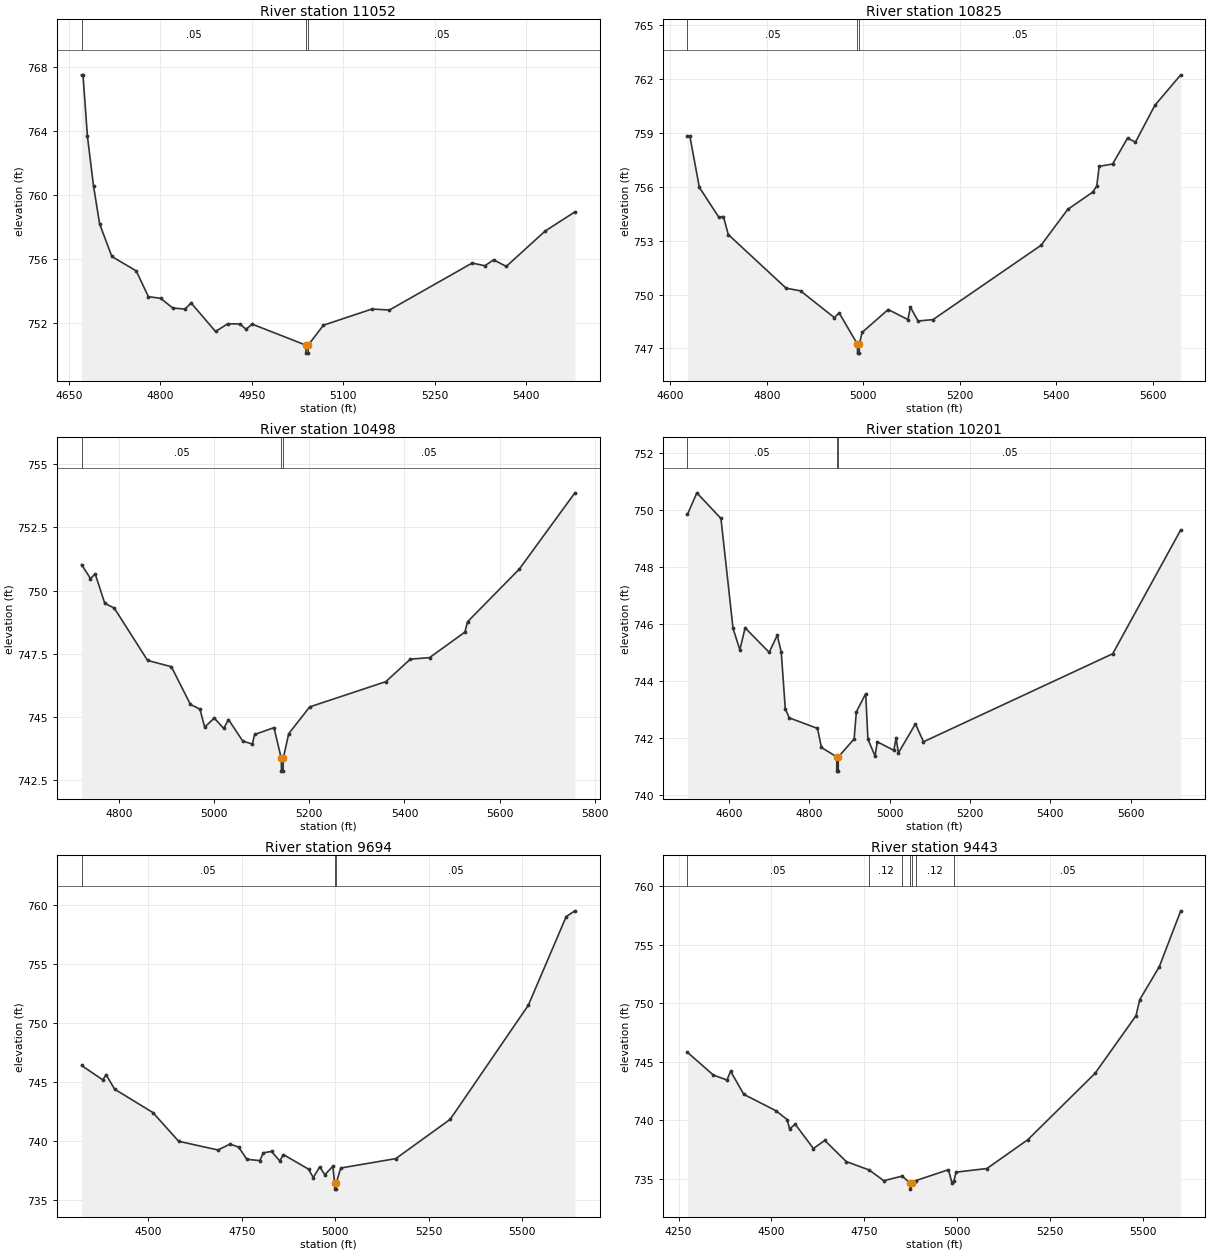
Type RM Length L Ch R = 1 ,11052   ,227,227,227
BEGIN DESCRIPTION:
Trail Creek Tr 5 27.0
END DESCRIPTION:
XS GIS Cut Line= 3
      2322017.81       7076239.6      2322017.81       7075841.4
      2321700.42      7075580.91
#Sta/Elev= 30
  4670.7   767.5    4673   767.5  4680.3  763.66  4690.3  760.56  4700.3   758.2
  4720.3  756.17  4760.3  755.27  4780.3  753.66  4800.3  753.56  4820.3  752.95
  4840.3  752.89  4850.3  753.27  4890.3  751.49  4910.3  751.97  4930.3  751.96
  4940.3  751.63  4950.3  751.95  5038.3  750.64  5038.6  750.14  5042.1  750.14
  5042.3  750.64  5067.1  751.88  5146.7  752.89  5175.4  752.83  5311.1  755.76
  5331.9  755.59  5346.2  755.96    5367  755.55  5430.9  757.76  5479.5  758.95
#Mann= 3 ,-1 , 0
  4670.7     .05       0  5038.3    .033       0  5042.3     .05       0
Bank Sta=5038.3,5042.3
XS Rating Curve= 0 ,0
Exp/Cntr=0.3,0.1

Type RM Length L Ch R = 1 ,10825   ,327,327,327
BEGIN DESCRIPTION:
Trail Creek Tr 5 26.0
END DESCRIPTION:
XS GIS Cut Line= 3
      2322224.39      7076224.67        2322229.        7075860.
      2322060.16       7075223.3
#Sta/Elev= 30
  4635.2  758.85  4640.1  758.85  4659.9  755.98  4699.9  754.33  4709.9  754.35
  4719.9  753.35  4839.9  750.36  4869.9  750.21  4939.9  748.72  4949.9  748.98
  4987.9  747.24  4988.1  746.74  4991.6  746.74  4991.9  747.24  4997.4  747.89
  5051.6  749.17  5092.6  748.61  5097.8   749.3  5113.7  748.53  5144.7  748.61
  5368.8  752.75  5424.1  754.75  5475.8  755.71  5484.3  756.05  5489.4  757.15
  5517.2  757.28  5548.2  758.72  5564.7   758.5  5604.9  760.55  5658.6  762.25
#Mann= 3 ,-1 , 0
  4635.2     .05       0  4987.9    .033       0  4991.9     .05       0
Bank Sta=4987.9,4991.9
XS Rating Curve= 0 ,0
Exp/Cntr=0.3,0.1

Type RM Length L Ch R = 1 ,10498   ,297,297,297
BEGIN DESCRIPTION:
Trail Creek Tr 5 25.0
END DESCRIPTION:
XS GIS Cut Line= 3
      2322541.74      7076188.67      2322539.53      7075824.92
      2322257.87      7075213.87
#Sta/Elev= 30
  4721.5  751.03  4740.2  750.48  4750.2  750.66  4770.2   749.5  4790.2  749.31
  4860.2  747.24  4910.2  746.99  4950.2   745.5  4970.2  745.31  4980.2   744.6
  5000.2  744.96  5020.2  744.55  5030.2   744.9  5060.2  744.05  5080.2  743.93
  5085.2  744.31  5125.8  744.58  5141.2  743.36  5141.5  742.86    5145  742.86
  5145.2  743.36  5156.7  744.34  5200.8   745.4  5360.8   746.4  5412.3  747.29
  5452.7  747.35    5527  748.36  5532.5  748.77  5641.2  750.85  5758.1  753.87
#Mann= 3 ,-1 , 0
  4721.5     .05       0  5141.2    .033       0  5145.2     .05       0
Bank Sta=5141.2,5145.2
XS Rating Curve= 0 ,0
Exp/Cntr=0.3,0.1

Type RM Length L Ch R = 1 ,10201   ,507,507,507
BEGIN DESCRIPTION:
Trail Creek Tr 5 24.5
END DESCRIPTION:
XS GIS Cut Line= 4
      2322868.08       7076323.4       2322856.1      7075934.21
      2322790.23      7075784.52      2322748.32      7075110.94
#Sta/Elev= 30
  4496.7  749.85  4520.1  750.61  4580.1  749.71  4610.2  745.85  4627.2   745.1
  4640.2  745.87  4700.2  745.01  4720.2  745.61  4730.2  745.02  4740.2  743.03
  4750.2  742.71  4820.3  742.34  4830.3  741.67  4868.3  741.34  4868.5  740.84
    4872  740.84  4872.3  741.34  4911.6  741.97  4917.1  742.92  4940.4  743.56
  4945.9  741.96  4963.7  741.37  4969.2  741.87  5010.4  741.57  5015.9     742
  5021.8  741.48  5064.2   742.5  5084.2  741.87  5555.1  744.96  5724.5  749.31
#Mann= 3 ,-1 , 0
  4496.7     .05       0  4868.3    .033       0  4872.3     .05       0
Bank Sta=4868.3,4872.3
XS Rating Curve= 0 ,0
Exp/Cntr=0.3,0.1

Type RM Length L Ch R = 1 ,9694    ,251,251,251
BEGIN DESCRIPTION:
Trail Creek Tr 5 24.0
END DESCRIPTION:
XS GIS Cut Line= 4
      2322895.03      7076281.49      2323166.09      7075696.38
      2323233.33      7075631.83      2323329.13      7075057.02
#Sta/Elev= 30
  4320.9   746.4  4377.7  745.18  4386.5  745.62  4409.4  744.39  4512.1   742.4
  4580.8  739.97  4686.2  739.23  4718.3  739.73  4741.3  739.48  4763.4  738.44
  4798.1  738.33  4807.5  738.99  4829.5  739.11  4851.6   738.3  4861.3  738.84
  4928.7   737.6  4941.1  736.89  4958.5   737.8  4972.2  737.13  4993.6  737.85
  4998.5  736.41  4998.8  735.91  5002.3  735.91  5002.5  736.41  5014.7   737.7
  5162.2   738.5  5307.8  741.83    5517  751.51  5618.4  759.03  5641.7  759.52
#Mann= 3 ,-1 , 0
  4320.9     .05       0  4998.5    .035       0  5002.5     .05       0
Bank Sta=4998.5,5002.5
XS Rating Curve= 0 ,0
Exp/Cntr=0.3,0.1

Type RM Length L Ch R = 1 ,9443    ,266,266,266
BEGIN DESCRIPTION:
Trail Creek Tr 5 23.0
END DESCRIPTION:
XS GIS Cut Line= 3
      2323050.69      7076329.43        2323429.        7075710.
        2323379.        7075110.
#Sta/Elev= 30
  4273.8  745.81  4343.5  743.87  4380.3  743.44  4389.9   744.2  4425.5  742.22
  4511.9  740.82  4542.6  740.05  4548.6  739.27  4564.1  739.66  4612.9  737.59
  4643.5  738.28  4701.5  736.47  4762.8  735.76  4802.2  734.84  4851.8  735.23
  4873.7  734.62    4874  734.12  4877.7  734.62  4887.8  734.84  4976.4  735.78
    4986  734.63  4991.4  734.84  4996.7  735.57  5079.9  735.88  5190.3  738.35
  5370.9  744.01  5481.3  748.94  5491.3  750.31    5544  753.13  5601.7   757.9
#Mann= 7 ,-1 , 0
  4273.8     .05       0  4762.8     .12       0  4851.8     .05       0
  4873.7    .035       0  4877.7     .05       0  4887.8     .12       0
  4991.4     .05       0
Bank Sta=4873.7,4877.7
XS Rating Curve= 0 ,0
Exp/Cntr=0.3,0.1

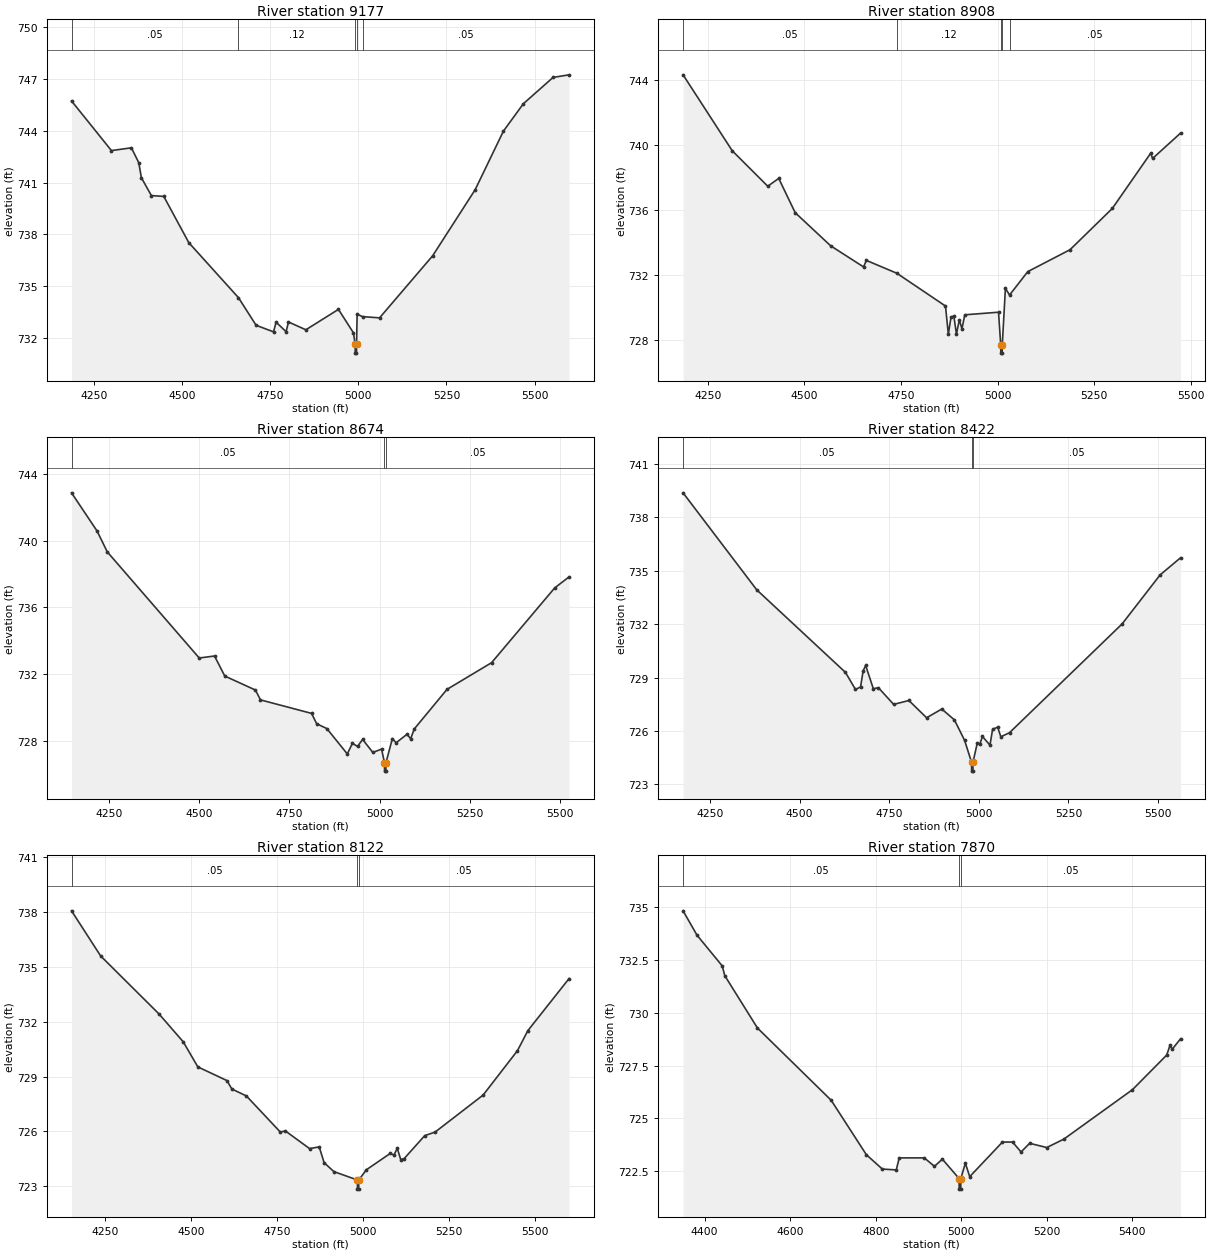
Type RM Length L Ch R = 1 ,9177    ,269,269,269
BEGIN DESCRIPTION:
Trail Creek Tr 5 22.0
END DESCRIPTION:
XS GIS Cut Line= 3
        2323129.        7076360.        2323679.        7075760.
      2323736.29      7075164.89
#Sta/Elev= 30
  4186.1  745.72  4299.3  742.85    4356  743.01  4376.9  742.15  4384.3  741.28
  4412.7  740.25  4447.9   740.2  4518.8  737.53  4659.7  734.35  4709.9  732.75
  4759.3  732.37  4766.6  732.93    4795  732.38  4801.8  732.94  4851.1  732.49
  4943.6  733.67  4986.2  732.31    4991  731.64  4991.2  731.14  4994.7  731.14
    4995  731.64  4996.6  733.39  5011.9  733.25  5060.3  733.18    5211  736.77
  5331.6  740.59  5411.9  743.98  5468.4  745.56  5552.6  747.08  5597.9  747.23
#Mann= 5 ,-1 , 0
  4186.1     .05       0  4659.7     .12       0    4991     .07       0
    4995     .12       0  5011.9     .05       0
Bank Sta=4991,4995
XS Rating Curve= 0 ,0
Exp/Cntr=0.3,0.1

Type RM Length L Ch R = 1 ,8908    ,234,234,234
BEGIN DESCRIPTION:
Trail Creek Tr 5 21.0
END DESCRIPTION:
XS GIS Cut Line= 3
      2323378.97      7076410.03        2323929.        7075810.
      2324017.67      7075344.75
#Sta/Elev= 30
    4186  744.32  4313.4  739.64  4405.2  737.46  4433.6  737.94  4476.2  735.83
    4568  733.79  4653.1  732.49  4660.5  732.89  4739.3   732.1  4865.2  730.08
  4872.6  728.35  4879.4  729.38  4886.8  729.47  4893.6  728.35    4901  729.23
  4907.8  728.68  4915.2  729.54  5002.5   729.7  5008.2  727.68  5008.4  727.18
  5011.9  727.18  5012.2  727.68  5020.3  731.17  5031.1  730.76  5078.2   732.2
  5187.6  733.55    5297  736.09  5396.3  739.49  5401.3  739.17  5473.6  740.73
#Mann= 5 ,-1 , 0
    4186     .05       0  4739.3     .12       0  5008.2     .07       0
  5012.2     .12       0  5031.1     .05       0
Bank Sta=5008.2,5012.2
XS Rating Curve= 0 ,0
Exp/Cntr=0.3,0.1

Type RM Length L Ch R = 1 ,8674    ,252,252,252
BEGIN DESCRIPTION:
Trail Creek Tr 5 20.0
END DESCRIPTION:
XS GIS Cut Line= 3
      2323528.97      7076510.03        2324129.        7075910.
      2324188.29       7075384.2
#Sta/Elev= 30
    4147  742.87  4217.7  740.58    4246  739.33  4500.6  732.97    4543  733.09
  4571.3  731.89  4656.2  731.05  4670.3  730.46  4811.7  729.65  4825.9  729.03
  4854.1  728.74  4910.7  727.22  4924.9  727.86    4939  727.67  4953.1  728.09
  4981.4  727.31  5005.6  727.51  5013.7  726.69  5013.9  726.19  5017.4  726.19
  5017.7  726.69  5035.5  728.14  5045.9  727.89  5076.1   728.4  5086.1  728.13
  5096.2  728.72  5186.8  731.09  5310.3  732.69    5485  737.17  5524.7  737.83
#Mann= 3 ,-1 , 0
    4147     .05       0  5013.7    .033       0  5017.7     .05       0
Bank Sta=5013.7,5017.7
XS Rating Curve= 0 ,0
Exp/Cntr=0.3,0.1

Type RM Length L Ch R = 1 ,8422    ,300,300,300
BEGIN DESCRIPTION:
Trail Creek Tr 5 19.0
END DESCRIPTION:
XS GIS Cut Line= 3
      2323778.99      7076610.01      2324385.98      7075964.15
      2324397.91      7075463.12
#Sta/Elev= 30
  4175.2  739.38  4380.6  733.93  4628.1  729.29  4656.1  728.33  4670.2  728.47
  4677.5  729.38  4684.4  729.68  4705.9  728.37    4720  728.43  4762.5  727.49
    4805  727.71  4854.4  726.74  4896.8  727.23    4932  726.62  4960.4  725.47
  4979.8  724.24  4980.1  723.74  4983.6  723.74  4983.8  724.24    4996  725.34
  5002.8  725.24  5010.1  725.69  5031.2   725.2  5038.5  726.09  5052.6  726.21
  5061.5  725.67  5085.7   725.9  5399.6  732.01  5505.8  734.77  5562.7  735.73
#Mann= 3 ,-1 , 0
  4175.2     .05       0  4979.8    .033       0  4983.8     .05       0
Bank Sta=4979.8,4983.8
XS Rating Curve= 0 ,0
Exp/Cntr=0.3,0.1

Type RM Length L Ch R = 1 ,8122    ,252,252,252
BEGIN DESCRIPTION:
Trail Creek Tr 5 18.0
END DESCRIPTION:
XS GIS Cut Line= 3
      2323979.01      7076759.99        2324579.        7076160.
        2324579.      7075560.02
#Sta/Elev= 30
  4151.2  738.07    4236   735.6  4405.7  732.43  4476.5   730.9  4518.9  729.53
  4603.7  728.78  4617.9  728.32  4660.3  727.94  4759.3  725.96  4773.4  726.03
  4844.2  725.06  4872.4  725.15  4886.6  724.29  4914.9   723.8  4983.6  723.34
  4983.8  722.84  4987.3  722.84  4987.6  723.34  5009.7   723.9  5079.7   724.8
  5089.7   724.7  5099.7  725.07  5109.7  724.46  5119.7  724.51  5179.7  725.77
  5209.7  725.96  5349.7  727.99  5449.7  730.42  5479.7  731.51  5599.7  734.36
#Mann= 3 ,-1 , 0
  4151.2     .05       0  4983.6    .033       0  4987.6     .05       0
Bank Sta=4983.6,4987.6
XS Rating Curve= 0 ,0
Exp/Cntr=0.3,0.1

Type RM Length L Ch R = 1 ,7870    ,355,355,355
BEGIN DESCRIPTION:
Trail Creek Tr 5 17.0
END DESCRIPTION:
XS GIS Cut Line= 3
      2324528.99      7076810.03        2324779.        7076210.
      2324805.13       7075697.7
#Sta/Elev= 30
  4349.6  734.83  4382.1  733.68  4441.2  732.22  4447.1  731.76  4523.5  729.28
  4695.8  725.86  4778.1  723.28  4815.5   722.6    4848  722.56    4855  723.13
  4913.5  723.13  4937.3  722.73  4955.8  723.07  4994.9  722.15  4995.2  721.65
  4998.7  721.65  4998.9  722.15  5009.6  722.88  5019.7  722.24  5096.3  723.88
  5119.8  723.88  5139.8  723.41  5159.8  723.82  5199.9  723.62  5239.9  724.02
  5400.2  726.36  5480.3     728  5487.9  728.46  5492.9  728.27  5512.6  728.77
#Mann= 3 ,-1 , 0
  4349.6     .05       0  4994.9    .033       0  4998.9     .05       0
Bank Sta=4994.9,4998.9
XS Rating Curve= 0 ,0
Exp/Cntr=0.3,0.1

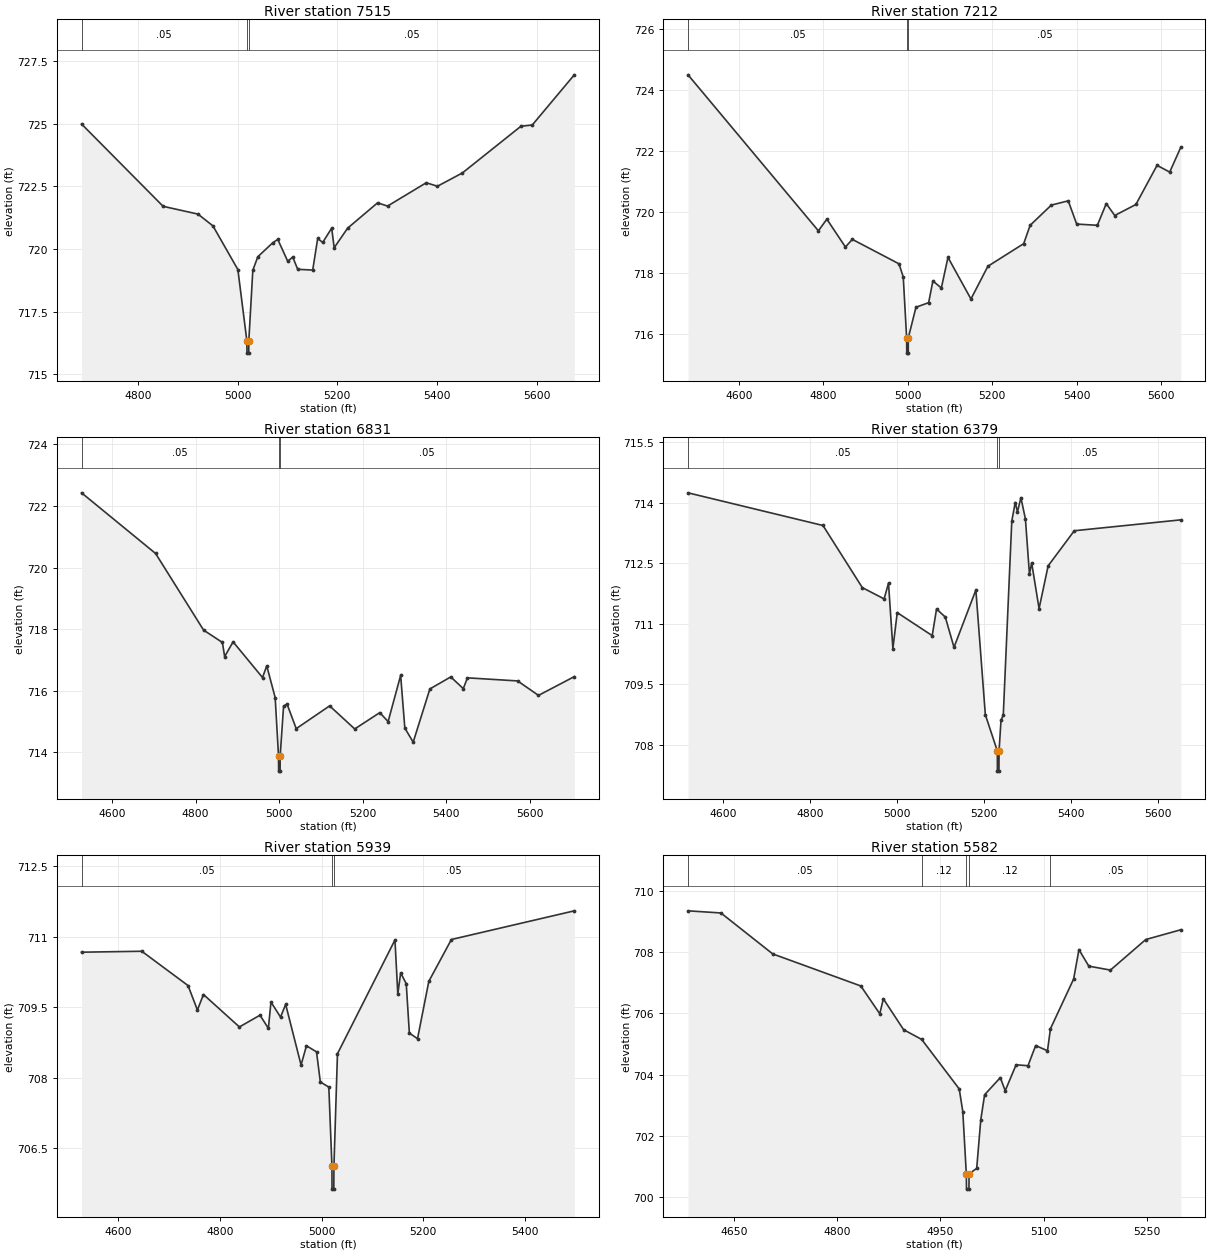
Type RM Length L Ch R = 1 ,7515    ,303,303,303
BEGIN DESCRIPTION:
Trail Creek Tr 5 16.0
END DESCRIPTION:
XS GIS Cut Line= 3
      2325053.62      7076673.72      2325056.61      7076308.45
      2325089.55      7075685.71
#Sta/Elev= 30
  4686.7  724.98  4850.4   721.7  4920.4  721.39  4950.4  720.92  5000.4  719.18
  5018.4  716.35  5018.7  715.85  5022.2  715.85  5022.4  716.35  5030.4  719.15
  5040.4  719.69  5070.5  720.25  5080.5  720.38  5100.5  719.51  5110.5  719.68
  5120.5  719.19  5150.6  719.16  5160.6  720.42  5170.6  720.26  5188.7  720.83
  5193.7  720.05  5220.7  720.83  5280.8  721.84  5300.8  721.71  5378.5  722.64
  5400.9   722.5    5451  723.03  5568.4  724.89  5591.2  724.94  5675.6  726.94
#Mann= 3 ,-1 , 0
  4686.7     .05       0  5018.4    .035       0  5022.4     .05       0
Bank Sta=5018.4,5022.4
XS Rating Curve= 0 ,0
Exp/Cntr=0.3,0.1

Type RM Length L Ch R = 1 ,7212    ,381,381,381
BEGIN DESCRIPTION:
Trail Creek Tr 5 15.0
END DESCRIPTION:
XS GIS Cut Line= 3
       2325308.1       7076877.3      2325359.02      7076353.09
      2325323.14      7075713.87
#Sta/Elev= 30
    4480  724.49  4788.7  719.39  4808.8  719.77  4852.7  718.86  4869.1  719.11
  4979.6  718.31  4989.7  717.88  4997.7  715.89    4998  715.39  5001.5  715.39
  5001.7  715.89  5019.8  716.89  5049.8  717.04  5059.9  717.75  5079.9  717.52
  5095.6  718.52    5150  717.16  5190.1  718.23  5274.9  718.97  5290.2  719.57
  5340.3  720.23  5380.4  720.37  5400.4  719.61  5449.3  719.57  5470.5  720.28
  5490.5  719.89  5540.6  720.25  5590.7  721.53  5620.7  721.31  5646.9  722.12
#Mann= 3 ,-1 , 0
    4480     .05       0  4997.7    .035       0  5001.7     .05       0
Bank Sta=4997.7,5001.7
XS Rating Curve= 0 ,0
Exp/Cntr=0.3,0.1

Type RM Length L Ch R = 1 ,6831    ,452,452,452
BEGIN DESCRIPTION:
Trail Creek Tr 5 14.0
END DESCRIPTION:
XS GIS Cut Line= 3
      2325601.51      7077029.96      2325667.37      7076512.03
      2325682.32       7075854.2
#Sta/Elev= 30
  4526.7  722.43    4704  720.46    4819  717.97    4864  717.57  4869.4  717.11
  4889.6  717.59  4960.1  716.43  4970.2  716.81  4990.4  715.78  4998.4  713.89
  4998.7  713.39  5002.2  713.39  5002.4  713.89  5010.5   715.5  5018.8  715.57
  5040.8  714.77  5120.8  715.51  5180.9  714.76  5240.9  715.29  5260.9     715
  5290.9   716.5  5300.9  714.79  5320.9  714.33  5360.9  716.06  5410.9  716.45
  5440.9  716.07  5450.9  716.42    5571  716.32    5621  715.85  5706.8  716.46
#Mann= 3 ,-1 , 0
  4526.7     .05       0  4998.4    .035       0  5002.4     .05       0
Bank Sta=4998.4,5002.4
XS Rating Curve= 0 ,0
Exp/Cntr=0.3,0.1

Type RM Length L Ch R = 1 ,6379    ,440,440,440
BEGIN DESCRIPTION:
Trail Creek Tr 5 13.0
END DESCRIPTION:
XS GIS Cut Line= 3
      2326062.56      7077038.96      2326134.42      7076356.35
      2326002.69      7075928.24
#Sta/Elev= 30
  4518.7  714.25  4829.4  713.44  4919.9   711.9  4970.1  711.62  4980.2  712.01
  4990.3  710.39  5000.3  711.28  5080.8  710.71  5090.8  711.37  5110.9  711.17
    5131  710.42  5181.3  711.84  5203.1  708.75  5230.7  707.85  5230.9  707.35
  5234.4  707.35  5234.7  707.85  5239.2  708.61  5244.4  708.74    5264  713.55
  5271.9  714.01  5277.1  713.78    5285  714.13  5295.4   713.6  5304.6  712.24
  5309.8  712.51  5326.8  711.38  5347.7  712.44  5407.9  713.31    5653  713.58
#Mann= 3 ,-1 , 0
  4518.7     .05       0  5230.7    .033       0  5234.7     .05       0
Bank Sta=5230.7,5234.7
XS Rating Curve= 0 ,0
Exp/Cntr=0.3,0.1

Type RM Length L Ch R = 1 ,5939    ,357,357,357
BEGIN DESCRIPTION:
Trail Creek Tr 5 12.0
END DESCRIPTION:
XS GIS Cut Line= 3
      2326547.57      7076877.26        2326479.        7076410.
      2326263.59      7075962.06
#Sta/Elev= 30
  4527.7  710.67  4646.2  710.69  4737.2  709.96  4755.6  709.44  4767.5  709.77
  4838.2  709.08  4878.7  709.33  4895.2  709.05  4900.3  709.61  4919.1  709.29
  4929.2  709.56  4959.5  708.27  4970.1  708.68  4989.9  708.55  4997.4  707.91
  5014.1   707.8  5020.2  706.13  5020.4  705.63  5023.9  705.63  5024.2  706.13
  5031.1  708.51  5144.2  710.93  5149.8  709.78  5155.4  710.23  5166.4     710
  5172.5  708.95  5188.6  708.83  5210.8  710.05  5255.2  710.94    5497  711.55
#Mann= 3 ,-1 , 0
  4527.7     .05       0  5020.2    .033       0  5024.2     .05       0
Bank Sta=5020.2,5024.2
XS Rating Curve= 0 ,0
Exp/Cntr=0.3,0.1

Type RM Length L Ch R = 1 ,5582    ,408,408,408
BEGIN DESCRIPTION:
Trail Creek Tr 5 11.0
END DESCRIPTION:
XS GIS Cut Line= 3
      2326885.88      7076712.63        2326779.        7076310.
      2326652.36        7076039.
#Sta/Elev= 30
  4583.4  709.36  4631.2  709.29  4706.4  707.95  4834.4   706.9  4861.9  705.99
  4867.1  706.48  4896.5  705.47  4922.8  705.15  4977.3  703.53  4982.5  702.79
  4987.6  700.75  4987.9  700.25  4991.4  700.25  4991.6  700.75  5002.7  700.93
  5008.6  702.52  5014.2  703.34    5037   703.9  5044.1  703.47  5059.9  704.32
  5077.2  704.29  5088.3  704.95  5105.5  704.78  5109.8   705.5  5143.5  707.13
  5151.2  708.09  5165.5  707.55  5196.9  707.42  5248.2  708.42  5299.1  708.74
#Mann= 5 ,-1 , 0
  4583.4     .05       0  4922.8     .12       0  4987.6     .07       0
  4991.6     .12       0  5109.8     .05       0
Bank Sta=4987.6,4991.6
XS Rating Curve= 0 ,0
Exp/Cntr=0.3,0.1

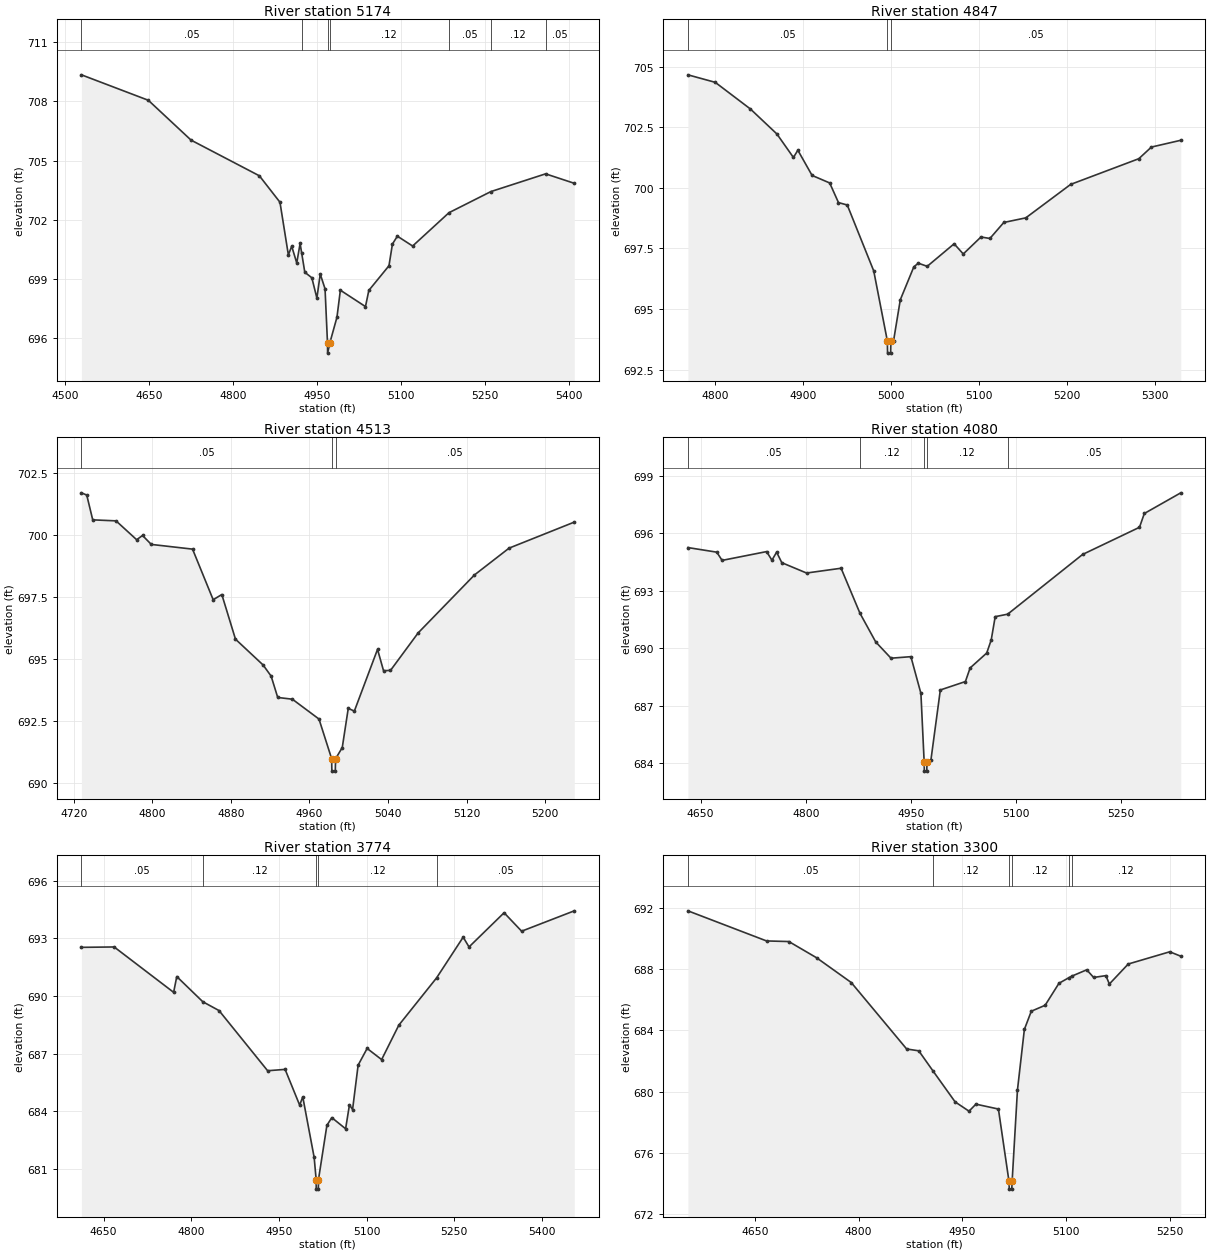
Type RM Length L Ch R = 1 ,5174    ,327,327,327
BEGIN DESCRIPTION:
Trail Creek Tr 5 10.0
END DESCRIPTION:
XS GIS Cut Line= 4
      2326981.68      7076742.59      2327044.28      7076413.05
      2327185.27      7076203.66      2327179.29      7075910.29
#Sta/Elev= 30
  4528.6  709.35  4648.2  708.06  4724.6  706.04  4846.8  704.23  4883.6  702.89
  4898.6  700.22  4904.6  700.66  4913.6  699.81  4919.6   700.8  4922.5   700.3
    4928  699.34  4940.6  699.06  4949.6  698.03  4955.6  699.25  4964.2   698.5
  4968.6  695.74  4968.8  695.24  4972.6  695.74  4985.5  697.06  4991.6  698.43
  5036.5   697.6  5042.5  698.42  5078.5  699.67  5084.7  700.77  5093.5  701.17
  5120.8  700.67  5185.8  702.36  5260.7  703.43  5358.6  704.33  5409.9  703.85
#Mann= 7 ,-1 , 0
  4528.6     .05       0  4922.5     .12       0  4968.6     .07       0
  4972.6     .12       0  5185.8     .05       0  5260.7     .12       0
  5358.6     .05       0
Bank Sta=4968.6,4972.6
XS Rating Curve= 0 ,0
Exp/Cntr=0.3,0.1

Type RM Length L Ch R = 1 ,4847    ,334,334,334
BEGIN DESCRIPTION:
Trail Creek Tr 5 9.0
END DESCRIPTION:
XS GIS Cut Line= 3
      2327439.75      7076491.04        2327429.        7076260.
       2327364.9      7075937.19
#Sta/Elev= 30
  4768.8  704.66  4799.9  704.35  4839.9  703.25    4870  702.22  4888.8  701.25
  4893.8  701.55    4910  700.51    4930   700.2    4940  699.39    4950  699.29
  4980.1  696.57  4995.6  693.68  4995.8  693.18  4999.3  693.18  4999.6  693.68
  5002.6  693.68  5010.3  695.38  5025.7  696.74  5030.8  696.89  5040.9  696.76
  5071.5  697.69  5081.9  697.27    5102  697.97  5112.2  697.91    5128  698.57
    5153  698.76    5204  700.14  5281.5   701.2  5295.8  701.68  5329.2  701.96
#Mann= 3 ,-1 , 0
  4768.8     .05       0  4995.6    .033       0  4999.6     .05       0
Bank Sta=4995.6,4999.6
XS Rating Curve= 0 ,0
Exp/Cntr=0.3,0.1

Type RM Length L Ch R = 1 ,4513    ,433,433,433
BEGIN DESCRIPTION:
Trail Creek Tr 5 8.0
END DESCRIPTION:
XS GIS Cut Line= 3
      2327816.99      7076299.48      2327643.34      7076044.99
      2327520.58      7075895.28
#Sta/Elev= 30
  4727.9  701.69  4733.3   701.6  4739.4   700.6  4763.1  700.56  4784.1   699.8
  4790.1  699.97    4799  699.61    4841  699.42    4862  697.38  4870.8  697.59
  4884.7  695.79  4912.8  694.75    4921   694.3  4927.7  693.44  4942.6  693.37
  4969.7  692.57  4982.6  690.97  4982.8  690.47  4986.3  690.47  4986.6  690.97
  4993.4  691.42  4999.5     693  5005.7  692.89  5029.3  695.38  5035.4  694.52
  5042.5  694.53  5070.6  696.04    5128  698.38  5163.2  699.46  5229.6  700.51
#Mann= 3 ,-1 , 0
  4727.9     .05       0  4982.6    .033       0  4986.6     .05       0
Bank Sta=4982.6,4986.6
XS Rating Curve= 0 ,0
Exp/Cntr=0.3,0.1

Type RM Length L Ch R = 1 ,4080    ,306,306,306
BEGIN DESCRIPTION:
Trail Creek Tr 5 7.0
END DESCRIPTION:
XS GIS Cut Line= 3
      2328257.06      7076200.64      2327975.66      7075880.32
      2327733.57      7075745.83
#Sta/Elev= 30
  4631.9  695.26  4673.1  695.02  4680.7  694.59  4744.2  695.05  4751.8   694.6
  4758.5  695.02  4765.9  694.47  4801.2  693.93  4850.5  694.18  4877.4  691.83
  4899.9  690.33  4921.7  689.48  4950.1  689.56  4964.4  687.64    4969  684.08
  4969.3  683.58  4972.8  683.58    4973  684.08  4978.6  684.14  4992.1  687.82
  5027.9  688.26  5034.6  688.97  5058.3  689.75  5064.7  690.43  5070.4  691.65
  5088.2  691.78  5195.1   694.9  5276.3  696.32  5283.2  697.04  5335.2  698.12
#Mann= 5 ,-1 , 0
  4631.9     .05       0  4877.4     .12       0    4969     .07       0
    4973     .12       0  5088.2     .05       0
Bank Sta=4969,4973
XS Rating Curve= 0 ,0
Exp/Cntr=0.3,0.1

Type RM Length L Ch R = 1 ,3774    ,474,474,474
BEGIN DESCRIPTION:
Trail Creek Tr 5 6.0
END DESCRIPTION:
XS GIS Cut Line= 4
      2328373.86      7076119.86       2328251.1      7075817.45
      2328183.15      7075637.47      2327858.94       7075646.8
#Sta/Elev= 30
  4612.1  692.53  4668.1  692.55  4769.8  690.19  4775.2  691.01  4819.7   689.7
  4847.5  689.24  4930.6  686.11  4960.5  686.18  4985.4  684.32  4990.7  684.75
  5010.2   681.6  5013.6  680.45  5013.8  679.95  5017.3  679.95  5017.6  680.45
    5032  683.27  5040.4  683.67    5064  683.09  5070.6  684.34  5075.9  684.09
  5085.4   686.4  5100.8  687.27  5125.6  686.69    5155  688.48  5219.6  690.94
  5265.1  693.06  5275.1  692.55  5335.1  694.33  5365.1  693.37  5455.2  694.43
#Mann= 5 ,-1 , 0
  4612.1     .05       0  4819.7     .12       0  5013.6     .07       0
  5017.6     .12       0  5219.6     .05       0
Bank Sta=5013.6,5017.6
XS Rating Curve= 0 ,0
Exp/Cntr=0.3,0.1

Type RM Length L Ch R = 1 ,3300    ,516,516,516
BEGIN DESCRIPTION:
Trail Creek Tr 5 5.0
END DESCRIPTION:
XS GIS Cut Line= 3
      2328649.29      7076155.73        2328629.        7075710.
      2328637.28      7075444.12
#Sta/Elev= 30
  4553.4  691.83    4667  689.86  4699.3  689.82  4739.3  688.76  4789.4  687.14
  4869.5  682.79    4887  682.67  4907.3  681.37  4939.5  679.33  4959.6  678.72
  4969.6  679.18  5002.1  678.86  5017.4  674.12  5017.8  673.62  5021.4  673.62
  5021.9  674.12  5029.6   680.1  5039.6  684.07  5049.6  685.26  5069.6  685.65
  5089.6  687.09  5103.4  687.44  5107.8  687.55  5129.7  687.97  5139.7  687.47
  5157.4  687.59  5162.4  687.04  5189.7  688.35  5249.7  689.15  5265.6  688.86
#Mann= 6 ,-1 , 0
  4553.4     .05       0  4907.3     .12       0  5017.4     .07       0
  5021.9     .12       0  5103.4     .05       0  5107.8     .12       0
Bank Sta=5017.4,5021.9
XS Rating Curve= 0 ,0
Exp/Cntr=0.3,0.1

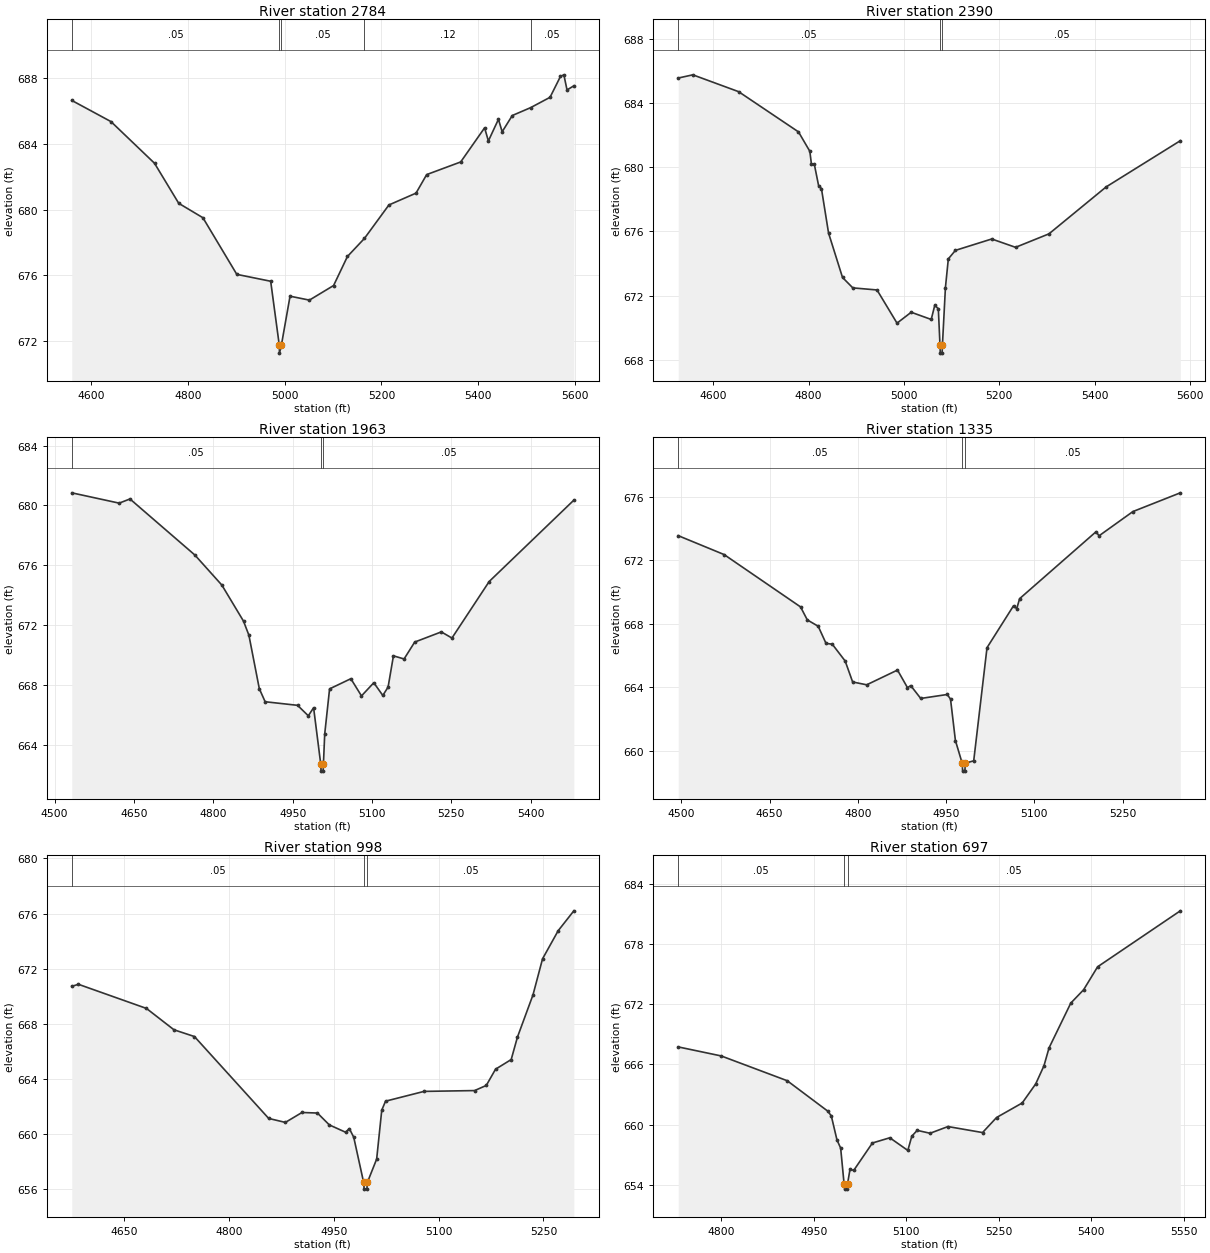
Type RM Length L Ch R = 1 ,2784    ,394,394,394
BEGIN DESCRIPTION:
Trail Creek Tr 5 4.0
END DESCRIPTION:
XS GIS Cut Line= 3
      2329104.36      7076050.94      2329095.38       7075500.1
      2328781.01      7075128.84
#Sta/Elev= 30
  4560.1  686.66  4641.1  685.37  4731.1  682.83  4781.1  680.39  4831.1  679.51
  4901.1  676.06  4971.1  675.64  4988.8  671.76  4989.3  671.26  4993.3  671.76
  5011.1  674.73  5051.1  674.49  5101.1  675.38  5129.7  677.15  5164.8  678.25
  5215.4  680.29  5271.4  681.01  5293.4  682.14  5363.7  682.91  5413.1  684.99
  5420.9  684.19  5441.7  685.51  5449.4  684.75  5470.3  685.74  5508.2  686.22
  5548.3  686.85  5569.8  688.12  5576.9  688.22  5583.4   687.3  5597.5  687.55
#Mann= 5 ,-1 , 0
  4560.1     .05       0  4988.8    .033       0  4993.3     .05       0
  5164.8     .12       0  5508.2     .05       0
Bank Sta=4988.8,4993.3
XS Rating Curve= 0 ,0
Exp/Cntr=0.3,0.1

Type RM Length L Ch R = 1 ,2390    ,427,427,427
BEGIN DESCRIPTION:
Trail Creek Tr 5 3.0
END DESCRIPTION:
XS GIS Cut Line= 4
      2329200.16      7076110.87       2329230.1       7075838.4
      2329409.74      7075574.94      2329427.68      7075114.47
#Sta/Elev= 30
  4526.3  685.57  4556.9  685.77    4653  684.72  4778.7  682.21  4802.5     681
  4805.9  680.19    4812  680.18  4820.9  678.86  4826.9  678.67  4841.8   675.9
  4871.1  673.13  4892.7  672.48  4943.5  672.35  4985.5  670.28  5015.3  670.96
  5057.3  670.51  5064.7  671.39  5072.2  671.18  5075.7  668.91  5076.3  668.41
  5080.1  668.41  5080.8  668.91  5087.1   672.5  5093.2  674.29  5108.1  674.82
  5184.3  675.53  5234.3  675.01  5304.4  675.85  5424.5  678.78  5580.1  681.66
#Mann= 3 ,-1 , 0
  4526.3     .05       0  5075.7     .04       0  5080.8     .05       0
Bank Sta=5075.7,5080.8
XS Rating Curve= 0 ,0
Exp/Cntr=0.3,0.1

Type RM Length L Ch R = 1 ,1963    ,628,628,628
BEGIN DESCRIPTION:
Trail Creek Tr 5 2.0
END DESCRIPTION:
XS GIS Cut Line= 3
      2329610.34       7076167.7      2329700.15      7075739.61
      2329754.01      7075230.86
#Sta/Elev= 30
  4532.5  680.84  4622.1  680.15  4642.5  680.43  4765.2  676.68  4816.2  674.67
  4857.1  672.26  4867.3  671.32    4887  667.74    4898  666.87  4959.3  666.63
  4979.6  665.93  4989.6  666.47    5003  662.73  5003.7  662.23  5007.5  662.23
  5008.2  662.73  5010.6  664.71  5019.8  667.73    5060  668.41  5080.1  667.26
  5103.4  668.14  5120.4  667.29  5130.4  667.85  5140.5  669.94  5160.6  669.73
  5180.7  670.86    5231  671.54  5251.1  671.13  5321.5  674.91  5481.5  680.35
#Mann= 3 ,-1 , 0
  4532.5     .05       0    5003     .04       0  5008.2     .05       0
Bank Sta=5003,5008.2
XS Rating Curve= 0 ,0
Exp/Cntr=0.3,0.1

Type RM Length L Ch R = 1 ,1335    ,337,337,337
BEGIN DESCRIPTION:
Trail Creek Tr 5 1.5
END DESCRIPTION:
XS GIS Cut Line= 4
      2329891.74      7076071.96        2330027.      7075746.07
      2330128.27      7075539.02      2330140.25      7075269.62
#Sta/Elev= 30
  4494.9  673.56  4572.8  672.37  4702.7  669.07  4714.2  668.25  4732.7  667.85
    4746  666.77  4756.6  666.72  4778.5  665.66  4791.2  664.34  4815.1  664.16
  4867.4  665.09  4884.4  663.98  4889.9  664.11  4906.9   663.3  4951.9  663.55
  4957.5  663.26  4965.8  660.65  4977.3  659.22  4978.1  658.72  4981.9  658.72
  4982.7  659.22  4996.9  659.37  5019.5   666.5  5064.5  669.14    5070  668.96
  5074.9  669.59  5204.8  673.81  5209.8  673.55  5267.4  675.08  5347.9  676.26
#Mann= 3 ,-1 , 0
  4494.9     .05       0  4977.3     .04       0  4982.7     .05       0
Bank Sta=4977.3,4982.7
XS Rating Curve= 0 ,0
Exp/Cntr=0.3,0.1

Type RM Length L Ch R = 1 ,998     ,301,301,301
BEGIN DESCRIPTION:
Trail Creek Tr 5 1.0
END DESCRIPTION:
XS GIS Cut Line= 4
      2330077.37      7076158.78      2330212.63      7075832.89
      2330313.89      7075787.51      2330429.01      7075559.99
#Sta/Elev= 30
  4574.8  670.72  4584.3  670.87  4681.7  669.12  4721.1  667.57  4750.4  667.08
  4856.7  661.14  4880.6  660.85  4904.4  661.57  4926.5  661.53  4943.5  660.67
  4966.7  660.14  4972.2   660.4  4978.5  659.77  4992.6  656.51  4993.4  656.01
  4997.3  656.01  4998.1  656.51  5011.3  658.19  5018.6  661.74    5024  662.39
  5079.1   663.1  5151.5  663.16  5168.2  663.53  5181.5  664.71  5203.9  665.41
  5212.8  667.03  5235.1   670.1  5248.8  672.72  5271.2  674.76  5293.6   676.2
#Mann= 3 ,-1 , 0
  4574.8     .05       0  4992.6     .04       0  4998.1     .05       0
Bank Sta=4992.6,4998.1
XS Rating Curve= 0 ,0
Exp/Cntr=0.3,0.1

Type RM Length L Ch R = 1 ,697     ,391,391,391
BEGIN DESCRIPTION:
Trail Creek Tr 5 0.5
END DESCRIPTION:
XS GIS Cut Line= 3
      2330292.92       7076248.6       2330508.5      7075913.26
      2330762.58      7075584.45
#Sta/Elev= 30
  4730.2  667.74  4799.9  666.84  4906.9  664.37  4972.4  661.35  4978.4  660.87
  4987.6  658.47  4993.6  657.65  4999.2  654.06    5000  653.56  5003.9  653.56
  5004.7  654.06  5008.8  655.55  5014.7  655.42  5045.1  658.16  5073.3  658.68
  5102.5  657.42    5109  658.84  5117.7  659.42  5138.6  659.13  5167.6   659.8
  5223.7   659.2  5246.4   660.7    5288  662.15  5309.9  664.05  5323.3  665.86
  5331.5  667.64  5366.8  672.11  5387.6  673.44  5410.3  675.73  5544.4  681.31
#Mann= 3 ,-1 , 0
  4730.2     .05       0  4999.2     .04       0  5004.7     .05       0
Bank Sta=4999.2,5004.7
XS Rating Curve= 0 ,0
Exp/Cntr=0.3,0.1