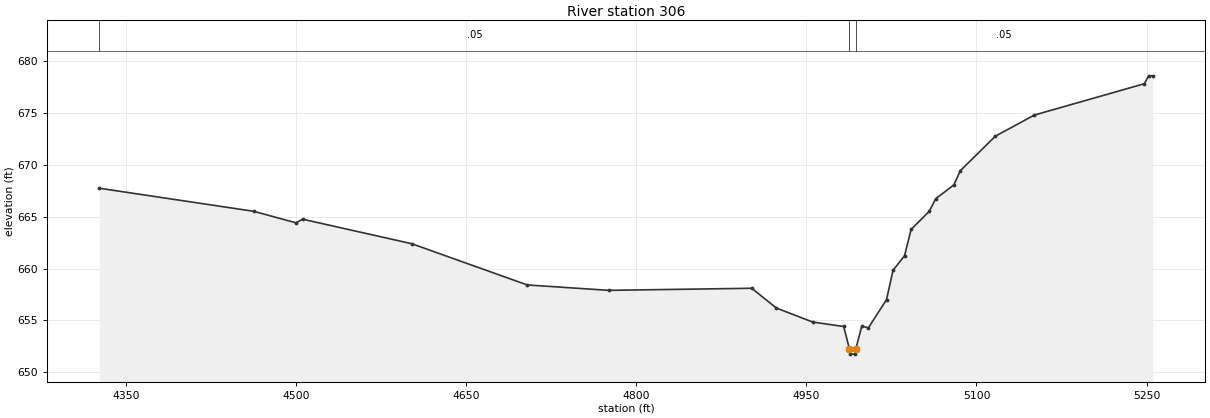
HEC-RAS study Trail Creek Tr 5.prj: Trail Creek Tr 5 Base Level Engineering

--- Trail Creek Tr 5.g01 (geometry) --- (continued)

Type RM Length L Ch R = 1 ,306     ,0,0,0
BEGIN DESCRIPTION:
Trail Creek Tr 5 0.3
END DESCRIPTION:
XS GIS Cut Line= 3
      2330274.97       7076332.4      2330664.18      7076107.86
      2330897.68      7075688.75
#Sta/Elev= 30
  4326.4  667.73  4462.5  665.51  4499.9   664.4  4505.6  664.75  4601.9  662.39
  4703.8  658.42  4775.6   657.9  4901.8   658.1  4923.5   656.2  4955.5  654.85
  4982.9  654.42    4988  652.26  4988.8  651.76  4992.7  651.76  4993.6  652.26
  4998.9  654.46  5004.7  654.29  5020.7  657.01  5026.4  659.82  5036.6  661.24
  5042.4  663.77  5058.4  665.51  5064.1  666.72  5080.1  668.05  5085.8  669.42
  5116.7  672.74    5151  674.77  5248.1  677.79  5251.9  678.55  5255.5  678.55
#Mann= 3 ,-1 , 0
  4326.4     .05       0    4988     .04       0  4993.6     .05       0
Bank Sta=4988,4993.6
XS Rating Curve= 0 ,0
Exp/Cntr=0.3,0.1

Chan Stop Cuts=-1
Use User Specified Reach Order=0
Composite Channel Slope=5