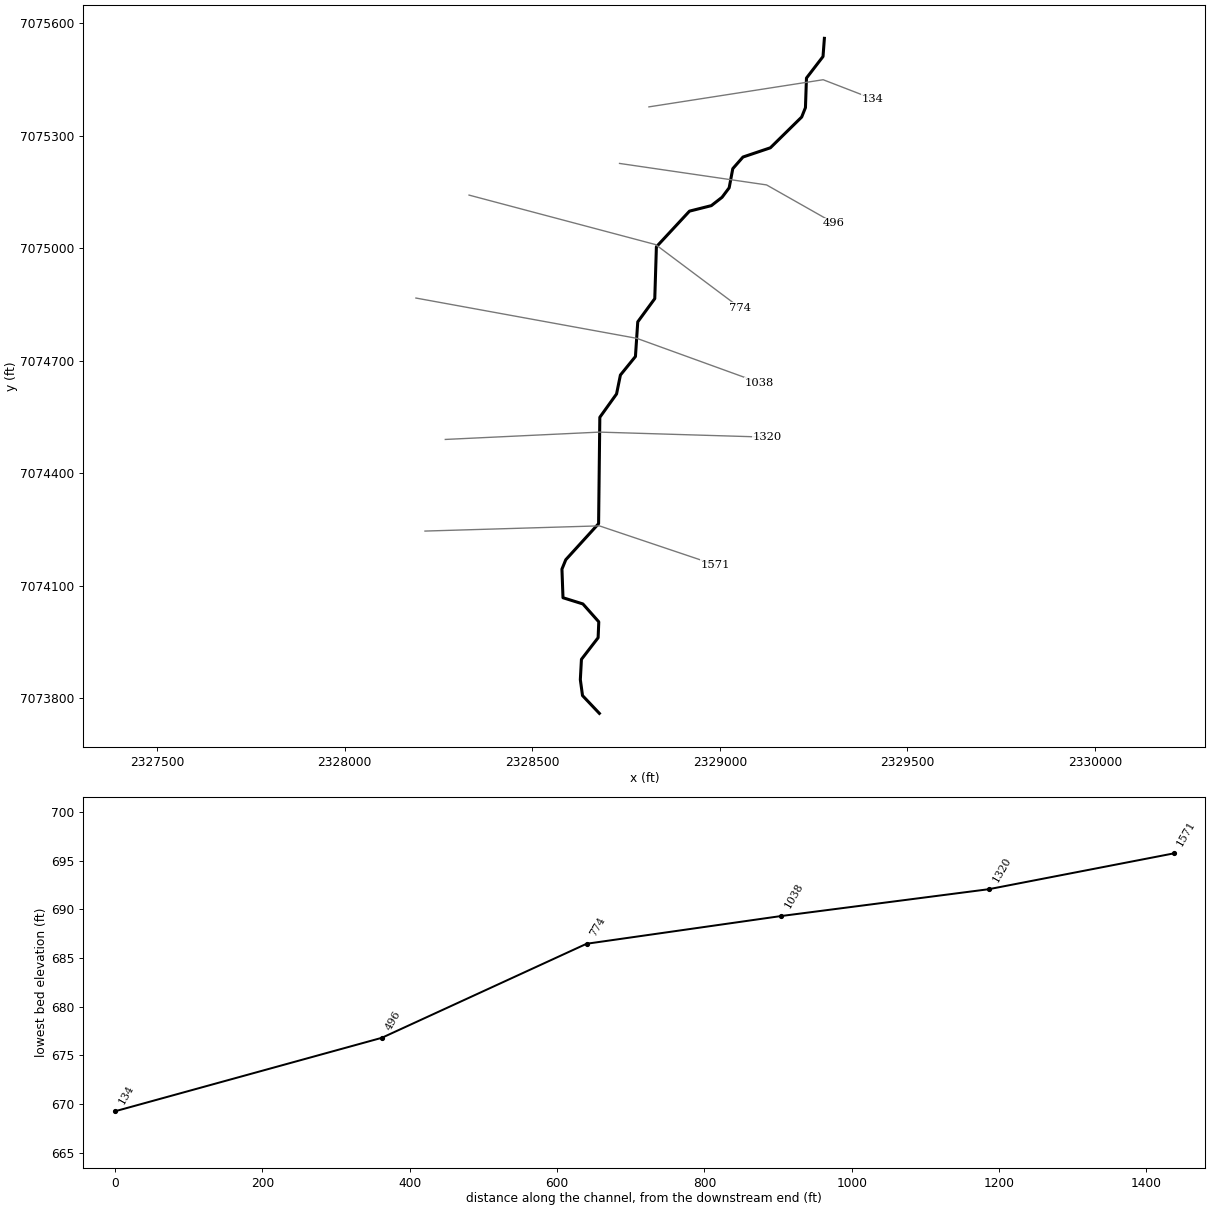
--- Trail Creek Tr 5_1.prj (project) ---

Proj Title=Trail Creek Tr 5_1 Base Level Engineering
Current Plan=p01
Default Exp/Contr=0.3,0.1
English Units
Geom File=g01
Flow File=f01
Plan File=p01
BEGIN DESCRIPTION:
Trail Creek Tr 5_1
END DESCRIPTION:

--- Trail Creek Tr 5_1.p01 (plan) ---

Plan Title=Multiple Run
Short Identifier=Multiple
Geom File=g01
Flow File=f01
Subcritical Flow
K Sum by GR= 0
Std Step Tol= 0.01
Critical Tol= 0.01
Num of Std Step Trials= 20
Max Error Tol= 0.3
Flow Tol Ratio= 0.001
Split Flow NTrial= 30
Split Flow Tol= 0.02
Split Flow Ratio= 0.02
Log Output Level= 0
Friction Slope Method= 1
Unsteady Friction Slope Method= 2
Unsteady Bridges Friction Slope Method= 1
Parabolic Critical Depth
Global Vel Dist=  1 , 1 , 1
Global Log Level= 0
CheckData=True
Encroach Param= -1, 0, 0, 0
BEGIN DESCRIPTION:
Multiple Run
END DESCRIPTION:

--- Trail Creek Tr 5_1.f01 (steady flow) ---

Flow Title=Multiple
Number of Profiles=7
Profile Names=10-year,25-year,50-year,1pct_min,100-year,1pct_plu,500-year
River Rch & RM= Trail Creek Tr 5,Reach-1,1571
     254     330     390     230     458     915     632
Boundary for River Rch & Prof#=Trail Creek Tr 5,Reach-1,1
Up Type=0
Dn Type=3
Dn Slope=0.005
Boundary for River Rch & Prof#=Trail Creek Tr 5,Reach-1,2
Up Type=0
Dn Type=3
Dn Slope=0.005
Boundary for River Rch & Prof#=Trail Creek Tr 5,Reach-1,3
Up Type=0
Dn Type=3
Dn Slope=0.005
Boundary for River Rch & Prof#=Trail Creek Tr 5,Reach-1,4
Up Type=0
Dn Type=3
Dn Slope=0.005
Boundary for River Rch & Prof#=Trail Creek Tr 5,Reach-1,5
Up Type=0
Dn Type=3
Dn Slope=0.005
Boundary for River Rch & Prof#=Trail Creek Tr 5,Reach-1,6
Up Type=0
Dn Type=3
Dn Slope=0.005
Boundary for River Rch & Prof#=Trail Creek Tr 5,Reach-1,7
Up Type=0
Dn Type=3
Dn Slope=0.005

--- Trail Creek Tr 5_1.g01 (geometry) ---

Geom Title=Existing Conditions

River Reach=Trail Creek Tr 5,Reach-1
Reach XY= 30
      2328679.00      7073760.00      2328634.05      7073807.45
      2328628.22      7073849.98      2328631.19      7073904.05
      2328675.67      7073961.77      2328677.43      7074004.14
      2328635.07      7074051.82      2328582.00      7074068.35
      2328579.19      7074144.65      2328589.44      7074169.74
      2328676.93      7074265.86      2328680.20      7074549.50
      2328724.81      7074611.74      2328735.11      7074662.18
      2328775.17      7074711.58      2328781.36      7074804.02
      2328826.73      7074865.94      2328831.06      7075004.15
      2328919.31      7075099.22      2328977.57      7075113.89
      2329006.14      7075136.17      2329025.10      7075161.46
      2329034.76      7075212.51      2329061.95      7075243.50
      2329135.05      7075268.16      2329218.49      7075350.19
      2329228.49      7075375.21      2329231.23      7075454.08
      2329275.36      7075511.51      2329279.00      7075560.00

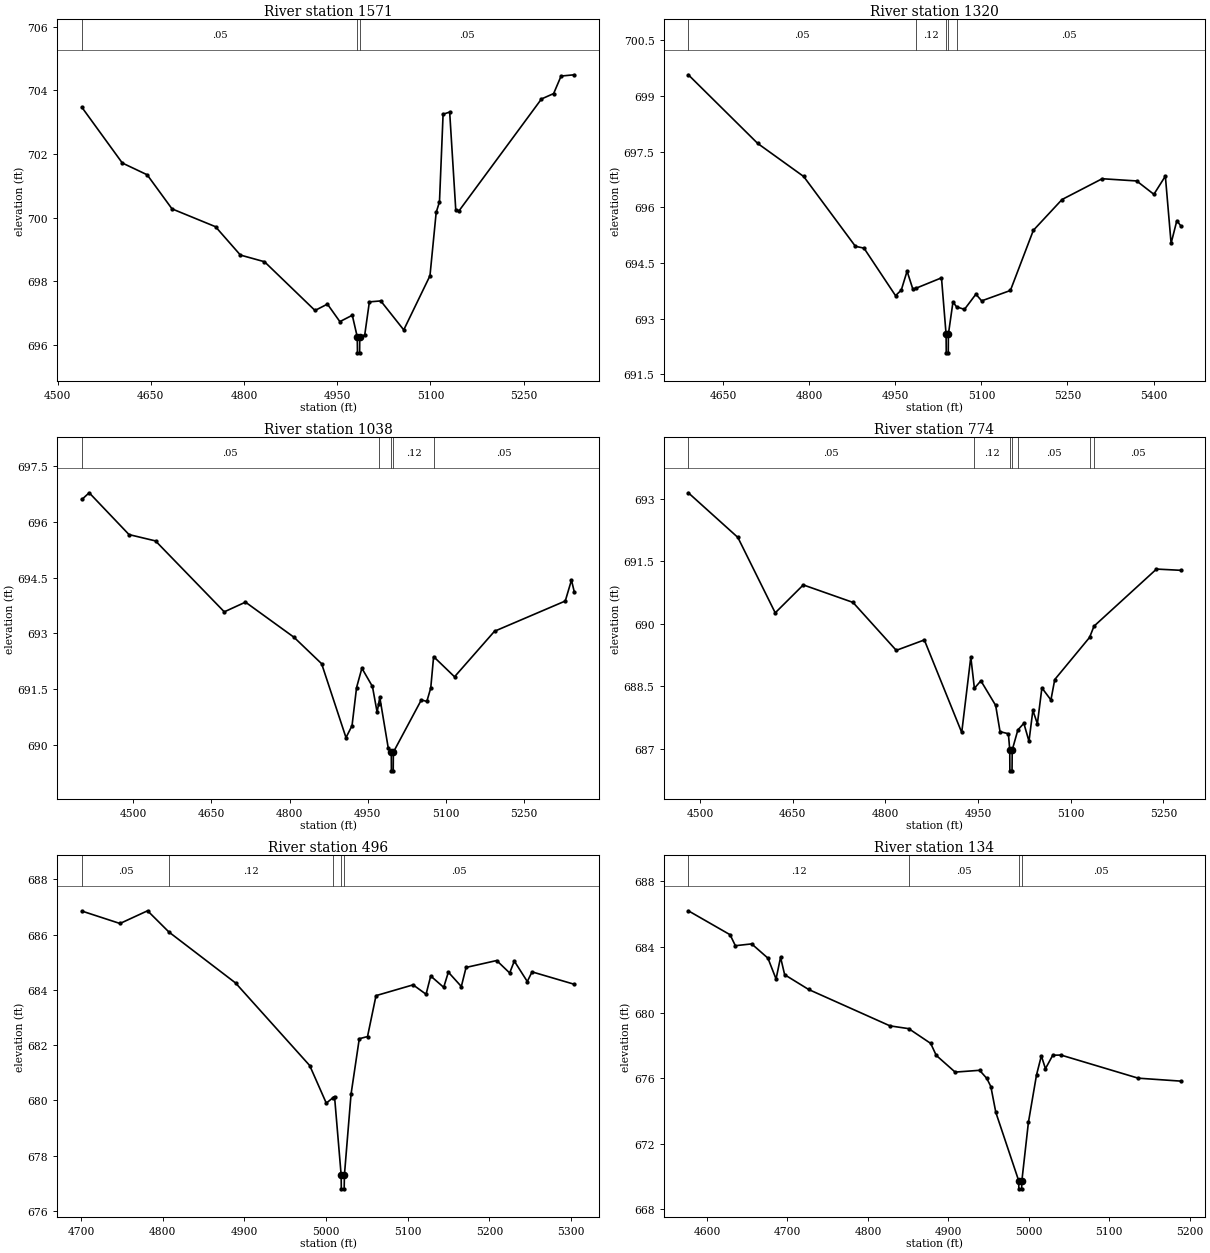
Type RM Length L Ch R = 1,1571,251,251,251
BEGIN DESCRIPTION:
Trail Creek Tr 5_1 4.0
END DESCRIPTION:
XS GIS Cut Line= 3
      2328213.97      7074246.12      2328679.00      7074260.00
      2328989.17      7074155.62
#Sta/Elev= 30
  4539.1  703.47  4604.2  701.72  4644.2  701.35  4684.2  700.28  4754.2  699.72
  4794.2  698.83  4833.0  698.62  4914.3  697.09  4934.3  697.29  4954.3  696.74
  4974.3  696.94  4982.3  696.26  4982.6  695.76  4986.1  695.76  4986.3  696.26
  4994.3  696.32  5001.8  697.36  5020.1  697.39  5057.1  696.48  5099.3  698.18
  5109.3  700.17  5114.6  700.50  5120.4  703.25  5131.0  703.32  5140.8  700.25
  5146.1  700.22  5278.7  703.73  5298.3  703.90  5310.3  704.45  5331.6  704.49
#Mann=3,-1,0
  4539.1    0.05       0  4982.3    0.04       0  4986.3    0.05       0
Bank Sta=4982.3,4986.3
Exp/Cntr=0.3,0.1

Type RM Length L Ch R = 1,1320,282,282,282
BEGIN DESCRIPTION:
Trail Creek Tr 5_1 3.0
END DESCRIPTION:
XS GIS Cut Line= 3
      2328268.17      7074490.44      2328679.00      7074510.00
      2329125.91      7074496.54
#Sta/Elev= 30
  4589.1  699.57  4710.1  697.72  4790.2  696.83  4880.3  694.95  4895.3  694.90
  4950.3  693.62  4960.3  693.77  4970.4  694.28  4980.4  693.80  4985.9  693.82
  5030.4  694.10  5038.4  692.58  5038.7  692.08  5042.2  692.08  5042.4  692.58
  5050.4  693.45  5056.6  693.32  5070.4  693.25  5090.4  693.66  5100.4  693.48
  5150.5  693.76  5190.5  695.38  5240.5  696.21  5310.5  696.77  5370.6  696.71
  5400.6  696.35  5420.6  696.84  5430.6  695.03  5440.6  695.64  5447.5  695.50
#Mann=5,-1,0
  4589.1    0.05       0  4985.9    0.12       0  5038.4    0.07       0
  5042.4    0.12       0  5056.6    0.05       0
Bank Sta=5038.4,5042.4
Exp/Cntr=0.3,0.1

Type RM Length L Ch R = 1,1038,264,264,264
BEGIN DESCRIPTION:
Trail Creek Tr 5_1 2.0
END DESCRIPTION:
XS GIS Cut Line= 3
      2328189.83      7074867.48      2328779.00      7074760.00
      2329105.35      7074641.77
#Sta/Elev= 30
  4401.1  696.59  4415.2  696.77  4491.7  695.65  4542.6  695.48  4674.7  693.58
  4715.4  693.84  4808.5  692.90  4861.7  692.19  4908.5  690.21  4920.1  690.53
  4928.8  691.55  4939.0  692.07  4959.3  691.58  4968.3  690.89  4971.1  691.11
  4973.4  691.29  4989.8  689.92  4995.5  689.82  4995.7  689.32  4999.2  689.32
  4999.5  689.82  5053.2  691.22  5063.8  691.18  5071.3  691.54  5076.8  692.38
  5117.0  691.84  5193.8  693.06  5329.7  693.87  5341.6  694.43  5347.1  694.11
#Mann=5,-1,0
  4401.1    0.05       0  4971.1    0.12       0  4995.5    0.07       0
  4999.5    0.12       0  5076.8    0.05       0
Bank Sta=4995.5,4999.5
Exp/Cntr=0.3,0.1

Type RM Length L Ch R = 1,774,278,278,278
BEGIN DESCRIPTION:
Trail Creek Tr 5_1 1.0
END DESCRIPTION:
XS GIS Cut Line= 3
      2328331.53      7075141.98      2328829.00      7075010.00
      2329054.72      7074840.92
#Sta/Elev= 30
  4481.3  693.14  4561.4  692.07  4621.9  690.26  4667.3  690.93  4747.7  690.51
  4817.7  689.36  4863.1  689.61  4923.6  687.39  4938.3  689.20  4944.1  688.45
  4954.6  688.63  4978.5  688.04  4985.6  687.41  4999.1  687.36  5001.3  686.97
  5001.5  686.47  5005.0  686.47  5005.3  686.97  5014.4  687.45  5024.1  687.61
  5032.4  687.18  5038.7  687.92  5046.0  687.60  5053.3  688.46  5067.9  688.17
  5074.1  688.66  5130.4  689.67  5137.6  689.94  5238.7  691.31  5278.0  691.28
#Mann=7,-1,0
  4481.3    0.05       0  4944.1    0.12       0  5001.3    0.07       0
  5005.3    0.12       0  5014.4    0.05       0  5130.4    0.12       0
  5137.6    0.05       0
Bank Sta=5001.3,5005.3
Exp/Cntr=0.3,0.1

Type RM Length L Ch R = 1,496,362,362,362
BEGIN DESCRIPTION:
Trail Creek Tr 5_1 0.4
END DESCRIPTION:
XS GIS Cut Line= 3
      2328732.79      7075226.43      2329124.86      7075169.12
      2329304.92      7075067.09
#Sta/Elev= 30
  4700.8  686.85  4747.5  686.40  4781.3  686.86  4807.5  686.09  4889.0  684.25
  4979.9  681.26  5000.2  679.90  5008.5  680.10  5010.3  680.14  5018.4  677.30
  5018.6  676.80  5022.1  676.80  5022.4  677.30  5030.5  680.22  5040.6  682.23
  5050.7  682.31  5061.1  683.79  5106.5  684.18  5122.4  683.84  5128.1  684.50
  5144.0  684.09  5149.7  684.64  5165.6  684.12  5171.4  684.81  5208.9  685.06
  5224.8  684.61  5230.5  685.04  5246.4  684.30  5252.2  684.65  5304.0  684.20
#Mann=5,-1,0
  4700.8    0.05       0  4807.5    0.12       0  5008.5    0.05       0
  5018.4    0.07       0  5022.4    0.05       0
Bank Sta=5018.4,5022.4
Exp/Cntr=0.3,0.1

Type RM Length L Ch R = 1,134,0,0,0
BEGIN DESCRIPTION:
Trail Creek Tr 5_1 0.2
END DESCRIPTION:
XS GIS Cut Line= 3
      2328811.16      7075377.25      2329275.68      7075449.64
      2329408.39      7075398.37
#Sta/Elev= 30
  4576.7  686.21  4628.6  684.75  4635.2  684.08  4655.5  684.19  4675.7  683.32
  4685.8  682.05  4691.4  683.37  4696.5  682.31  4726.3  681.41  4827.5  679.19
  4850.8  679.02  4878.1  678.12  4885.0  677.39  4908.5  676.37  4938.9  676.48
  4947.8  675.99  4952.9  675.49  4959.1  673.91  4987.5  669.75  4987.7  669.25
  4991.2  669.25  4991.5  669.75  4999.6  673.30  5009.7  676.20  5015.7  677.36
  5020.8  676.58  5029.9  677.40  5040.1  677.41  5136.1  676.00  5189.1  675.82
#Mann=4,-1,0
  4576.7    0.12       0  4850.8    0.05       0  4987.5    0.04       0
  4991.5    0.05       0
Bank Sta=4987.5,4991.5
Exp/Cntr=0.3,0.1

Chan Stop Cuts=-1