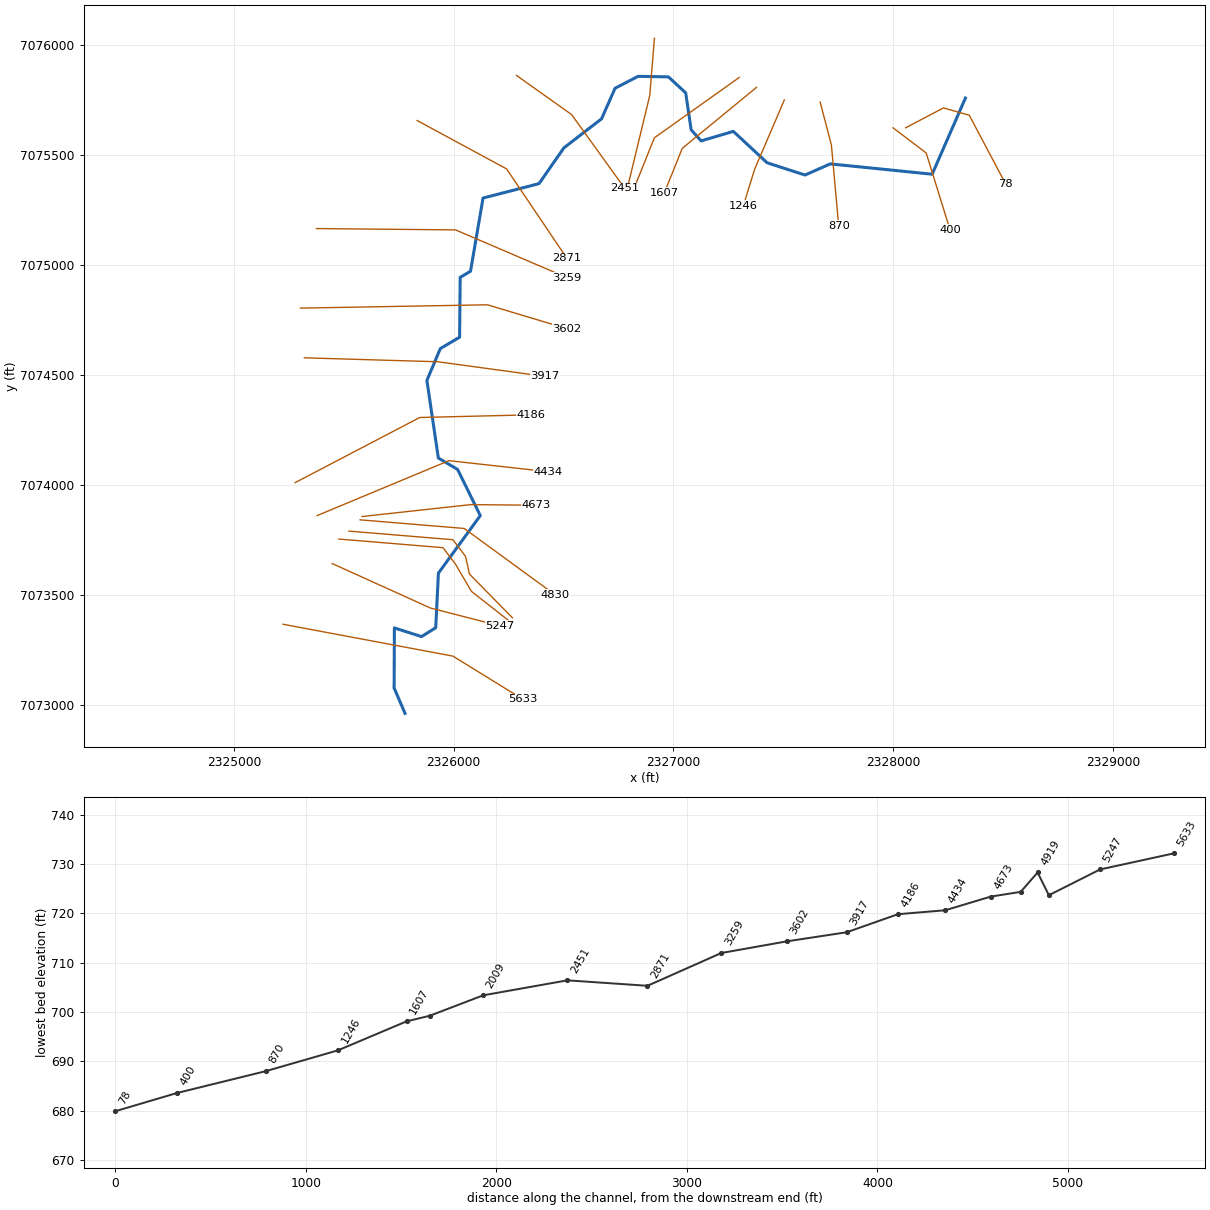
--- Trail Creek Tr 5_2.prj (project) ---

Proj Title=Trail Creek Tr 5_2 Base Level Engineering
Current Plan=p01
Default Exp/Contr=0.3,0.1
English Units
Geom File=g01
Flow File=f01
Plan File=p01
BEGIN DESCRIPTION:
Trail Creek Tr 5_2
END DESCRIPTION:

--- Trail Creek Tr 5_2.p01 (plan) ---

Plan Title=Multiple Run
Short Identifier=Multiple
Geom File=g01
Flow File=f01
Subcritical Flow
K Sum by GR= 0
Std Step Tol= 0.01
Critical Tol= 0.01
Num of Std Step Trials= 20
Max Error Tol= 0.3
Flow Tol Ratio= 0.001
Split Flow NTrial= 30
Split Flow Tol= 0.02
Split Flow Ratio= 0.02
Log Output Level= 0
Friction Slope Method= 1
Unsteady Friction Slope Method= 2
Unsteady Bridges Friction Slope Method= 1
Parabolic Critical Depth
Global Vel Dist=  1 , 1 , 1
Global Log Level= 0
CheckData=True
Encroach Param= -1, 0, 0, 0
BEGIN DESCRIPTION:
Multiple Run
END DESCRIPTION:

--- Trail Creek Tr 5_2.f01 (steady flow) ---

Flow Title=Multiple
Number of Profiles=7
Profile Names=10-year,25-year,50-year,1pct_min,100-year,1pct_plu,500-year
River Rch & RM= Trail Creek Tr 5,Reach-1,5633
     359     477     571     340     679    1354     961
River Rch & RM= Trail Creek Tr 5,Reach-1,2871
     432     581     701     421     840    1676    1207
Boundary for River Rch & Prof#=Trail Creek Tr 5,Reach-1,1
Up Type=0
Dn Type=3
Dn Slope=0.005
Boundary for River Rch & Prof#=Trail Creek Tr 5,Reach-1,2
Up Type=0
Dn Type=3
Dn Slope=0.005
Boundary for River Rch & Prof#=Trail Creek Tr 5,Reach-1,3
Up Type=0
Dn Type=3
Dn Slope=0.005
Boundary for River Rch & Prof#=Trail Creek Tr 5,Reach-1,4
Up Type=0
Dn Type=3
Dn Slope=0.005
Boundary for River Rch & Prof#=Trail Creek Tr 5,Reach-1,5
Up Type=0
Dn Type=3
Dn Slope=0.005
Boundary for River Rch & Prof#=Trail Creek Tr 5,Reach-1,6
Up Type=0
Dn Type=3
Dn Slope=0.005
Boundary for River Rch & Prof#=Trail Creek Tr 5,Reach-1,7
Up Type=0
Dn Type=3
Dn Slope=0.005

--- Trail Creek Tr 5_2.g01 (geometry) ---

Geom Title=Existing Conditions

River Reach=Trail Creek Tr 5,Reach-1
Reach XY= 30
      2325779.00      7072960.00      2325729.45      7073075.19
      2325730.62      7073348.84      2325854.12      7073309.48
      2325918.66      7073349.76      2325930.92      7073598.05
      2326121.50      7073860.00      2326018.31      7074069.98
      2325930.66      7074121.84      2325878.56      7074475.18
      2325939.69      7074619.98      2326027.36      7074671.83
      2326029.96      7074944.04      2326077.02      7074971.97
      2326134.02      7075304.99      2326388.77      7075370.52
      2326502.01      7075533.47      2326673.41      7075665.61
      2326734.58      7075804.42      2326839.48      7075858.82
      2326977.54      7075856.48      2327056.16      7075783.58
      2327080.99      7075615.63      2327126.42      7075564.97
      2327272.96      7075608.38      2327426.57      7075465.52
      2327599.18      7075409.72      2327713.82      7075460.42
      2328177.77      7075413.43      2328329.00      7075760.00

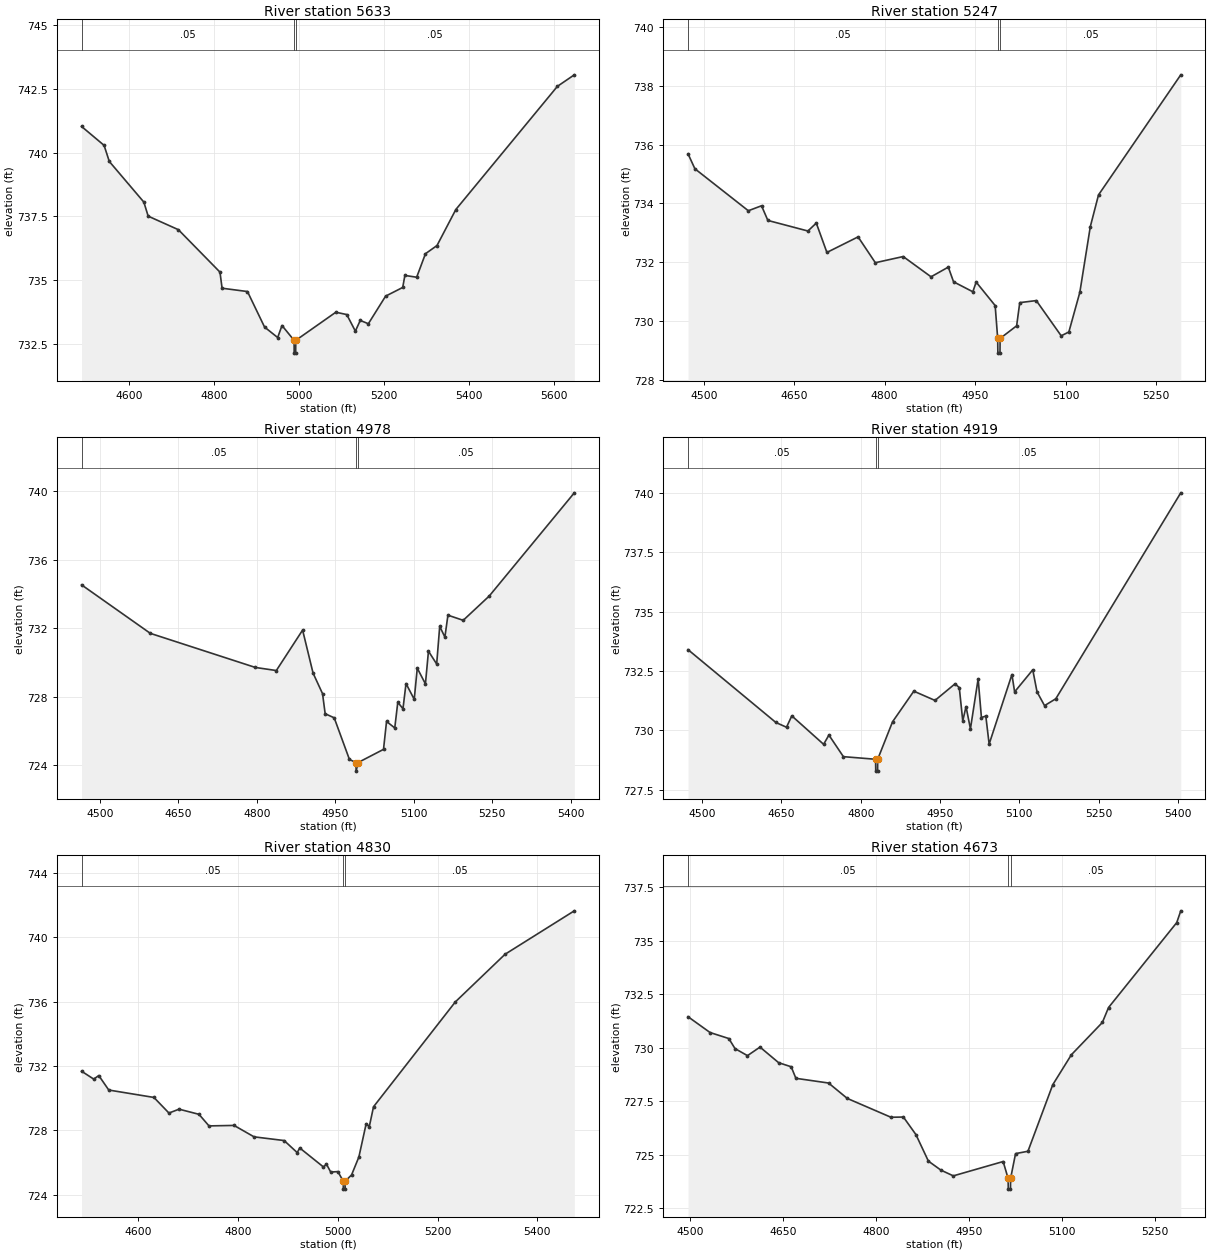
Type RM Length L Ch R = 1,5633,386,386,386
BEGIN DESCRIPTION:
Trail Creek Tr 5_2 14.0
END DESCRIPTION:
XS GIS Cut Line= 3
      2325224.71      7073365.35      2325996.91      7073220.56
      2326316.61      7073023.31
#Sta/Elev= 30
  4487.1  741.02  4540.2  740.28  4552.5  739.65  4633.9  738.06  4644.1  737.51
  4715.3  736.98  4813.3  735.32  4818.3  734.69  4878.1  734.56  4918.4  733.17
  4949.3  732.76  4959.5  733.23  4988.0  732.65  4988.2  732.15  4991.7  732.15
  4992.0  732.65  5086.3  733.75  5112.1  733.66  5132.4  733.01  5143.9  733.43
  5163.0  733.30  5203.7  734.38  5244.0  734.72  5249.1  735.19  5276.9  735.12
  5297.6  736.04  5324.8  736.36  5369.2  737.77  5608.6  742.59  5648.4  743.04
#Mann=3,-1,0
  4487.1    0.05       0  4988.0   0.033       0  4992.0    0.05       0
Bank Sta=4988,4992
Exp/Cntr=0.3,0.1

Type RM Length L Ch R = 1,5247,269,269,269
BEGIN DESCRIPTION:
Trail Creek Tr 5_2 13.0
END DESCRIPTION:
XS GIS Cut Line= 3
      2325447.91      7073641.65      2325894.35      7073439.55
      2326211.09      7073358.10
#Sta/Elev= 30
  4473.9  735.69  4485.3  735.18  4573.9  733.75  4595.8  733.92  4606.3  733.42
  4672.7  733.06  4686.6  733.33  4704.2  732.33  4755.9  732.86  4784.5  731.98
  4830.7  732.19  4876.9  731.50  4905.5  731.83  4914.2  731.33  4946.2  730.99
  4951.7  731.32  4983.2  730.52  4987.4  729.40  4987.7  728.90  4991.2  728.90
  4991.4  729.40  5018.8  729.83  5024.0  730.62  5051.4  730.69  5092.7  729.49
  5105.4  729.62  5123.6  730.97  5141.0  733.21  5154.6  734.29  5291.0  738.38
#Mann=3,-1,0
  4473.9    0.05       0  4987.4   0.033       0  4991.4    0.05       0
Bank Sta=4987.4,4991.4
Exp/Cntr=0.3,0.1

Type RM Length L Ch R = 1,4978,59,59,59
BEGIN DESCRIPTION:
Trail Creek Tr 5_2 12.4
END DESCRIPTION:
XS GIS Cut Line= 5
      2325478.08      7073753.25      2325951.66      7073714.04
      2326008.97      7073638.63      2326081.36      7073514.96
      2326261.15      7073374.13
#Sta/Elev= 30
  4465.1  734.54  4596.5  731.71  4797.2  729.72  4837.3  729.54  4887.5  731.90
  4907.5  729.39  4925.6  728.19  4930.6  727.02  4947.9  726.78  4977.0  724.35
  4989.5  724.17  4989.8  723.67  4993.5  724.17  5042.1  724.94  5047.9  726.57
  5063.6  726.19  5069.4  727.69  5079.3  727.31  5085.1  728.78  5100.8  727.86
  5106.6  729.68  5122.2  728.76  5128.0  730.67  5143.7  729.92  5149.5  732.12
  5159.4  731.49  5165.2  732.77  5194.4  732.47  5244.2  733.89  5406.7  739.91
#Mann=3,-1,0
  4465.1    0.05       0  4989.5   0.033       0  4993.5    0.05       0
Bank Sta=4989.5,4993.5
Exp/Cntr=0.3,0.1

Type RM Length L Ch R = 1,4919,89,89,89
BEGIN DESCRIPTION:
Trail Creek Tr 5_2 12.2
END DESCRIPTION:
XS GIS Cut Line= 5
      2325523.37      7073789.44      2325996.91      7073750.23
      2326054.22      7073674.82      2326072.25      7073594.04
      2326268.05      7073394.64
#Sta/Elev= 30
  4473.2  733.40  4639.4  730.33  4659.5  730.13  4669.5  730.61  4729.7  729.41
  4739.7  729.80  4767.1  728.89  4828.0  728.78  4828.3  728.28  4831.8  728.28
  4832.0  728.78  4860.1  730.36  4900.3  731.65  4940.4  731.26  4978.3  731.96
  4986.3  731.80  4992.9  730.40  4999.1  731.00  5007.4  730.06  5022.0  732.17
  5028.2  730.54  5036.5  730.60  5042.8  729.42  5085.9  732.35  5091.0  731.62
  5125.3  732.55  5133.4  731.62  5147.6  731.04  5168.9  731.33  5405.3  740.01
#Mann=3,-1,0
  4473.2    0.05       0  4828.0   0.033       0  4832.0    0.05       0
Bank Sta=4828,4832
Exp/Cntr=0.3,0.1

Type RM Length L Ch R = 1,4830,157,157,157
BEGIN DESCRIPTION:
Trail Creek Tr 5_2 12.0
END DESCRIPTION:
XS GIS Cut Line= 3
      2325574.64      7073840.72      2326048.18      7073801.51
      2326461.44      7073499.87
#Sta/Elev= 30
  4487.1  731.68  4511.5  731.19  4521.6  731.41  4541.6  730.51  4632.0  730.05
  4662.1  729.08  4682.4  729.32  4722.3  729.00  4742.3  728.28  4792.5  728.31
  4832.6  727.60  4892.8  727.37  4919.0  726.62  4924.0  726.91  4971.4  725.73
  4977.6  725.90  4986.1  725.41  5000.4  725.44  5011.1  724.85  5011.4  724.35
  5014.9  724.35  5015.1  724.85  5027.8  725.23  5042.5  726.35  5057.1  728.42
  5063.3  728.23  5071.8  729.47  5235.7  735.99  5335.2  738.95  5473.9  741.65
#Mann=3,-1,0
  4487.1    0.05       0  5011.1    0.04       0  5015.1    0.05       0
Bank Sta=5011.1,5015.1
Exp/Cntr=0.3,0.1

Type RM Length L Ch R = 1,4673,239,239,239
BEGIN DESCRIPTION:
Trail Creek Tr 5_2 11.0
END DESCRIPTION:
XS GIS Cut Line= 3
      2325583.63      7073855.80      2326079.00      7073910.00
      2326375.46      7073907.10
#Sta/Elev= 30
  4496.4  731.45  4532.0  730.71  4562.2  730.43  4572.2  729.96  4592.3  729.63
  4612.5  730.03  4642.6  729.30  4662.8  729.11  4670.4  728.57  4723.1  728.35
  4753.3  727.63  4823.7  726.75  4843.8  726.76  4864.0  725.94  4884.1  724.70
  4904.2  724.28  4924.3  724.01  5004.7  724.68  5012.7  723.89  5013.0  723.39
  5016.5  723.39  5016.7  723.89  5024.7  725.05  5044.7  725.16  5084.7  728.27
  5114.7  729.67  5164.7  731.18  5174.7  731.88  5284.7  735.85  5291.2  736.40
#Mann=3,-1,0
  4496.4    0.05       0  5012.7    0.04       0  5016.7    0.05       0
Bank Sta=5012.7,5016.7
Exp/Cntr=0.3,0.1

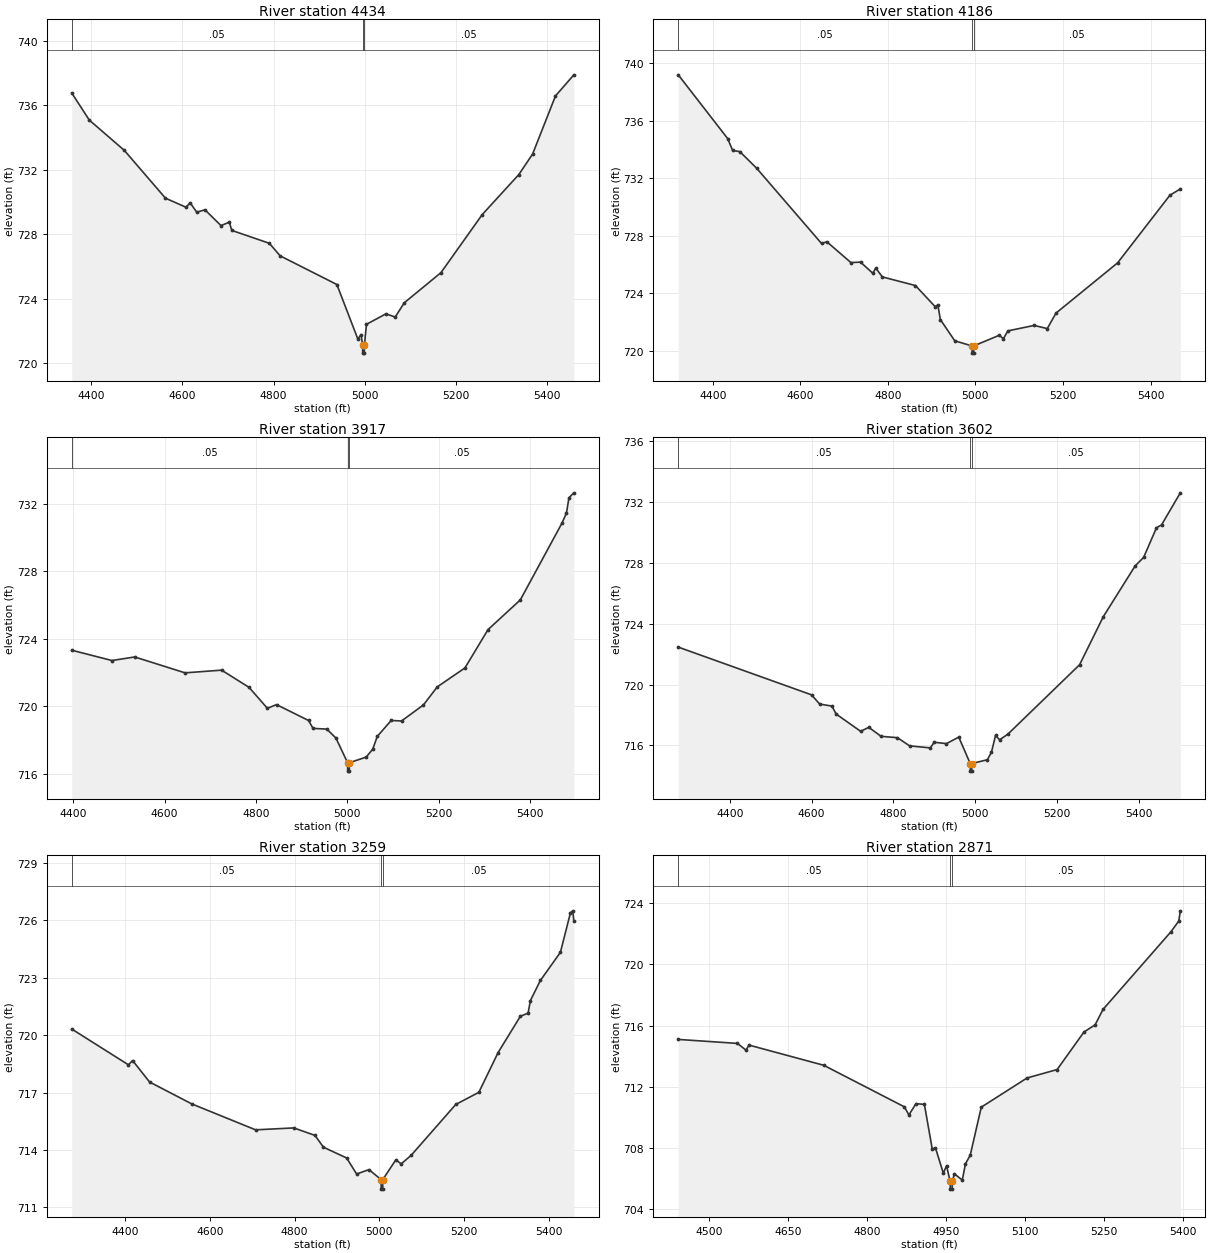
Type RM Length L Ch R = 1,4434,248,248,248
BEGIN DESCRIPTION:
Trail Creek Tr 5_2 10.0
END DESCRIPTION:
XS GIS Cut Line= 3
      2325379.00      7073860.00      2325979.00      7074110.00
      2326429.03      7074060.00
#Sta/Elev= 30
  4356.9  736.77  4395.4  735.09  4472.3  733.21  4562.7  730.24  4607.7  729.68
  4616.9  729.95  4631.5  729.37  4649.4  729.52  4684.6  728.54  4703.0  728.75
  4708.4  728.24  4790.8  727.44  4814.6  726.66  4939.2  724.88  4985.2  721.50
  4992.3  721.77  4995.7  721.12  4995.9  720.62  4999.4  720.62  4999.7  721.12
  5004.2  722.41  5047.1  723.06  5067.3  722.86  5087.4  723.75  5167.9  725.62
  5258.4  729.22  5338.9  731.71  5369.1  732.98  5419.4  736.59  5459.7  737.90
#Mann=3,-1,0
  4356.9    0.05       0  4995.7    0.04       0  4999.7    0.05       0
Bank Sta=4995.7,4999.7
Exp/Cntr=0.3,0.1

Type RM Length L Ch R = 1,4186,269,269,269
BEGIN DESCRIPTION:
Trail Creek Tr 5_2 9.0
END DESCRIPTION:
XS GIS Cut Line= 3
      2325278.96      7074009.98      2325846.09      7074306.45
      2326352.80      7074318.51
#Sta/Elev= 30
  4321.2  739.21  4434.1  734.77  4445.5  733.94  4461.9  733.86  4500.4  732.70
  4648.5  727.46  4660.6  727.58  4715.6  726.13  4737.6  726.16  4765.4  725.39
  4772.6  725.74  4787.4  725.13  4862.9  724.53  4908.0  723.06  4914.2  723.18
  4919.9  722.16  4952.8  720.68  4992.1  720.32  4992.3  719.82  4995.8  719.82
  4996.1  720.32  5054.1  721.06  5064.1  720.83  5074.1  721.37  5134.1  721.75
  5164.1  721.53  5184.1  722.61  5324.8  726.11  5444.2  730.82  5468.0  731.26
#Mann=3,-1,0
  4321.2    0.05       0  4992.1    0.04       0  4996.1    0.05       0
Bank Sta=4992.1,4996.1
Exp/Cntr=0.3,0.1

Type RM Length L Ch R = 1,3917,315,315,315
BEGIN DESCRIPTION:
Trail Creek Tr 5_2 8.0
END DESCRIPTION:
XS GIS Cut Line= 3
      2325321.24      7074577.92      2325929.00      7074560.00
      2326415.06      7074493.61
#Sta/Elev= 30
  4397.0  723.32  4484.8  722.71  4534.8  722.92  4644.9  721.98  4724.9  722.14
  4784.9  721.12  4825.0  719.88  4845.0  720.10  4915.0  719.16  4925.0  718.69
  4955.0  718.65  4975.0  718.12  5000.5  716.66  5000.8  716.16  5004.3  716.16
  5004.5  716.66  5041.2  716.99  5055.5  717.46  5065.6  718.22  5095.9  719.16
  5118.5  719.13  5166.5  720.08  5196.8  721.15  5257.3  722.27  5307.8  724.54
  5378.5  726.30  5469.3  730.83  5479.4  731.44  5484.9  732.35  5495.6  732.64
#Mann=3,-1,0
  4397.0    0.05       0  5000.5    0.04       0  5004.5    0.05       0
Bank Sta=5000.5,5004.5
Exp/Cntr=0.3,0.1

Type RM Length L Ch R = 1,3602,343,343,343
BEGIN DESCRIPTION:
Trail Creek Tr 5_2 7.0
END DESCRIPTION:
XS GIS Cut Line= 3
      2325303.11      7074804.14      2326153.76      7074819.23
      2326514.88      7074710.89
#Sta/Elev= 30
  4274.0  722.47  4599.9  719.33  4619.9  718.72  4649.9  718.59  4660.0  718.07
  4720.0  716.93  4740.0  717.19  4770.0  716.60  4810.0  716.51  4840.0  715.97
  4890.7  715.84  4900.0  716.21  4930.0  716.12  4960.0  716.55  4988.0  714.81
  4988.3  714.31  4991.8  714.31  4992.0  714.81  5030.0  715.06  5040.0  715.56
  5050.0  716.66  5060.0  716.37  5080.0  716.74  5255.5  721.31  5313.2  724.46
  5391.3  727.81  5412.1  728.37  5443.5  730.32  5455.9  730.51  5501.8  732.62
#Mann=3,-1,0
  4274.0    0.05       0  4988.0    0.04       0  4992.0    0.05       0
Bank Sta=4988,4992
Exp/Cntr=0.3,0.1

Type RM Length L Ch R = 1,3259,388,388,388
BEGIN DESCRIPTION:
Trail Creek Tr 5_2 6.0
END DESCRIPTION:
XS GIS Cut Line= 3
      2325375.51      7075166.11      2326008.97      7075160.07
      2326514.88      7074943.26
#Sta/Elev= 30
  4274.6  720.32  4408.1  718.45  4418.1  718.67  4458.1  717.55  4558.1  716.40
  4708.1  715.05  4798.1  715.15  4848.1  714.76  4868.1  714.14  4922.7  713.58
  4946.3  712.74  4975.3  712.97  5004.0  712.45  5004.3  711.95  5007.8  711.95
  5008.0  712.45  5038.7  713.48  5051.4  713.27  5075.0  713.72  5180.2  716.38
  5234.5  717.01  5279.9  719.09  5332.5  720.99  5350.6  721.15  5356.1  721.81
  5379.6  722.86  5426.8  724.33  5450.4  726.39  5455.8  726.50  5458.5  725.98
#Mann=3,-1,0
  4274.6    0.05       0  5004.0    0.04       0  5008.0    0.05       0
Bank Sta=5004,5008
Exp/Cntr=0.3,0.1

Type RM Length L Ch R = 1,2871,420,420,420
BEGIN DESCRIPTION:
Trail Creek Tr 5_2 5.0
END DESCRIPTION:
XS GIS Cut Line= 3
      2325834.03      7075657.77      2326241.23      7075437.58
      2326514.88      7075031.62
#Sta/Elev= 30
  4442.0  715.09  4554.3  714.83  4570.5  714.39  4576.2  714.72  4718.0  713.40
  4871.1  710.68  4879.6  710.15  4893.0  710.89  4909.0  710.84  4923.9  707.92
  4930.0  708.00  4944.9  706.34  4951.0  706.83  4957.9  705.80  4958.2  705.30
  4961.7  705.30  4961.9  705.80  4965.9  706.30  4980.9  705.89  4986.9  706.96
  4995.9  707.51  5016.9  710.66  5103.8  712.57  5160.8  713.12  5211.8  715.58
  5232.8  716.04  5247.8  717.05  5376.7  722.13  5391.7  722.84  5394.5  723.50
#Mann=3,-1,0
  4442.0    0.05       0  4957.9   0.033       0  4961.9    0.05       0
Bank Sta=4957.9,4961.9
Exp/Cntr=0.3,0.1

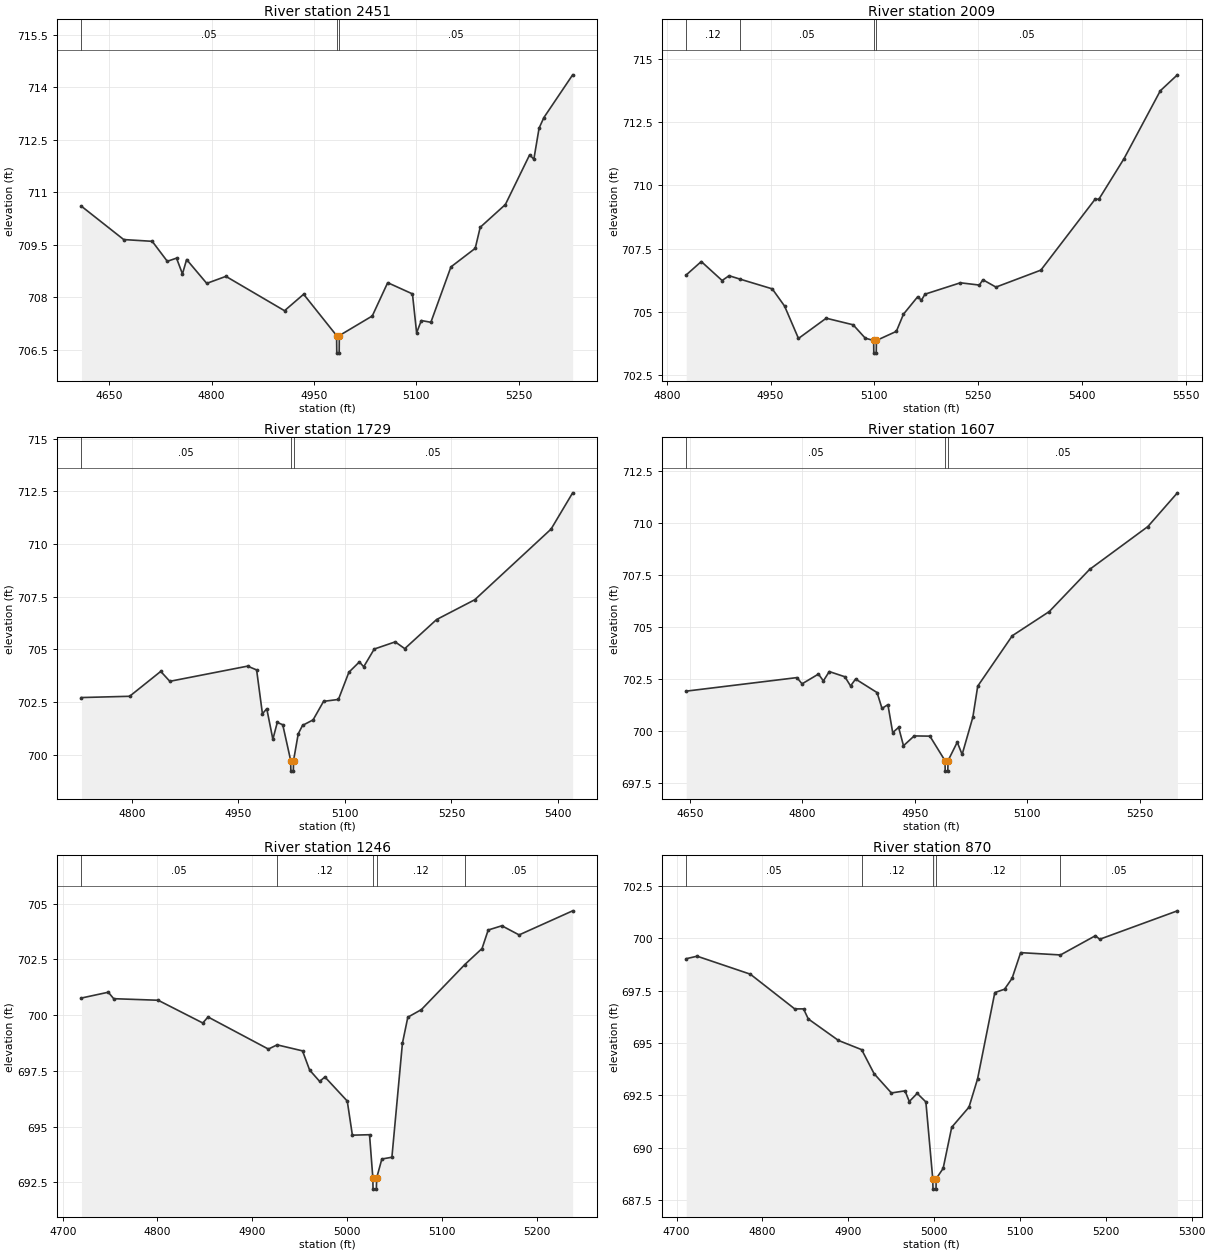
Type RM Length L Ch R = 1,2451,442,442,442
BEGIN DESCRIPTION:
Trail Creek Tr 5_2 4.0
END DESCRIPTION:
XS GIS Cut Line= 3
      2326286.46      7075862.90      2326536.83      7075684.92
      2326778.14      7075350.10
#Sta/Elev= 30
  4609.2  710.60  4671.1  709.65  4712.9  709.60  4735.0  709.03  4748.5  709.12
  4757.2  708.67  4763.3  709.08  4792.8  708.40  4820.9  708.60  4906.8  707.62
  4934.8  708.09  4983.1  706.91  4983.4  706.41  4986.9  706.41  4987.1  706.91
  5035.4  707.47  5058.0  708.42  5094.3  708.10  5100.4  706.99  5107.3  707.34
  5121.3  707.29  5150.7  708.87  5186.3  709.40  5193.6  710.00  5230.5  710.65
  5266.1  712.07  5272.2  711.94  5279.9  712.83  5286.9  713.13  5329.1  714.35
#Mann=3,-1,0
  4609.2    0.05       0  4983.1    0.04       0  4987.1    0.05       0
Bank Sta=4983.1,4987.1
Exp/Cntr=0.3,0.1

Type RM Length L Ch R = 1,2009,280,280,280
BEGIN DESCRIPTION:
Trail Creek Tr 5_2 3.7
END DESCRIPTION:
XS GIS Cut Line= 3
      2326913.87      7076031.75      2326892.76      7075772.39
      2326787.20      7075335.07
#Sta/Elev= 30
  4828.1  706.46  4849.9  706.99  4880.0  706.24  4890.1  706.43  4905.3  706.30
  4952.5  705.91  4970.3  705.23  4990.4  703.95  5030.5  704.75  5069.4  704.49
  5087.0  703.96  5099.1  703.87  5099.3  703.37  5102.8  703.37  5103.1  703.87
  5131.9  704.23  5142.2  704.91  5162.8  705.60  5168.1  705.46  5173.3  705.70
  5224.5  706.15  5251.9  706.06  5257.0  706.27  5275.9  705.98  5340.8  706.65
  5419.4  709.46  5424.6  709.45  5461.1  711.06  5513.5  713.74  5538.2  714.37
#Mann=4,-1,0
  4828.1    0.12       0  4905.3    0.05       0  5099.1   0.033       0
  5103.1    0.05       0
Bank Sta=5099.1,5103.1
Exp/Cntr=0.3,0.1

Type RM Length L Ch R = 1,1729,122,122,122
BEGIN DESCRIPTION:
Trail Creek Tr 5_2 3.5
END DESCRIPTION:
XS GIS Cut Line= 3
      2327299.96      7075853.83      2326913.88      7075579.35
      2326832.43      7075377.25
#Sta/Elev= 30
  4729.1  702.72  4796.9  702.78  4840.7  703.96  4853.5  703.49  4963.0  704.21
  4975.7  704.03  4983.9  701.95  4990.0  702.19  4998.6  700.74  5004.8  701.54
  5012.5  701.43  5023.7  699.73  5023.9  699.23  5027.4  699.23  5027.7  699.73
  5034.3  701.00  5040.4  701.40  5055.2  701.66  5070.0  702.54  5090.9  702.63
  5105.6  703.92  5120.4  704.41  5126.5  704.18  5141.3  705.02  5170.8  705.36
  5184.3  705.04  5229.1  706.42  5282.9  707.36  5390.3  710.71  5420.7  712.43
#Mann=3,-1,0
  4729.1    0.05       0  5023.7    0.04       0  5027.7    0.05       0
Bank Sta=5023.7,5027.7
Exp/Cntr=0.3,0.1

Type RM Length L Ch R = 1,1607,361,361,361
BEGIN DESCRIPTION:
Trail Creek Tr 5_2 3.3
END DESCRIPTION:
XS GIS Cut Line= 3
      2327378.38      7075808.57      2327040.56      7075531.09
      2326959.11      7075328.95
#Sta/Elev= 30
  4645.2  701.93  4792.9  702.58  4799.7  702.28  4821.6  702.75  4828.1  702.42
  4836.0  702.87  4856.8  702.62  4864.4  702.18  4871.1  702.51  4899.8  701.86
  4906.3  701.10  4914.2  701.28  4920.6  699.94  4928.5  700.19  4935.0  699.31
  4949.3  699.78  4970.2  699.77  4990.4  698.59  4990.6  698.09  4994.1  698.09
  4994.4  698.59  5006.7  699.48  5013.2  698.89  5027.5  700.68  5034.0  702.17
  5080.1  704.59  5129.4  705.75  5183.1  707.77  5260.9  709.83  5300.3  711.45
#Mann=3,-1,0
  4645.2    0.05       0  4990.4    0.04       0  4994.4    0.05       0
Bank Sta=4990.4,4994.4
Exp/Cntr=0.3,0.1

Type RM Length L Ch R = 1,1246,376,376,376
BEGIN DESCRIPTION:
Trail Creek Tr 5_2 3.0
END DESCRIPTION:
XS GIS Cut Line= 3
      2327505.06      7075751.23      2327369.35      7075434.56
      2327318.06      7075268.64
#Sta/Elev= 30
  4719.8  700.77  4748.1  701.03  4753.8  700.74  4800.7  700.67  4847.8  699.65
  4853.3  699.92  4917.0  698.48  4926.2  698.67  4953.0  698.40  4960.5  697.54
  4971.1  697.03  4976.6  697.23  5000.2  696.15  5005.6  694.62  5023.7  694.64
  5027.2  692.70  5027.4  692.20  5030.9  692.20  5031.2  692.70  5036.7  693.55
  5047.3  693.63  5058.4  698.74  5064.1  699.91  5078.4  700.25  5124.2  702.27
  5142.4  702.99  5148.9  703.82  5163.3  704.01  5181.5  703.60  5238.0  704.68
#Mann=5,-1,0
  4719.8    0.05       0  4926.2    0.12       0  5027.2    0.07       0
  5031.2    0.12       0  5124.2    0.05       0
Bank Sta=5027.2,5031.2
Exp/Cntr=0.3,0.1

Type RM Length L Ch R = 1,870,470,470,470
BEGIN DESCRIPTION:
Trail Creek Tr 5_2 2.0
END DESCRIPTION:
XS GIS Cut Line= 3
      2327667.95      7075742.27      2327719.24      7075546.17
      2327752.42      7075178.16
#Sta/Elev= 30
  4711.2  699.03  4723.9  699.15  4785.9  698.29  4837.6  696.63  4847.9  696.63
  4853.4  696.15  4888.6  695.12  4915.6  694.68  4930.1  693.53  4950.2  692.61
  4966.1  692.71  4971.1  692.20  4980.3  692.59  4990.4  692.18  4998.4  688.51
  4998.7  688.01  5002.2  688.01  5002.4  688.51  5010.5  689.00  5020.5  690.97
  5040.6  691.93  5050.6  693.28  5070.7  697.41  5082.0  697.57  5090.8  698.09
  5100.8  699.32  5147.2  699.21  5187.9  700.13  5192.9  699.96  5283.4  701.32
#Mann=5,-1,0
  4711.2    0.05       0  4915.6    0.12       0  4998.4    0.07       0
  5002.4    0.12       0  5147.2    0.05       0
Bank Sta=4998.4,5002.4
Exp/Cntr=0.3,0.1

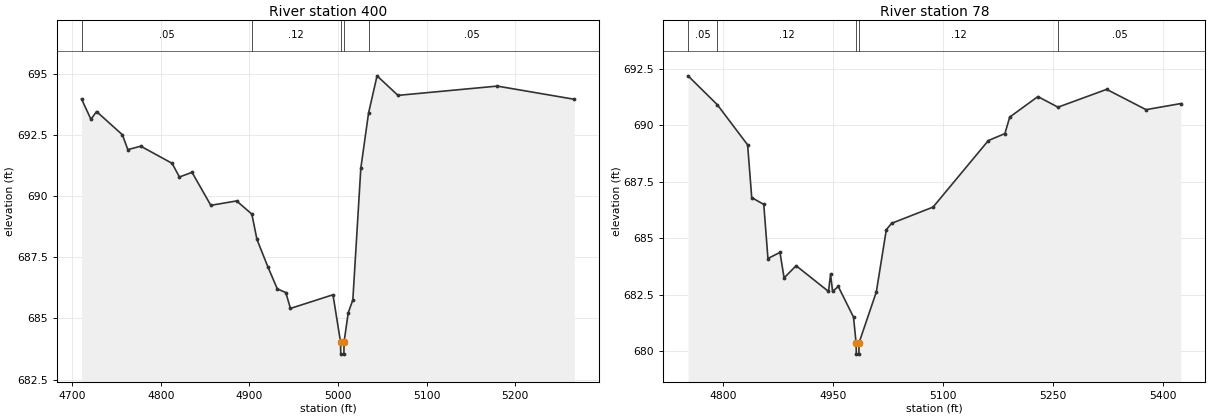
Type RM Length L Ch R = 1,400,322,322,322
BEGIN DESCRIPTION:
Trail Creek Tr 5_2 1.5
END DESCRIPTION:
XS GIS Cut Line= 3
      2327999.76      7075624.59      2328150.58      7075509.97
      2328259.17      7075160.06
#Sta/Elev= 30
  4710.7  693.98  4721.3  693.15  4727.6  693.47  4756.7  692.52  4762.9  691.91
  4777.5  692.05  4812.8  691.35  4821.1  690.79  4835.3  690.98  4856.5  689.63
  4885.6  689.81  4902.8  689.27  4908.5  688.24  4921.0  687.10  4931.5  686.21
  4941.1  686.06  4946.3  685.41  4994.3  685.97  5002.8  684.04  5003.1  683.54
  5006.6  683.54  5006.8  684.04  5011.5  685.23  5016.7  685.76  5025.7  691.15
  5034.4  693.40  5044.0  694.93  5067.6  694.13  5179.6  694.51  5266.5  693.97
#Mann=5,-1,0
  4710.7    0.05       0  4902.8    0.12       0  5002.8    0.07       0
  5006.8    0.12       0  5034.4    0.05       0
Bank Sta=5002.8,5006.8
Exp/Cntr=0.3,0.1

Type RM Length L Ch R = 1,78,0,0,0
BEGIN DESCRIPTION:
Trail Creek Tr 5_2 1.0
END DESCRIPTION:
XS GIS Cut Line= 4
      2328057.08      7075624.59      2328229.01      7075715.08
      2328346.64      7075681.90      2328512.55      7075368.19
#Sta/Elev= 30
  4752.4  692.20  4792.3  690.92  4833.6  689.14  4839.2  686.80  4855.6  686.50
  4861.3  684.10  4877.7  684.37  4883.3  683.24  4899.7  683.78  4943.8  682.64
  4946.6  683.40  4949.4  682.64  4957.1  682.86  4977.9  681.50  4981.4  680.36
  4981.7  679.86  4985.2  679.86  4985.4  680.36  5009.0  682.62  5022.6  685.38
  5029.8  685.66  5086.3  686.38  5161.6  689.33  5184.2  689.64  5190.7  690.37
  5229.1  691.28  5256.5  690.81  5322.8  691.60  5376.5  690.70  5423.8  690.97
#Mann=5,-1,0
  4752.4    0.05       0  4792.3    0.12       0  4981.4    0.07       0
  4985.4    0.12       0  5256.5    0.05       0
Bank Sta=4981.4,4985.4
Exp/Cntr=0.3,0.1

Chan Stop Cuts=-1