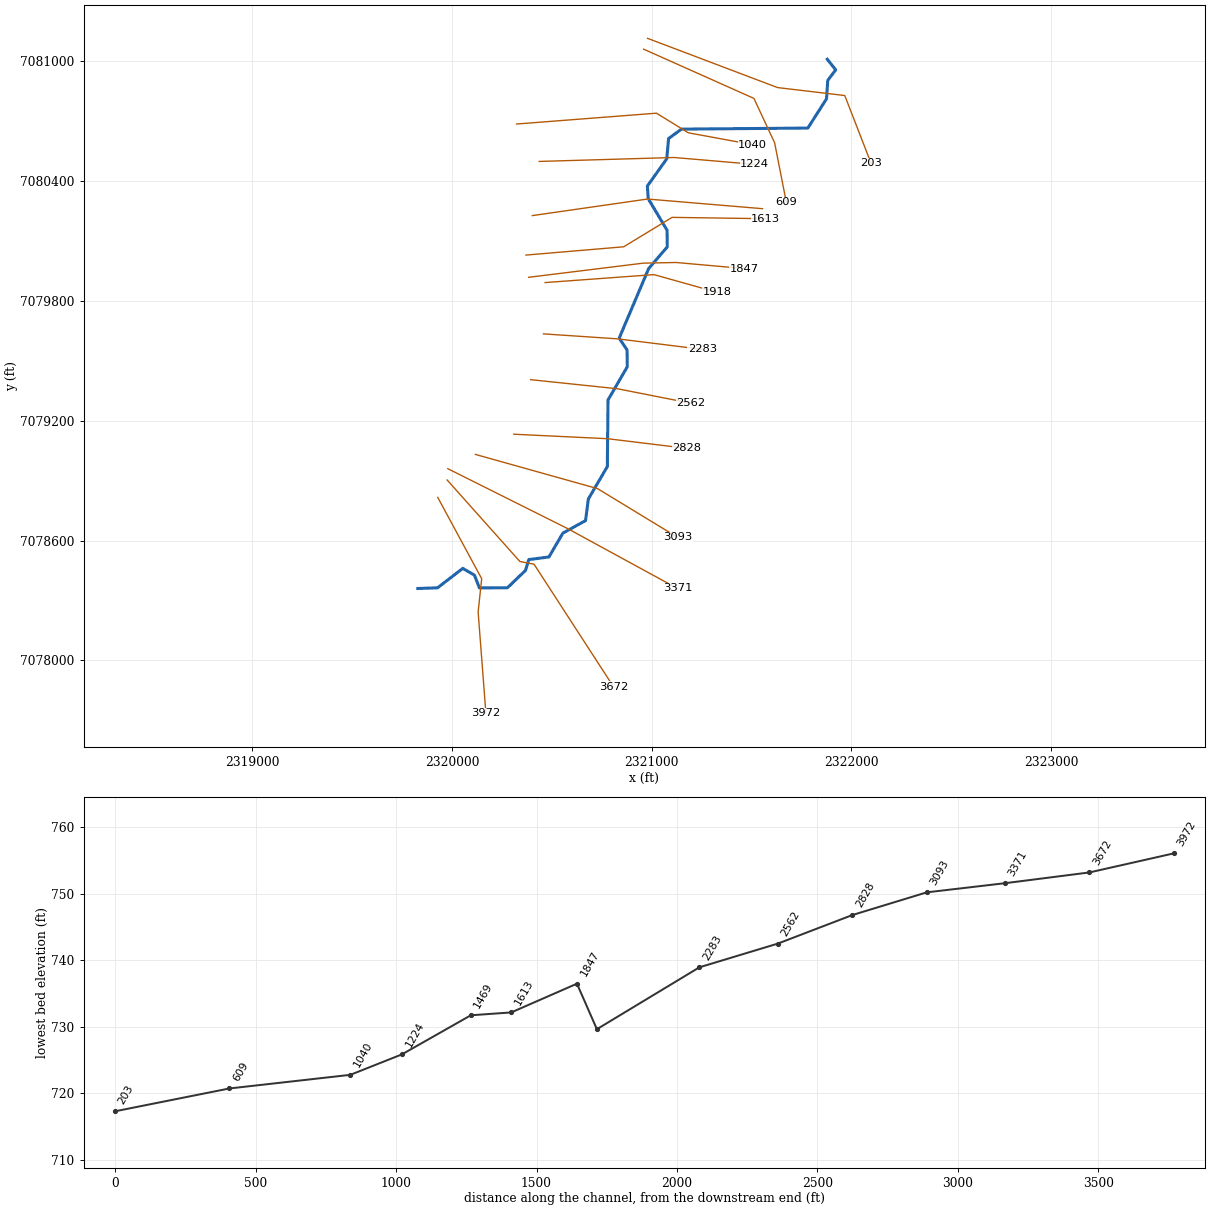
--- Trail Creek Tr 8.prj (project) ---

Proj Title=Trail Creek Tr 8 Base Level Engineering
Current Plan=p01
Default Exp/Contr=0.3,0.1
English Units
Geom File=g01
Flow File=f01
Plan File=p01
BEGIN DESCRIPTION:
Trail Creek Tr 8
END DESCRIPTION:

--- Trail Creek Tr 8.p01 (plan) ---

Plan Title=Multiple Run
Short Identifier=Multiple
Geom File=g01
Flow File=f01
Subcritical Flow
K Sum by GR= 0
Std Step Tol= 0.01
Critical Tol= 0.01
Num of Std Step Trials= 20
Max Error Tol= 0.3
Flow Tol Ratio= 0.001
Split Flow NTrial= 30
Split Flow Tol= 0.02
Split Flow Ratio= 0.02
Log Output Level= 0
Friction Slope Method= 1
Unsteady Friction Slope Method= 2
Unsteady Bridges Friction Slope Method= 1
Parabolic Critical Depth
Global Vel Dist=  1 , 1 , 1
Global Log Level= 0
CheckData=True
Encroach Param= -1, 0, 0, 0
BEGIN DESCRIPTION:
Multiple Run
END DESCRIPTION:

--- Trail Creek Tr 8.f01 (steady flow) ---

Flow Title=Multiple
Number of Profiles=7
Profile Names=10-year,25-year,50-year,1pct_min,100-year,1pct_plu,500-year
River Rch & RM= Trail Creek Tr 8,Reach-1,3972
     368     490     589     352     703    1402    1001
Boundary for River Rch & Prof#=Trail Creek Tr 8,Reach-1,1
Up Type=0
Dn Type=3
Dn Slope=0.005
Boundary for River Rch & Prof#=Trail Creek Tr 8,Reach-1,2
Up Type=0
Dn Type=3
Dn Slope=0.005
Boundary for River Rch & Prof#=Trail Creek Tr 8,Reach-1,3
Up Type=0
Dn Type=3
Dn Slope=0.005
Boundary for River Rch & Prof#=Trail Creek Tr 8,Reach-1,4
Up Type=0
Dn Type=3
Dn Slope=0.005
Boundary for River Rch & Prof#=Trail Creek Tr 8,Reach-1,5
Up Type=0
Dn Type=3
Dn Slope=0.005
Boundary for River Rch & Prof#=Trail Creek Tr 8,Reach-1,6
Up Type=0
Dn Type=3
Dn Slope=0.005
Boundary for River Rch & Prof#=Trail Creek Tr 8,Reach-1,7
Up Type=0
Dn Type=3
Dn Slope=0.005

--- Trail Creek Tr 8.g01 (geometry) ---

Geom Title=Existing Conditions

River Reach=Trail Creek Tr 8,Reach-1
Reach XY= 30
      2319829.00      7078360.00      2319927.59      7078363.40
      2320054.08      7078460.61      2320112.41      7078427.00
      2320137.31      7078363.09      2320277.54      7078363.52
      2320368.11      7078450.60      2320384.48      7078504.74
      2320485.41      7078517.77      2320555.17      7078637.13
      2320668.61      7078699.90      2320682.83      7078808.41
      2320777.80      7078970.50      2320781.24      7079304.07
      2320877.91      7079470.55      2320876.64      7079554.11
      2320837.08      7079613.30      2320984.85      7079962.29
      2321078.06      7080070.48      2321076.86      7080154.03
      2320982.67      7080311.59      2320978.23      7080375.09
      2321075.37      7080511.51      2321084.41      7080612.71
      2321148.87      7080660.09      2321781.70      7080665.36
      2321875.18      7080811.58      2321881.46      7080904.12
      2321921.37      7080956.82      2321879.00      7081010.00

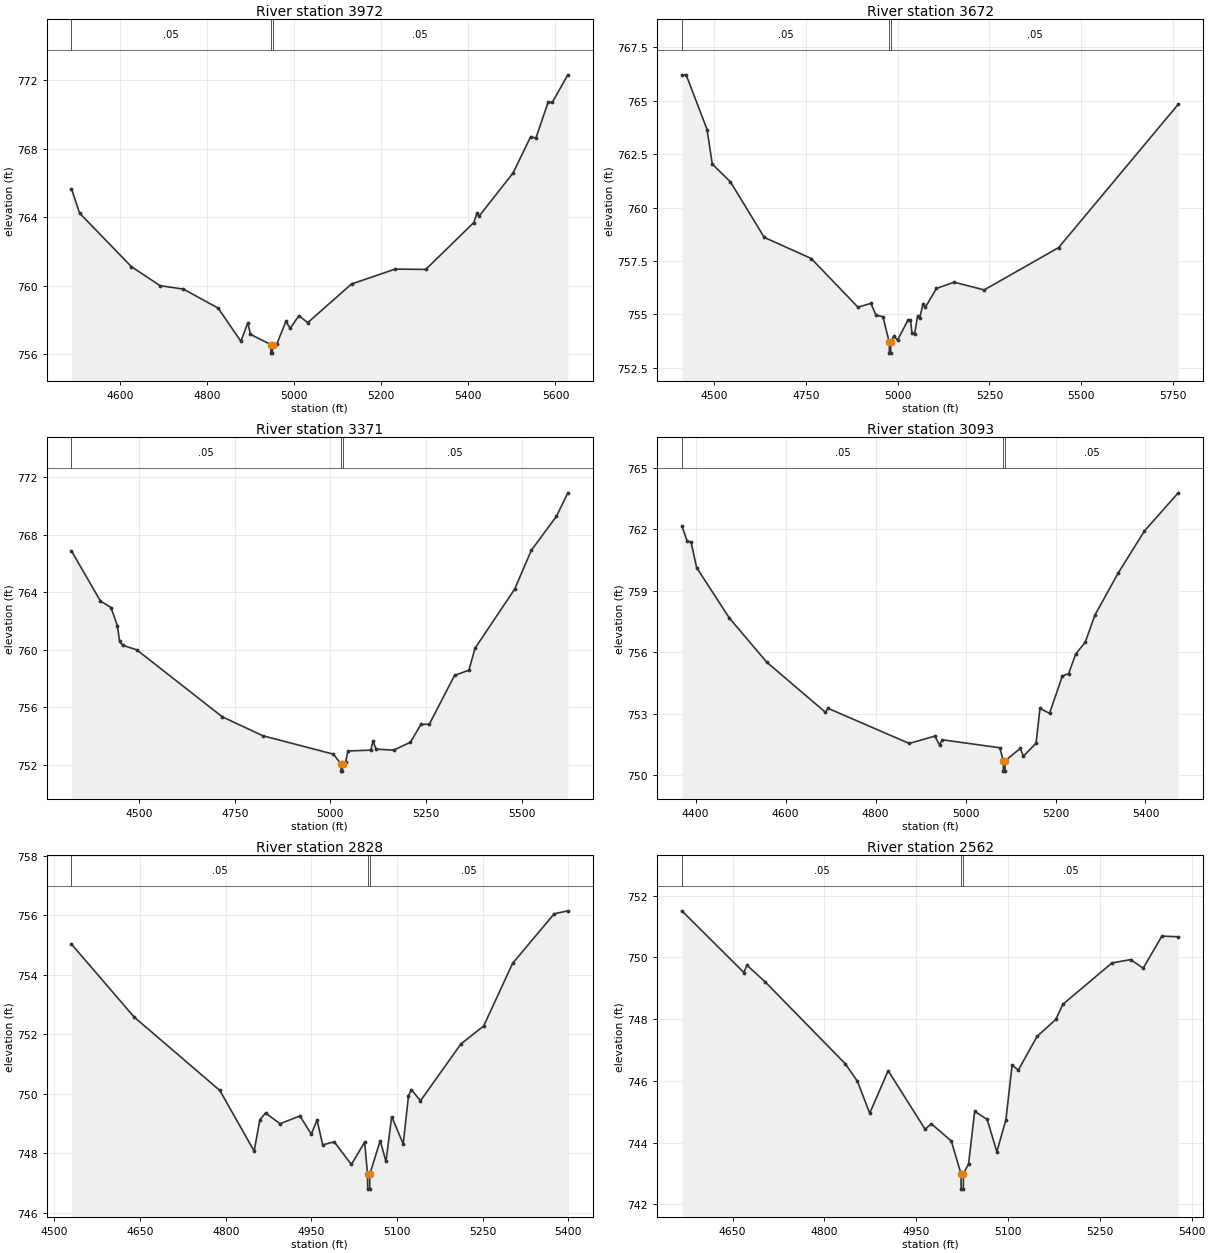
Type RM Length L Ch R = 1,3972,300,300,300
BEGIN DESCRIPTION:
Trail Creek Tr 8 11.0
END DESCRIPTION:
XS GIS Cut Line= 4
      2319928.64      7078816.33      2320148.75      7078408.89
      2320130.87      7078242.56      2320169.81      7077734.74
#Sta/Elev= 30
  4488.7  765.65  4507.3  764.23  4626.4  761.10  4692.1  759.99  4745.9  759.79
  4825.5  758.68  4877.7  756.74  4893.7  757.83  4899.6  757.15  4946.3  756.55
  4946.6  756.05  4950.1  756.05  4950.3  756.55  4960.7  756.61  4980.9  757.90
  4990.9  757.50  5011.0  758.24  5031.1  757.83  5131.7  760.09  5232.0  760.96
  5302.2  760.94  5412.5  763.68  5419.6  764.21  5424.6  764.05  5502.8  766.58
  5542.9  768.69  5555.2  768.62  5583.0  770.70  5593.0  770.71  5628.4  772.31
#Mann=3,-1,0
  4488.7    0.05       0  4946.3   0.035       0  4950.3    0.05       0
Bank Sta=4946.3,4950.3
Exp/Cntr=0.3,0.1

Type RM Length L Ch R = 1,3672,301,301,301
BEGIN DESCRIPTION:
Trail Creek Tr 8 10.0
END DESCRIPTION:
XS GIS Cut Line= 4
      2319975.79      7078903.18      2320339.95      7078495.18
      2320410.76      7078481.70      2320808.62      7077868.05
#Sta/Elev= 30
  4413.2  766.22  4424.8  766.22  4481.7  763.66  4495.9  762.04  4545.2  761.21
  4637.2  758.61  4765.1  757.62  4892.2  755.34  4927.3  755.52  4941.5  754.96
  4960.1  754.90  4977.5  753.69  4977.7  753.19  4981.2  753.19  4981.5  753.69
  4989.7  753.99  4999.8  753.80  5028.7  754.75  5035.1  754.75  5039.1  754.13
  5046.1  754.07  5054.3  754.91  5060.2  754.84  5069.4  755.50  5075.4  755.33
  5105.7  756.22  5153.9  756.51  5235.6  756.15  5438.0  758.13  5763.5  764.84
#Mann=3,-1,0
  4413.2    0.05       0  4977.5   0.035       0  4981.5    0.05       0
Bank Sta=4977.5,4981.5
Exp/Cntr=0.3,0.1

Type RM Length L Ch R = 1,3371,278,278,278
BEGIN DESCRIPTION:
Trail Creek Tr 8 9.0
END DESCRIPTION:
XS GIS Cut Line= 3
      2319978.97      7078960.01      2320579.00      7078660.00
      2321128.96      7078360.02
#Sta/Elev= 30
  4323.4  766.89  4398.9  763.41  4426.8  762.95  4443.6  761.66  4449.2  760.59
  4457.6  760.32  4493.9  760.01  4717.5  755.35  4823.7  754.03  5008.0  752.75
  5027.8  752.07  5028.1  751.57  5031.6  751.57  5031.8  752.07  5039.8  752.19
  5046.0  752.97  5105.8  753.03  5111.5  753.66  5119.5  753.10  5165.1  753.03
  5209.3  753.58  5236.8  754.82  5258.6  754.83  5324.6  758.23  5362.1  758.59
  5378.2  760.12  5481.7  764.23  5525.3  766.93  5590.8  769.29  5620.7  770.93
#Mann=3,-1,0
  4323.4    0.05       0  5027.8   0.033       0  5031.8    0.05       0
Bank Sta=5027.8,5031.8
Exp/Cntr=0.3,0.1

Type RM Length L Ch R = 1,3093,265,265,265
BEGIN DESCRIPTION:
Trail Creek Tr 8 8.0
END DESCRIPTION:
XS GIS Cut Line= 3
      2320117.44      7079031.30      2320729.00      7078860.00
      2321128.95      7078616.58
#Sta/Elev= 30
  4369.5  762.17  4381.5  761.41  4389.8  761.39  4402.3  760.13  4475.0  757.67
  4558.0  755.52  4688.7  753.07  4693.9  753.27  4874.8  751.55  4931.9  751.91
  4942.3  751.47  4948.2  751.73  5076.3  751.34  5083.9  750.70  5084.2  750.20
  5087.7  750.20  5087.9  750.70  5121.7  751.31  5128.6  750.93  5156.8  751.56
  5165.4  753.26  5186.7  753.02  5215.3  754.84  5229.3  754.96  5244.8  755.91
  5266.1  756.49  5287.5  757.81  5339.7  759.88  5397.8  761.92  5472.8  763.78
#Mann=3,-1,0
  4369.5    0.05       0  5083.9   0.033       0  5087.9    0.05       0
Bank Sta=5083.9,5087.9
Exp/Cntr=0.3,0.1

Type RM Length L Ch R = 1,2828,266,266,266
BEGIN DESCRIPTION:
Trail Creek Tr 8 7.0
END DESCRIPTION:
XS GIS Cut Line= 3
      2320309.57      7079132.47      2320779.00      7079110.00
      2321175.11      7079061.79
#Sta/Elev= 30
  4530.0  755.03  4639.6  752.58  4789.7  750.11  4849.8  748.07  4859.8  749.12
  4869.8  749.35  4895.1  748.99  4929.9  749.25  4949.9  748.64  4959.9  749.11
  4969.9  748.28  4990.0  748.38  5020.1  747.62  5043.3  748.37  5048.3  747.29
  5048.6  746.79  5052.1  746.79  5052.3  747.29  5070.5  748.42  5080.6  747.72
  5090.6  749.23  5110.8  748.31  5120.0  749.92  5125.0  750.14  5141.0  749.76
  5211.7  751.67  5251.8  752.28  5302.2  754.38  5375.1  756.05  5399.0  756.15
#Mann=3,-1,0
  4530.0    0.05       0  5048.3   0.033       0  5052.3    0.05       0
Bank Sta=5048.3,5052.3
Exp/Cntr=0.3,0.1

Type RM Length L Ch R = 1,2562,279,279,279
BEGIN DESCRIPTION:
Trail Creek Tr 8 6.0
END DESCRIPTION:
XS GIS Cut Line= 3
      2320393.86      7079405.59      2320829.00      7079360.00
      2321195.23      7079287.80
#Sta/Elev= 30
  4567.3  751.51  4668.5  749.51  4673.5  749.75  4703.2  749.21  4833.9  746.56
  4854.0  745.99  4874.1  744.95  4904.3  746.33  4964.6  744.43  4974.7  744.61
  5007.4  744.05  5023.2  742.99  5023.5  742.49  5027.0  742.49  5027.2  742.99
  5035.6  743.31  5045.6  745.01  5066.0  744.75  5081.8  743.70  5096.6  744.74
  5106.7  746.51  5116.9  746.35  5147.5  747.44  5178.1  747.99  5189.6  748.48
  5269.8  749.82  5300.4  749.93  5320.8  749.65  5351.4  750.69  5378.1  750.67
#Mann=3,-1,0
  4567.3    0.05       0  5023.2   0.033       0  5027.2    0.05       0
Bank Sta=5023.2,5027.2
Exp/Cntr=0.3,0.1

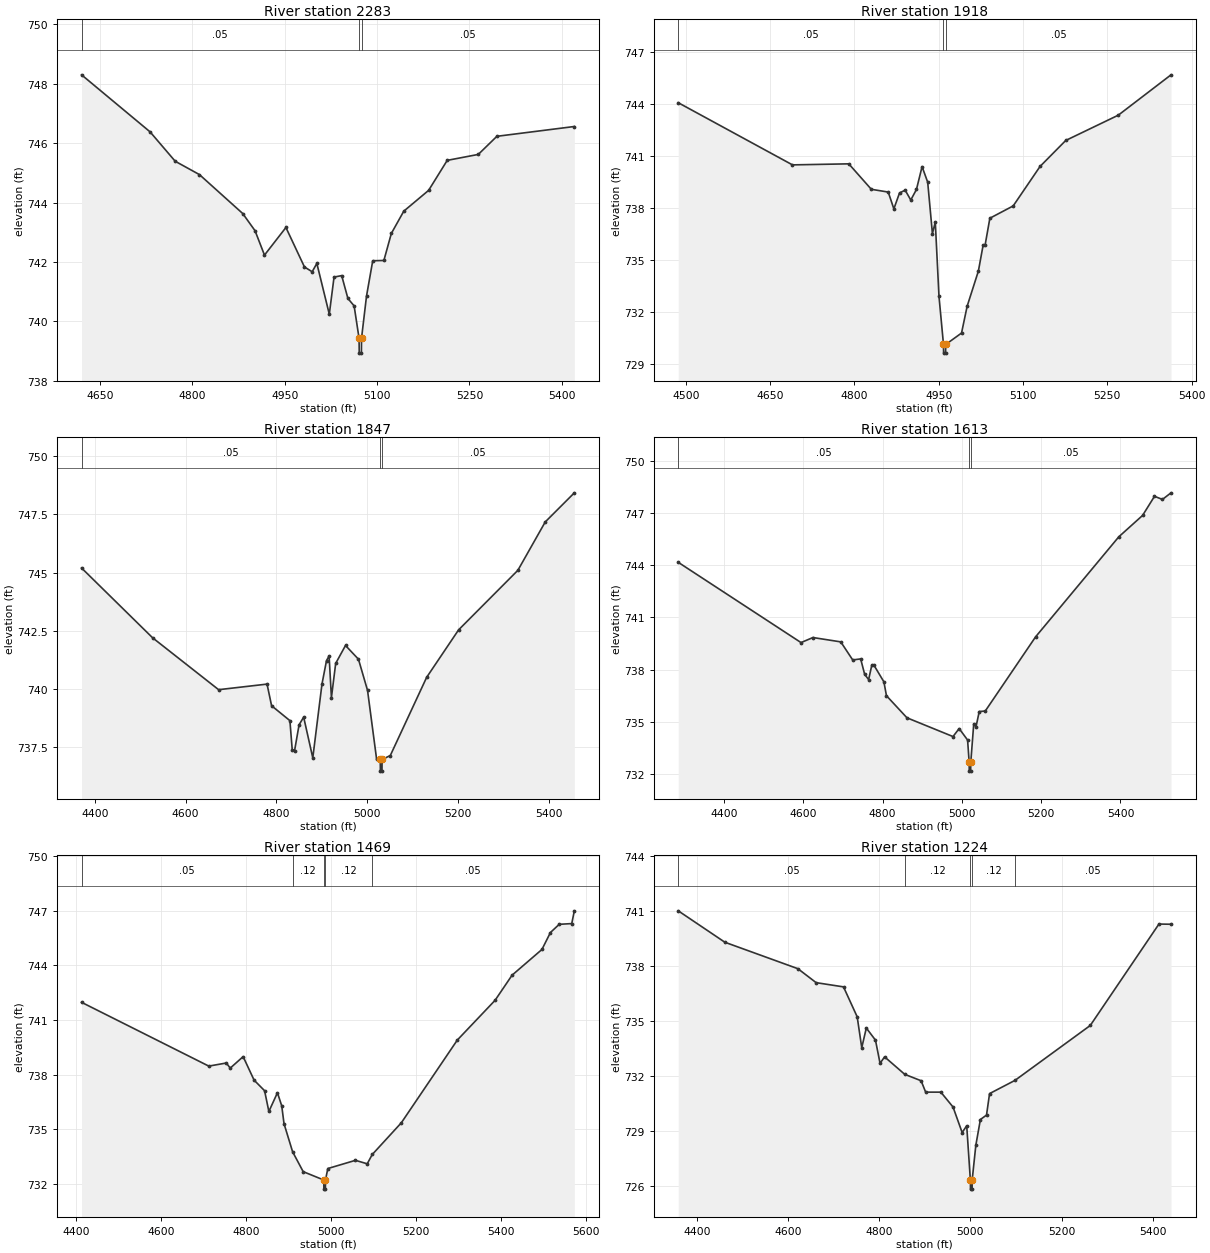
Type RM Length L Ch R = 1,2283,365,365,365
BEGIN DESCRIPTION:
Trail Creek Tr 8 5.0
END DESCRIPTION:
XS GIS Cut Line= 3
      2320458.00      7079634.87      2320829.00      7079610.00
      2321253.72      7079557.32
#Sta/Elev= 30
  4620.4  748.30  4731.6  746.38  4772.4  745.39  4811.8  744.94  4882.0  743.63
  4902.0  743.05  4917.3  742.23  4952.1  743.16  4982.2  741.83  4994.7  741.67
  5002.3  741.95  5022.5  740.24  5030.2  741.49  5042.6  741.54  5052.7  740.77
  5062.8  740.52  5070.8  739.43  5071.1  738.93  5074.6  738.93  5074.8  739.43
  5082.9  740.85  5093.0  742.04  5111.1  742.05  5123.2  742.96  5143.4  743.71
  5183.7  744.41  5213.9  745.42  5264.3  745.62  5294.5  746.23  5420.2  746.56
#Mann=3,-1,0
  4620.4    0.05       0  5070.8   0.033       0  5074.8    0.05       0
Bank Sta=5070.8,5074.8
Exp/Cntr=0.3,0.1

Type RM Length L Ch R = 1,1918,71,71,71
BEGIN DESCRIPTION:
Trail Creek Tr 8 4.0
END DESCRIPTION:
XS GIS Cut Line= 3
      2320466.38      7079891.73      2321010.95      7079931.60
      2321329.36      7079842.42
#Sta/Elev= 30
  4486.6  744.09  4689.8  740.50  4790.0  740.56  4830.1  739.09  4860.2  738.93
  4870.2  737.96  4880.3  738.88  4890.3  739.04  4900.3  738.47  4910.4  739.08
  4920.4  740.40  4930.4  739.50  4938.8  736.53  4943.9  737.20  4950.5  732.90
  4958.5  730.13  4958.7  729.63  4962.2  729.63  4962.5  730.13  4990.6  730.79
  5000.6  732.34  5020.6  734.37  5029.1  735.88  5032.6  735.88  5041.0  737.42
  5082.5  738.13  5130.3  740.41  5176.0  741.91  5269.5  743.37  5363.3  745.70
#Mann=3,-1,0
  4486.6    0.05       0  4958.5   0.033       0  4962.5    0.05       0
Bank Sta=4958.5,4962.5
Exp/Cntr=0.3,0.1

Type RM Length L Ch R = 1,1847,234,234,234
BEGIN DESCRIPTION:
Trail Creek Tr 8 3.5
END DESCRIPTION:
XS GIS Cut Line= 4
      2320383.82      7079918.12      2320957.00      7079988.92
      2321122.22      7079992.29      2321462.78      7079961.94
#Sta/Elev= 30
  4370.9  745.20  4527.3  742.20  4672.6  739.97  4779.2  740.21  4789.2  739.28
  4829.5  738.64  4834.7  737.37  4839.8  737.35  4849.7  738.46  4859.8  738.79
  4879.9  737.04  4900.1  740.21  4910.1  741.22  4915.8  741.42  4920.9  739.63
  4930.3  741.10  4951.9  741.87  4980.4  741.28  5000.4  739.94  5020.4  736.98
  5028.4  736.97  5028.7  736.47  5032.2  736.47  5032.4  736.97  5050.5  737.14
  5130.5  740.50  5200.8  742.54  5331.3  745.10  5391.6  747.18  5455.6  748.43
#Mann=3,-1,0
  4370.9    0.05       0  5028.4   0.033       0  5032.4    0.05       0
Bank Sta=5028.4,5032.4
Exp/Cntr=0.3,0.1

Type RM Length L Ch R = 1,1613,144,144,144
BEGIN DESCRIPTION:
Trail Creek Tr 8 3.4
END DESCRIPTION:
XS GIS Cut Line= 4
      2320370.33      7080029.39      2320859.87      7080070.95
      2321101.99      7080218.21      2321570.66      7080211.46
#Sta/Elev= 30
  4284.2  744.17  4594.0  739.55  4624.1  739.84  4694.3  739.59  4724.4  738.55
  4744.5  738.61  4754.6  737.72  4764.6  737.42  4772.6  738.25  4777.9  738.25
  4803.1  737.29  4809.6  736.49  4861.3  735.22  4977.5  734.14  4993.0  734.60
  5014.3  733.94  5018.3  732.65  5018.5  732.15  5022.0  732.15  5022.3  732.65
  5029.8  734.87  5035.6  734.71  5043.7  735.58  5058.9  735.61  5185.9  739.88
  5395.9  745.64  5455.9  746.87  5485.9  747.97  5505.9  747.79  5527.6  748.17
#Mann=3,-1,0
  4284.2    0.05       0  5018.3   0.033       0  5022.3    0.05       0
Bank Sta=5018.3,5022.3
Exp/Cntr=0.3,0.1

Type RM Length L Ch R = 1,1469,245,245,245
BEGIN DESCRIPTION:
Trail Creek Tr 8 3.0
END DESCRIPTION:
XS GIS Cut Line= 3
      2320402.32      7080227.05      2320979.00      7080310.00
      2321555.06      7080261.65
#Sta/Elev= 30
  4412.7  741.97  4712.4  738.47  4753.7  738.64  4762.9  738.36  4793.3  738.99
  4819.1  737.70  4843.8  737.12  4853.9  735.98  4874.1  737.01  4884.2  736.29
  4889.6  735.31  4909.8  733.77  4934.7  732.68  4983.2  732.22  4983.5  731.72
  4987.0  731.72  4987.2  732.22  4992.8  732.85  5057.8  733.30  5085.6  733.11
  5097.4  733.62  5165.9  735.36  5297.8  739.90  5386.7  742.08  5426.8  743.46
  5497.1  744.87  5517.1  745.80  5537.8  746.25  5567.3  746.29  5573.4  746.99
#Mann=5,-1,0
  4412.7    0.05       0  4909.8    0.12       0  4983.2    0.07       0
  4987.2    0.12       0  5097.4    0.05       0
Bank Sta=4983.2,4987.2
Exp/Cntr=0.3,0.1

Type RM Length L Ch R = 1,1224,184,184,184
BEGIN DESCRIPTION:
Trail Creek Tr 8 2.0
END DESCRIPTION:
XS GIS Cut Line= 3
      2320436.83      7080498.25      2321112.37      7080517.97
      2321515.38      7080483.57
#Sta/Elev= 30
  4359.5  741.00  4461.7  739.29  4621.8  737.85  4661.8  737.09  4721.8  736.86
  4751.8  735.23  4761.8  733.55  4771.8  734.62  4791.9  733.96  4801.9  732.70
  4811.9  733.05  4856.0  732.10  4891.9  731.75  4901.9  731.13  4935.2  731.13
  4961.9  730.32  4981.9  728.93  4991.9  729.30  4999.9  726.35  5000.2  725.85
  5003.7  725.85  5003.9  726.35  5011.9  728.24  5021.9  729.64  5035.3  729.88
  5042.0  731.05  5097.7  731.77  5262.8  734.76  5413.3  740.28  5439.8  740.27
#Mann=5,-1,0
  4359.5    0.05       0  4856.0    0.12       0  4999.9    0.07       0
  5003.9    0.12       0  5097.7    0.05       0
Bank Sta=4999.9,5003.9
Exp/Cntr=0.3,0.1

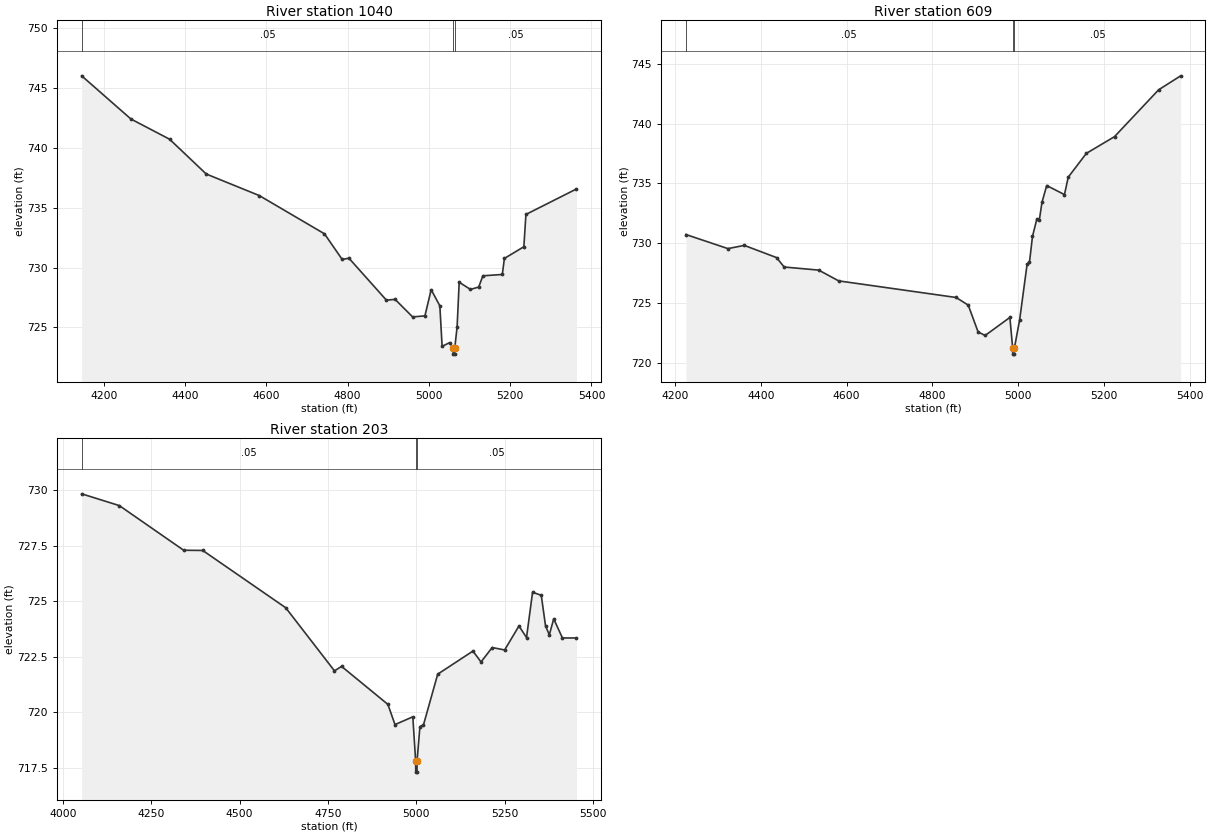
Type RM Length L Ch R = 1,1040,431,431,431
BEGIN DESCRIPTION:
Trail Creek Tr 8 1.0
END DESCRIPTION:
XS GIS Cut Line= 4
      2320323.38      7080685.63      2321023.61      7080739.87
      2321183.52      7080641.59      2321505.39      7080582.35
#Sta/Elev= 30
  4145.7  746.04  4266.9  742.43  4362.0  740.74  4452.2  737.83  4582.6  736.03
  4743.1  732.83  4786.6  730.69  4803.3  730.79  4895.5  727.28  4916.8  727.35
  4960.0  725.88  4990.2  725.97  5005.6  728.16  5026.9  726.81  5032.5  723.42
  5051.5  723.74  5059.6  723.27  5059.9  722.77  5063.4  722.77  5063.6  723.27
  5069.4  725.05  5074.5  728.78  5102.3  728.18  5122.5  728.38  5132.8  729.32
  5180.6  729.43  5185.7  730.77  5233.6  731.75  5238.7  734.45  5363.0  736.58
#Mann=3,-1,0
  4145.7    0.05       0  5059.6   0.033       0  5063.6    0.05       0
Bank Sta=5059.6,5063.6
Exp/Cntr=0.3,0.1

Type RM Length L Ch R = 1,609,406,406,406
BEGIN DESCRIPTION:
Trail Creek Tr 8 0.6
END DESCRIPTION:
XS GIS Cut Line= 4
      2320959.50      7081060.39      2321511.78      7080813.83
      2321615.33      7080591.94      2321673.88      7080294.33
#Sta/Elev= 30
  4225.4  730.73  4323.4  729.55  4361.5  729.82  4436.6  728.80  4454.4  728.01
  4535.0  727.75  4581.4  726.85  4855.1  725.46  4883.4  724.82  4906.3  722.58
  4922.7  722.28  4980.4  723.79  4986.9  721.22  4987.2  720.72  4990.7  720.72
  4990.9  721.22  5003.2  723.60  5020.6  728.26  5026.1  728.41  5033.1  730.58
  5043.4  732.04  5049.0  731.93  5055.2  733.42  5066.2  734.83  5107.6  734.07
  5116.4  735.53  5158.6  737.52  5224.2  738.92  5327.0  742.84  5378.4  744.01
#Mann=3,-1,0
  4225.4    0.05       0  4986.9    0.04       0  4990.9    0.05       0
Bank Sta=4986.9,4990.9
Exp/Cntr=0.3,0.1

Type RM Length L Ch R = 1,203,0,0,0
BEGIN DESCRIPTION:
Trail Creek Tr 8 0.4
END DESCRIPTION:
XS GIS Cut Line= 4
      2320979.24      7081114.62      2321630.13      7080868.08
      2321966.56      7080828.28      2322098.56      7080488.41
#Sta/Elev= 30
  4053.3  729.83  4159.9  729.30  4341.8  727.29  4395.8  727.28  4630.5  724.70
  4768.3  721.86  4788.5  722.06  4919.4  720.35  4939.5  719.44  4989.9  719.79
  4997.9  717.80  4998.2  717.30  5001.7  717.30  5001.9  717.80  5010.0  719.35
  5020.1  719.43  5060.3  721.71  5159.9  722.75  5182.8  722.26  5214.4  722.91
  5249.6  722.80  5290.1  723.88  5311.5  723.36  5328.6  725.40  5353.2  725.26
  5365.2  723.89  5375.9  723.48  5388.4  724.20  5413.0  723.34  5452.7  723.34
#Mann=3,-1,0
  4053.3    0.05       0  4997.9    0.04       0  5001.9    0.05       0
Bank Sta=4997.9,5001.9
Exp/Cntr=0.3,0.1

Chan Stop Cuts=-1