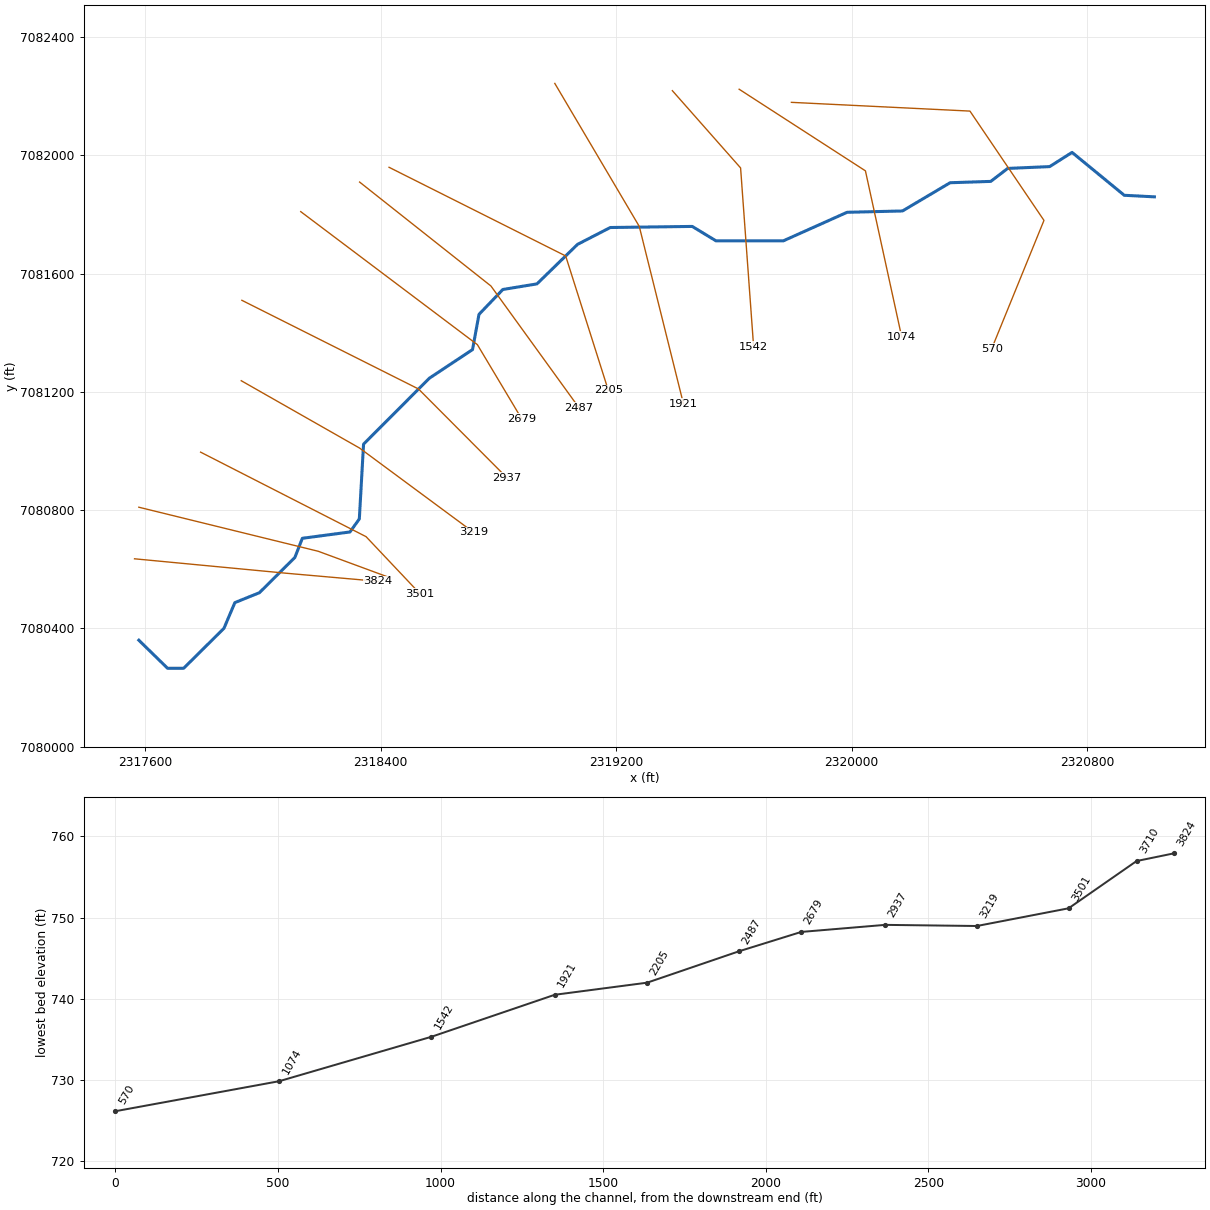
--- Trail Creek Tr 9.prj (project) ---

Proj Title=Trail Creek Tr 9 Base Level Engineering
Current Plan=p01
Default Exp/Contr=0.3,0.1
English Units
Geom File=g01
Flow File=f01
Plan File=p01
Y Axis Title=Elevation
X Axis Title(PF)=Main Channel Distance
X Axis Title(XS)=Station
BEGIN DESCRIPTION:
Trail Creek Tr 9
END DESCRIPTION:
DSS Export Rating Curves= 0
DSS Export Rating Curve Sorted= 0
DSS Export Volume Flow Curves= 0
DXF OffsetX= 0
DXF OffsetY= 0
DXF ScaleX= 1
DXF ScaleY= 10

--- Trail Creek Tr 9.p01 (plan) ---

Plan Title=Multiple Run
Program Version=4.10
Short Identifier=Multiple
Geom File=g01
Flow File=f01
Subcritical Flow
K Sum by GR= 0
Std Step Tol= 0.01
Critical Tol= 0.01
Num of Std Step Trials= 20
Max Error Tol= 0.3
Flow Tol Ratio= 0.001
Split Flow NTrial= 30
Split Flow Tol= 0.02
Split Flow Ratio= 0.02
Log Output Level= 0
Friction Slope Method= 1
Unsteady Friction Slope Method= 2
Unsteady Bridges Friction Slope Method= 1
Parabolic Critical Depth
Global Vel Dist= 1 , 1 , 1
Global Log Level= 0
CheckData=True
Encroach Param=-1 ,0,0, 0
BEGIN DESCRIPTION:
Multiple Run
END DESCRIPTION:
Computation Interval=1HOUR
Output Interval=1HOUR
Run HTab= 0
Run UNet= 0
Run PostProcess= 0
Run WQNet= 0
UNET Theta= 1
UNET Theta Warmup= 1
UNET ZTol= 0.02
UNET ZSATol= 0.05
UNET MxIter= 20
UNET MaxInSteps= 0
UNET DtIC= 0
UNET DtMin= 0
UNET MaxCRTS= 20
UNET WFStab= 2
UNET SFStab= 1
UNET WFX= 1
UNET SFX= 1
UNET DSS MLevel= 4
UNET DZMax Abort= 100
UNET Convert EG Bridges= 0
UNET Use Existing IB Tables=-1
UNET Froude Reduction=False
UNET Froude Limit= 1
UNET Froude Power= 10
UNET Time Slicing=0,0, 5
UNET Junction Losses=0
Instantaneous Interval=1HOUR
Write IC File= 0
Write IC File at Sim End=0
Echo Input=False
Echo Parameters=False
Echo Output=False
Write Detailed= 0
WQ AD Non Conservative
WQ ULTIMATE=-1
WQ Max Comp Step=1HOUR
WQ Output Interval=15MIN
WQ Output Selected Increments= 0
WQ Output face flow=0
WQ Output face velocity=0
WQ Output face area=0
WQ Output face dispersion=0
WQ Output cell volume=0
WQ Output cell surface area=0
WQ Output cell continuity=0
WQ Output cumulative cell continuity=0
WQ Output face conc=0
WQ Output face dconc_dx=0
WQ Output face courant=0
WQ Output face peclet=0
WQ Output face adv mass=0
WQ Output face disp mass=0
WQ Output cell mass=0
WQ Output cell source sink temp=0
WQ Output cell source sink nsm=0
WQ Output MaxMinRange=-1
WQ Daily Max Min Mean=-1
WQ Daily Range=0
WQ Daily Time=0
WQ Create Restart=0
WQ Fixed Restart=0
WQ System Summary=0
WQ Use Fixed Temperature=0
Sorting and Armoring Iterations= 10
XS Update Threshold= 0.02
Hydraulics Update Threshold= 0.02
Energy Slope Method= 1
Volume Change Method= 0
XS Weighting Method= 0
Number of US Weighted Cross Sections= 1
Number of DS Weighted Cross Sections= 1
Upstream XS Weight=0.25
Main XS Weight=0.5
Downstream XS Weight=0.25
Number of DS XS's Weighted with US Boundary= 1
Upstream Boundary Weight= 1
Weight of XSs Associated with US Boundary= 0
Number of US XS's Weighted with DS Boundary= 1
Downstream Boundary Weight= 0.5
Weight of XSs Associated with DS Boundary= 0.5
Sediment Output Level= 4
Mass or Volume Output= 0
Output Increment Type= 1
Profile and TS Output Increment= 10
XS Output Flag= 0
XS Output Increment= 10
Disregard all LS=0
Disregard all Conn=0
Disregard all Breaches=0
Disregard all Pumps=0

--- Trail Creek Tr 9.f01 (steady flow) ---

Flow Title=Multiple
Number of Profiles=7
Profile Names=10-year,25-year,50-year,1pct_min,100-year,1pct_plu,500-year
River Rch & RM= Trail Creek Tr 9,Reach-1,3824
     377     504     606     363     724    1444    1034
Boundary for River Rch & Prof#=Trail Creek Tr 9,Reach-1,1
Up Type=0
Dn Type=3
Dn Slope=0.005
Boundary for River Rch & Prof#=Trail Creek Tr 9,Reach-1,2
Up Type=0
Dn Type=3
Dn Slope=0.005
Boundary for River Rch & Prof#=Trail Creek Tr 9,Reach-1,3
Up Type=0
Dn Type=3
Dn Slope=0.005
Boundary for River Rch & Prof#=Trail Creek Tr 9,Reach-1,4
Up Type=0
Dn Type=3
Dn Slope=0.005
Boundary for River Rch & Prof#=Trail Creek Tr 9,Reach-1,5
Up Type=0
Dn Type=3
Dn Slope=0.005
Boundary for River Rch & Prof#=Trail Creek Tr 9,Reach-1,6
Up Type=0
Dn Type=3
Dn Slope=0.005
Boundary for River Rch & Prof#=Trail Creek Tr 9,Reach-1,7
Up Type=0
Dn Type=3
Dn Slope=0.005

--- Trail Creek Tr 9.g01 (geometry) ---

Geom Title=Existing Conditions
Program Version=4.10

River Reach=Trail Creek Tr 9,Reach-1
Reach XY= 30
        2317579.        7080360.      2317676.69      7080264.98
      2317731.29      7080265.06      2317868.21      7080400.34
      2317905.16      7080487.14      2317988.66      7080520.79
      2318109.13       7080640.1      2318134.44      7080704.81
      2318296.23      7080726.24      2318328.02      7080770.26
      2318342.37      7081023.32      2318565.79      7081246.37
      2318712.56      7081343.21      2318734.52      7081462.44
      2318815.67      7081546.61      2318931.43      7081565.52
      2319069.32      7081699.24      2319180.55      7081756.25
      2319458.97      7081759.93       2319539.5      7081711.22
       2319768.5      7081711.22      2319984.94      7081807.74
      2320173.07      7081812.24      2320334.93      7081907.75
      2320473.06      7081912.27      2320530.57      7081956.21
      2320673.07       7081962.3      2320749.21      7082010.36
       2320926.5      7081865.35        2321029.        7081860.

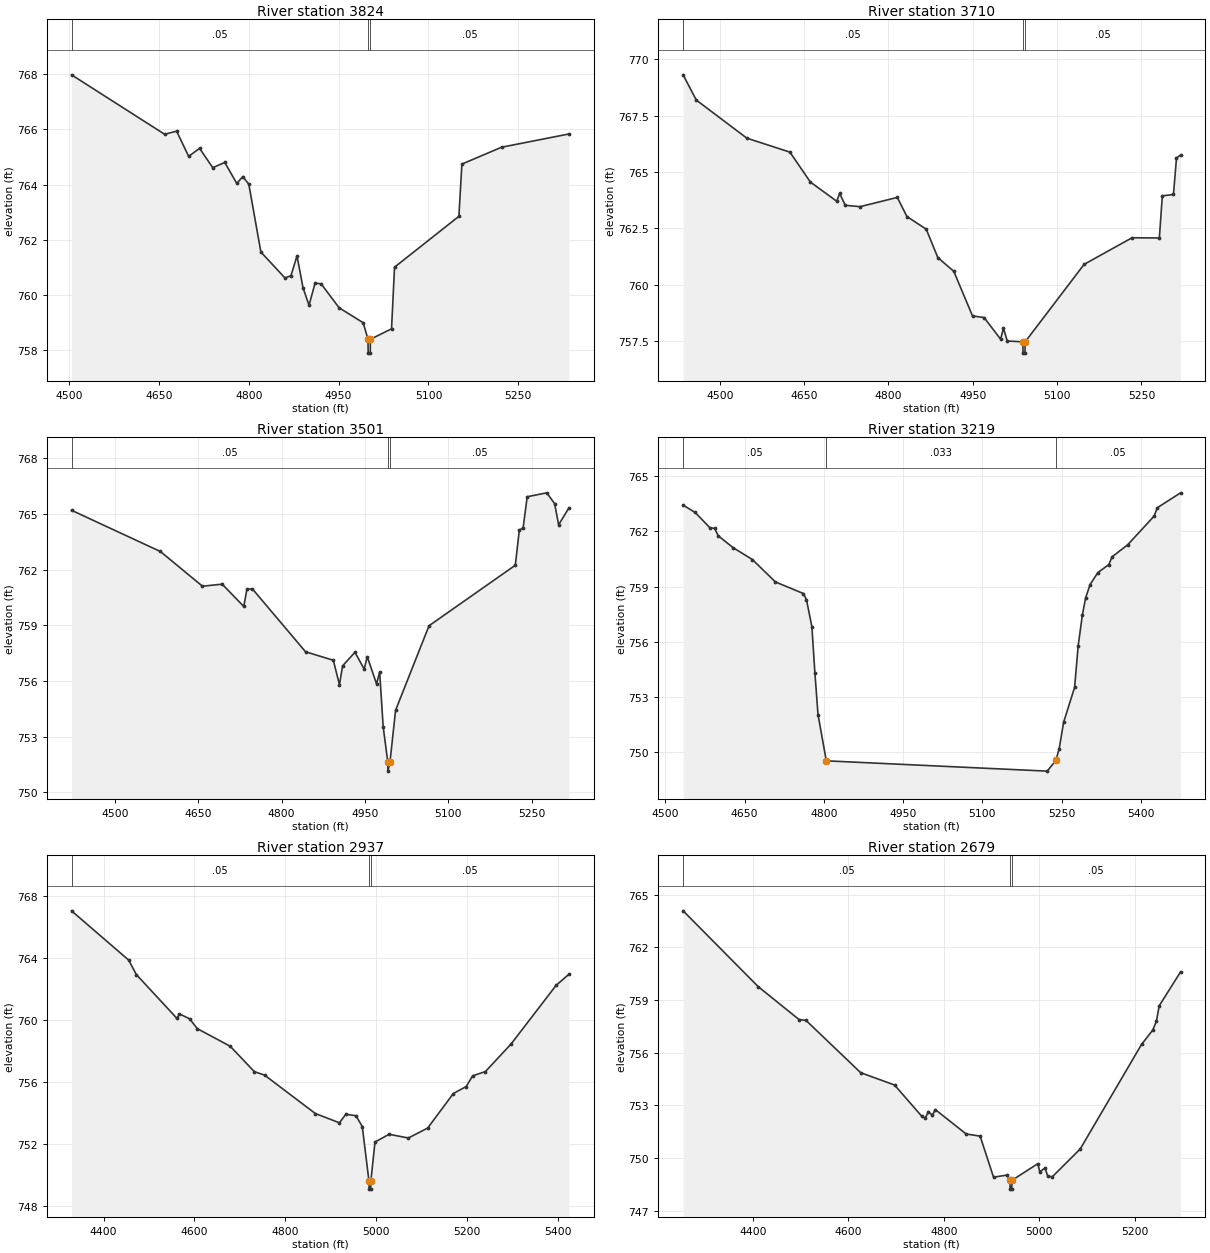
Type RM Length L Ch R = 1 ,3824    ,114,114,114
BEGIN DESCRIPTION:
Trail Creek Tr 9 9.0
END DESCRIPTION:
XS GIS Cut Line= 3
      2317564.39      7080635.45      2318081.05       7080586.5
      2318391.08      7080559.31
#Sta/Elev= 30
  4504.3  767.97  4659.6  765.82  4679.7  765.93  4699.8  765.02    4718  765.31
    4740  764.61  4760.1   764.8  4780.1  764.04  4790.2  764.29  4800.2  764.01
  4820.3  761.56  4860.5  760.62  4870.5   760.7  4880.6  761.42  4890.6  760.27
  4900.7  759.63  4910.7  760.43  4920.8  760.41  4950.9  759.54  4991.1     759
  4999.1   758.4  4999.4   757.9  5002.9   757.9  5003.1   758.4  5038.4  758.78
  5043.4  761.01  5150.8  762.85  5155.8  764.74    5222  765.35  5334.5  765.83
#Mann= 3 ,-1 , 0
  4504.3     .05       0  4999.1    .033       0  5003.1     .05       0
Bank Sta=4999.1,5003.1
XS Rating Curve= 0 ,0
Exp/Cntr=0.3,0.1

Type RM Length L Ch R = 1 ,3710    ,209,209,209
BEGIN DESCRIPTION:
Trail Creek Tr 9 8.0
END DESCRIPTION:
XS GIS Cut Line= 3
      2317578.99        7080810.      2318188.28      7080660.97
      2318429.94       7080572.2
#Sta/Elev= 30
  4434.9  769.31  4458.3  768.19  4548.2   766.5  4624.8  765.88  4661.3  764.55
  4708.1   763.7  4713.3  764.05  4723.2  763.52  4749.7  763.46  4815.8  763.87
    4833  763.02  4867.3  762.46  4887.9   761.2  4916.3  760.59  4949.6  758.61
  4970.2  758.54  4999.5  757.58  5004.7  758.06  5011.4   757.5  5039.2  757.46
  5039.4  756.96  5042.9  756.96  5043.2  757.46  5148.1   760.9  5233.4  762.08
  5281.9  762.07  5287.2  763.94    5307     764  5312.4  765.62  5319.6  765.75
#Mann= 3 ,-1 , 0
  4434.9     .05       0  5039.2    .033       0  5043.2     .05       0
Bank Sta=5039.2,5043.2
XS Rating Curve= 0 ,0
Exp/Cntr=0.3,0.1

Type RM Length L Ch R = 1 ,3501    ,282,282,282
BEGIN DESCRIPTION:
Trail Creek Tr 9 7.0
END DESCRIPTION:
XS GIS Cut Line= 3
      2317788.84       7080996.3        2318351.      7080710.28
      2318533.44      7080517.99
#Sta/Elev= 30
  4421.6  765.19  4581.6  762.97  4657.4   761.1  4692.9  761.21  4731.8  760.01
  4737.4  760.93  4747.2  760.96    4843  757.57  4893.1  757.11  4904.1  755.79
  4909.7  756.81    4932  757.54  4948.6  756.64  4954.2   757.3  4970.9  755.84
  4976.5  756.48  4982.8  753.54  4991.1  751.64  4991.4  751.14  4995.1  751.64
  5005.2  754.42  5065.4  758.97  5220.8  762.23    5228  764.12  5234.9  764.25
  5242.2  765.92  5277.4  766.13  5291.6  765.55  5298.8  764.41  5317.4  765.32
#Mann= 3 ,-1 , 0
  4421.6     .05       0  4991.1    .033       0  4995.1     .05       0
Bank Sta=4991.1,4995.1
XS Rating Curve= 0 ,0
Exp/Cntr=0.3,0.1

Type RM Length L Ch R = 1 ,3219    ,282,282,282
BEGIN DESCRIPTION:
Trail Creek Tr 9 6.0
END DESCRIPTION:
XS GIS Cut Line= 3
      2317926.91      7081237.92        2318329.        7081010.
      2318714.95      7080725.78
#Sta/Elev= 30
  4533.8  763.43  4556.7  763.03  4584.1  762.21  4593.7  762.16    4600  761.77
  4628.2  761.12  4664.9  760.47  4708.6  759.25  4761.6  758.62  4767.3  758.28
  4777.5  756.82  4783.2  754.31  4789.1  752.04  4804.8  749.52  5222.9  748.96
  5239.3  749.54  5245.5  750.17    5254  751.62  5274.8  753.52  5281.6  755.79
  5289.5  757.46  5295.7  758.39  5304.1  759.11  5318.8  759.76  5339.6   760.2
  5345.8  760.62  5375.1  761.27  5425.2  762.83  5431.4  763.29  5475.3   764.1
#Mann= 3 ,-1 , 0
  4533.8     .05       0  4804.8    .033       0  5239.3     .05       0
Bank Sta=4804.8,5239.3
XS Rating Curve= 0 ,0
Exp/Cntr=0.3,0.1

Type RM Length L Ch R = 1 ,2937    ,258,258,258
BEGIN DESCRIPTION:
Trail Creek Tr 9 5.0
END DESCRIPTION:
XS GIS Cut Line= 3
      2317928.97      7081510.01        2318529.        7081210.
      2318828.99      7080910.01
#Sta/Elev= 30
  4329.4  767.06  4455.2  763.88    4472  762.95  4561.4  760.12    4567  760.41
  4589.4  760.09  4606.1  759.46  4678.8  758.32  4731.9  756.68  4754.3  756.46
  4866.1  753.98  4919.2  753.38  4933.2  753.93  4955.5  753.84  4969.5  753.14
  4984.3   749.6  4984.5   749.1    4988   749.1  4988.3   749.6  4997.5  752.14
  5028.5  752.64    5071   752.4  5113.4  753.04    5170  755.27  5198.2  755.72
  5212.4  756.41  5240.7  756.69  5297.2  758.47  5396.2  762.25  5424.5  762.97
#Mann= 3 ,-1 , 0
  4329.4     .05       0  4984.3    .033       0  4988.3     .05       0
Bank Sta=4984.3,4988.3
XS Rating Curve= 0 ,0
Exp/Cntr=0.3,0.1

Type RM Length L Ch R = 1 ,2679    ,192,192,192
BEGIN DESCRIPTION:
Trail Creek Tr 9 4.0
END DESCRIPTION:
XS GIS Cut Line= 3
      2318128.99        7081810.        2318729.        7081360.
      2318879.02      7081109.96
#Sta/Elev= 30
  4254.1  764.08  4411.4  759.76  4496.8  757.89  4511.4  757.84    4626  754.86
  4696.8  754.16  4754.1  752.37  4761.4  752.28  4767.6  752.65    4776  752.44
  4782.2  752.76  4846.8  751.37    4876  751.25  4904.1  748.91  4932.2  749.03
  4938.6  748.73  4938.8  748.23  4942.3  748.23  4942.6  748.73  4996.8  749.68
    5001  749.21  5011.9  749.44  5017.7  748.96  5027.4  748.94  5085.7  750.52
    5214  756.47  5237.3  757.28  5245.1  757.78    5251  758.67  5295.7   760.6
#Mann= 3 ,-1 , 0
  4254.1     .05       0  4938.6    .033       0  4942.6     .05       0
Bank Sta=4938.6,4942.6
XS Rating Curve= 0 ,0
Exp/Cntr=0.3,0.1

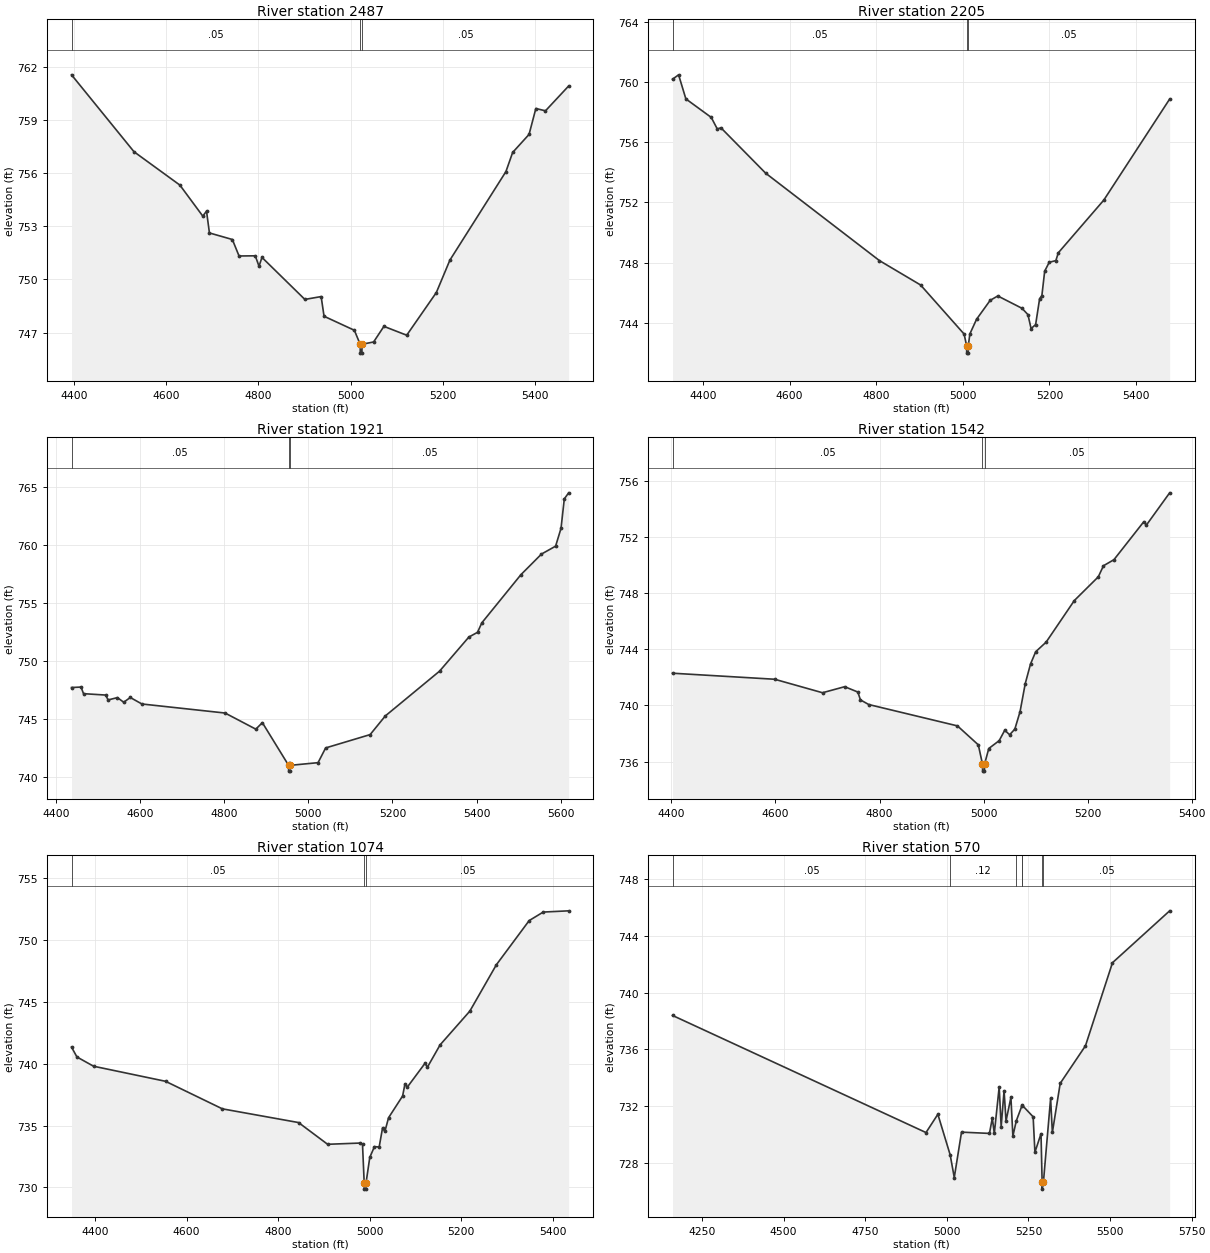
Type RM Length L Ch R = 1 ,2487    ,282,282,282
BEGIN DESCRIPTION:
Trail Creek Tr 9 3.0
END DESCRIPTION:
XS GIS Cut Line= 3
      2318328.99      7081910.01      2318775.07      7081558.42
      2319074.64      7081145.89
#Sta/Elev= 30
  4395.1  761.54  4530.6   757.2    4630  755.32  4679.7  753.57  4687.8  753.85
  4694.1  752.62  4743.8  752.25  4758.3  751.32  4793.5  751.33  4801.6  750.74
    4808  751.24    4901  748.87  4936.3  749.03  4942.6  747.92  5008.3  747.13
  5020.9  746.34  5021.2  745.84  5024.7  745.84  5024.9  746.34  5050.1  746.47
  5072.4  747.35  5121.8  746.85  5186.1  749.26  5215.5  751.09  5336.9  756.08
  5351.5  757.16  5387.1  758.18  5401.8  759.64  5422.7  759.51  5472.9  760.91
#Mann= 3 ,-1 , 0
  4395.1     .05       0  5020.9    .033       0  5024.9     .05       0
Bank Sta=5020.9,5024.9
XS Rating Curve= 0 ,0
Exp/Cntr=0.3,0.1

Type RM Length L Ch R = 1 ,2205    ,284,284,284
BEGIN DESCRIPTION:
Trail Creek Tr 9 2.0
END DESCRIPTION:
XS GIS Cut Line= 3
      2318428.99        7081960.        2319029.        7081660.
      2319173.98      7081204.97
#Sta/Elev= 30
  4329.4  760.19  4343.4  760.48  4360.2  758.88  4418.8  757.65  4432.8  756.88
  4441.2  756.96  4544.6  753.94  4807.4  748.13  4902.4  746.51  5002.9  743.25
  5008.7  742.48    5009  741.98  5012.5  741.98  5012.7  742.48  5016.3  743.26
  5031.7  744.23  5063.2  745.49  5080.8  745.78  5136.7  744.96  5150.4  744.54
  5157.7  743.61  5168.2  743.88  5177.4   745.6  5182.6   745.8  5189.1  747.43
  5199.6  748.02  5214.9  748.13  5220.6  748.65  5325.6  752.15  5477.8  758.87
#Mann= 3 ,-1 , 0
  4329.4     .05       0  5008.7    .033       0  5012.7     .05       0
Bank Sta=5008.7,5012.7
XS Rating Curve= 0 ,0
Exp/Cntr=0.3,0.1

Type RM Length L Ch R = 1 ,1921    ,379,379,379
BEGIN DESCRIPTION:
Trail Creek Tr 9 1.0
END DESCRIPTION:
XS GIS Cut Line= 3
      2318992.05       7082243.8        2319279.        7081760.
      2319429.01      7081159.97
#Sta/Elev= 30
  4437.6   747.7  4460.2  747.74  4466.1  747.17  4518.7  747.05  4524.5  746.63
  4546.7  746.83  4561.6  746.43  4577.2  746.84  4604.8  746.28  4802.4   745.5
  4875.4  744.11    4891  744.67  4953.3  740.99  4953.5  740.49    4957  740.49
  4957.3  740.99  5023.3  741.22  5041.3  742.49    5147  743.64  5183.1  745.25
  5311.9  749.11  5381.5  752.05  5402.1  752.46  5412.4  753.28  5505.2  757.43
  5554.1  759.21  5587.6  759.89  5600.5  761.43  5608.3  763.97  5618.6  764.49
#Mann= 3 ,-1 , 0
  4437.6     .05       0  4953.3    .033       0  4957.3     .05       0
Bank Sta=4953.3,4957.3
XS Rating Curve= 0 ,0
Exp/Cntr=0.3,0.1

Type RM Length L Ch R = 1 ,1542    ,468,468,468
BEGIN DESCRIPTION:
Trail Creek Tr 9 0.8
END DESCRIPTION:
XS GIS Cut Line= 3
      2319391.43       7082219.2      2319623.21      7081957.83
      2319667.45      7081353.18
#Sta/Elev= 30
  4402.1  742.29  4598.4  741.86  4690.4   740.9    4733  741.33  4758.3  740.95
  4763.3  740.39  4779.3  740.06  4949.8  738.54  4989.9  737.19  4997.9  735.82
  4998.2  735.32  5001.7  735.32  5001.9  735.82    5010  736.93    5030  737.49
  5040.7  738.23  5050.1  737.91  5060.1  738.31  5070.1  739.55  5080.1  741.55
  5090.2  742.94  5100.2  743.82  5120.2   744.5  5174.4  747.46  5220.5  749.15
  5230.5  749.94  5250.6  750.37  5308.1  753.08  5313.1  752.84  5357.7  755.13
#Mann= 3 ,-1 , 0
  4402.1     .05       0  4997.9     .04       0  5001.9     .05       0
Bank Sta=4997.9,5001.9
XS Rating Curve= 0 ,0
Exp/Cntr=0.3,0.1

Type RM Length L Ch R = 1 ,1074    ,504,504,504
BEGIN DESCRIPTION:
Trail Creek Tr 9 0.6
END DESCRIPTION:
XS GIS Cut Line= 3
       2319618.3      7082224.09      2320047.27      7081947.97
      2320170.56      7081385.79
#Sta/Elev= 30
  4348.6  741.35  4360.4  740.55  4396.7   739.8  4553.9  738.58    4678  736.35
  4844.4  735.24  4907.9  733.48    4979  733.58  4984.1  733.49  4987.8  730.35
    4988  729.85  4991.5  729.85  4991.8  730.35    5000  732.42  5010.2  733.29
  5020.5  733.26  5027.9  734.81    5033  734.52    5041  735.63  5071.7  737.39
  5076.8  738.36    5082  738.11  5120.7  740.04  5125.8  739.72  5153.6  741.53
  5218.5  744.26  5276.4  748.01  5348.1  751.59  5378.8  752.28  5434.3  752.38
#Mann= 3 ,-1 , 0
  4348.6     .05       0  4987.8    .033       0  4991.8     .05       0
Bank Sta=4987.8,4991.8
XS Rating Curve= 0 ,0
Exp/Cntr=0.3,0.1

Type RM Length L Ch R = 1 ,570     ,0,0,0
BEGIN DESCRIPTION:
Trail Creek Tr 9 0.3
END DESCRIPTION:
XS GIS Cut Line= 4
      2319795.82      7082179.72      2320402.31      7082150.14
      2320653.79      7081780.31      2320476.26      7081346.36
#Sta/Elev= 30
  4159.5   738.4  4936.2  730.14  4972.5  731.43  5010.2  728.57  5022.8  726.97
    5045  730.17  5130.6  730.08  5139.4  731.16  5145.5  730.08  5160.4  733.35
  5166.5  730.56  5175.4  733.09  5181.4  730.96  5196.4  732.62  5202.4  729.89
  5212.9  730.97  5230.1  732.03  5230.9  732.07  5264.5  731.25  5269.9  728.75
  5288.6  730.06    5292  726.65  5292.2  726.15    5296  726.65    5318  732.55
  5323.4  730.15  5347.4  733.61  5424.8  736.26  5507.6  742.12  5682.8  745.78
#Mann= 7 ,-1 , 0
  4159.5     .05       0  5010.2     .12       0  5212.9     .05       0
  5230.1     .12       0  5230.9     .05       0    5292    .033       0
    5296     .05       0
Bank Sta=5292,5296
XS Rating Curve= 0 ,0
Exp/Cntr=0.3,0.1

Chan Stop Cuts=-1
Use User Specified Reach Order=0
Composite Channel Slope=5