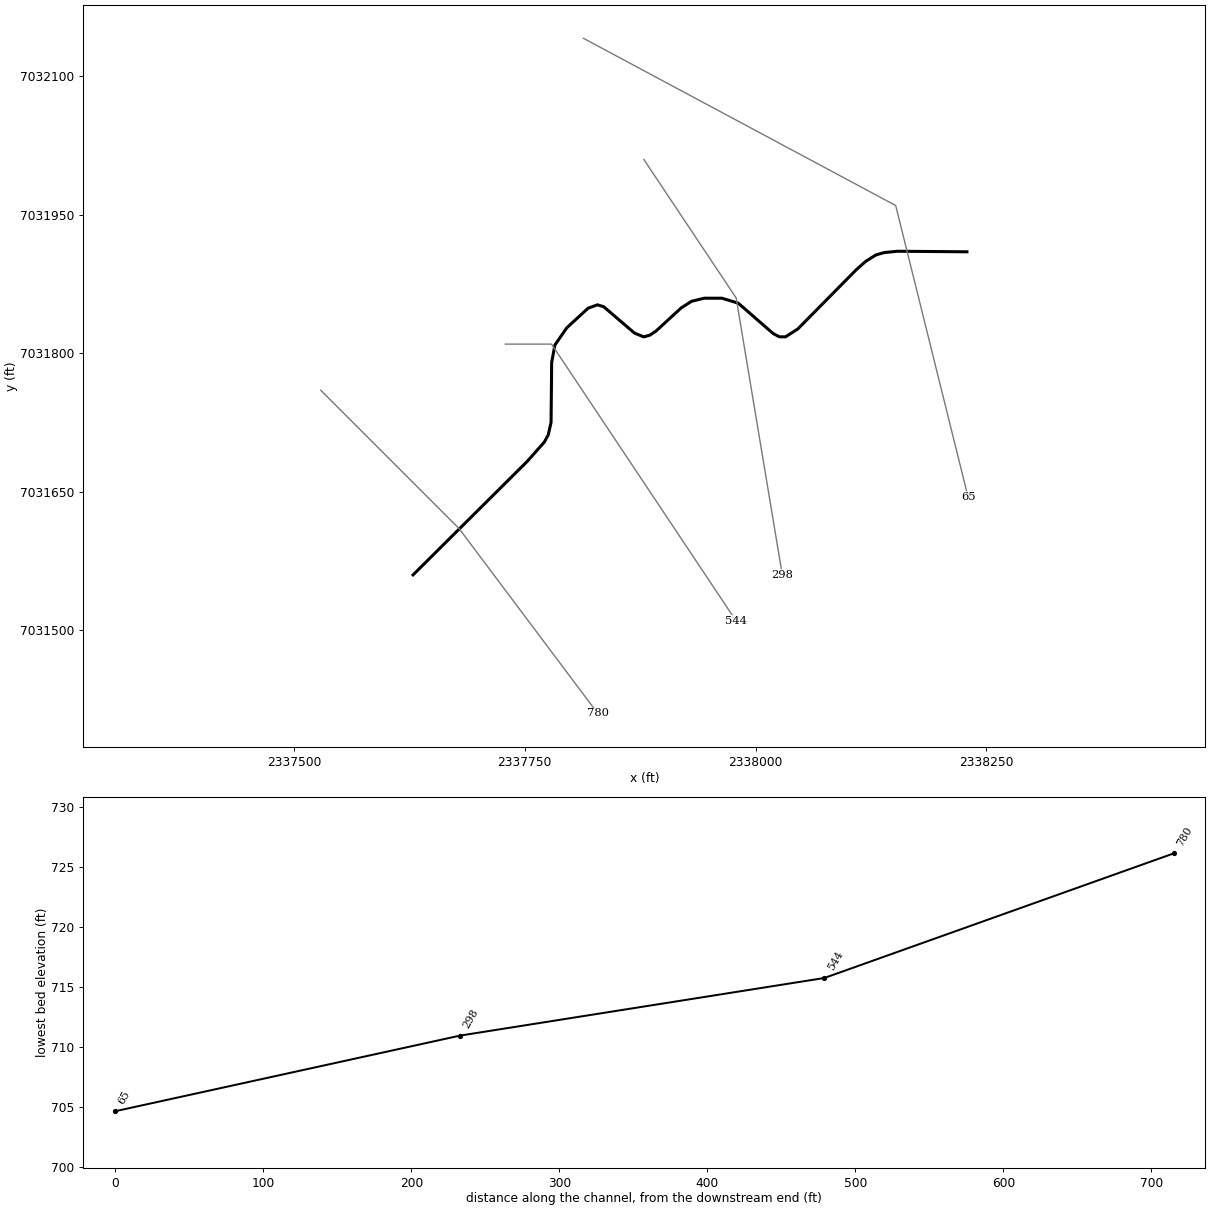
--- Tributary 3 to Powel Creek.prj (project) ---

Proj Title=Tributary 3 to Powel Creek Base Level Engineering
Current Plan=p01
Default Exp/Contr=0.3,0.1
English Units
Geom File=g01
Flow File=f01
Plan File=p01
BEGIN DESCRIPTION:
Tributary 3 to Powel Creek
END DESCRIPTION:

--- Tributary 3 to Powel Creek.p01 (plan) ---

Plan Title=Multiple Run
Short Identifier=Multiple
Geom File=g01
Flow File=f01
Subcritical Flow
K Sum by GR= 0
Std Step Tol= 0.01
Critical Tol= 0.01
Num of Std Step Trials= 20
Max Error Tol= 0.3
Flow Tol Ratio= 0.001
Split Flow NTrial= 30
Split Flow Tol= 0.02
Split Flow Ratio= 0.02
Log Output Level= 0
Friction Slope Method= 1
Unsteady Friction Slope Method= 2
Unsteady Bridges Friction Slope Method= 1
Parabolic Critical Depth
Global Vel Dist=  1 , 1 , 1
Global Log Level= 0
CheckData=True
Encroach Param= -1, 0, 0, 0
BEGIN DESCRIPTION:
Multiple Run
END DESCRIPTION:

--- Tributary 3 to Powel Creek.f01 (steady flow) ---

Flow Title=Multiple
Number of Profiles=7
Profile Names=10-year,25-year,50-year,1pct_min,100-year,1pct_plu,500-year
River Rch & RM= Tributary 3 to P,Reach-1,780
      98     117     131      74     147     294     183
Boundary for River Rch & Prof#=Tributary 3 to P,Reach-1,1
Up Type=0
Dn Type=3
Dn Slope=0.005
Boundary for River Rch & Prof#=Tributary 3 to P,Reach-1,2
Up Type=0
Dn Type=3
Dn Slope=0.005
Boundary for River Rch & Prof#=Tributary 3 to P,Reach-1,3
Up Type=0
Dn Type=3
Dn Slope=0.005
Boundary for River Rch & Prof#=Tributary 3 to P,Reach-1,4
Up Type=0
Dn Type=3
Dn Slope=0.005
Boundary for River Rch & Prof#=Tributary 3 to P,Reach-1,5
Up Type=0
Dn Type=3
Dn Slope=0.005
Boundary for River Rch & Prof#=Tributary 3 to P,Reach-1,6
Up Type=0
Dn Type=3
Dn Slope=0.005
Boundary for River Rch & Prof#=Tributary 3 to P,Reach-1,7
Up Type=0
Dn Type=3
Dn Slope=0.005

--- Tributary 3 to Powel Creek.g01 (geometry) ---

Geom Title=Existing Conditions

River Reach=Tributary 3 to P,Reach-1
Reach XY= 30
      2337629.00      7031560.00      2337752.83      7031683.13
      2337771.14      7031703.83      2337775.39      7031711.50
      2337778.48      7031725.23      2337779.13      7031790.17
      2337782.61      7031808.97      2337795.46      7031827.61
      2337818.63      7031848.92      2337828.75      7031852.55
      2337835.49      7031850.48      2337868.92      7031821.88
      2337878.90      7031817.84      2337885.54      7031819.68
      2337892.18      7031824.14      2337919.32      7031849.09
      2337930.65      7031856.37      2337944.36      7031859.72
      2337963.64      7031859.71      2337981.29      7031854.31
      2338019.13      7031821.39      2338025.77      7031817.92
      2338032.40      7031817.83      2338045.69      7031826.33
      2338108.84      7031890.29      2338119.18      7031899.52
      2338130.40      7031906.59      2338139.34      7031909.17
      2338153.75      7031910.59      2338229.00      7031910.00

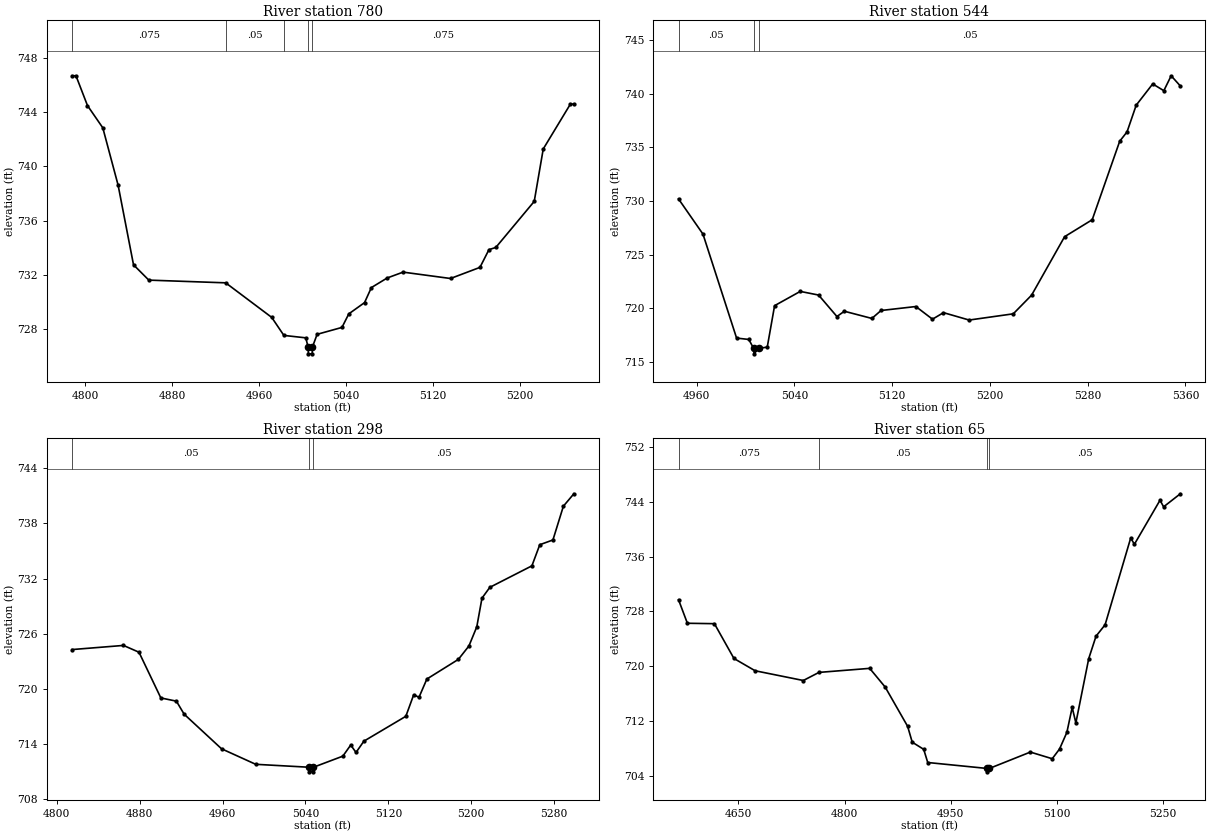
Type RM Length L Ch R = 1,780,236,236,236
BEGIN DESCRIPTION:
Tributary 3 to Powel Creek 3.0
END DESCRIPTION:
XS GIS Cut Line= 3
      2337528.99      7031760.01      2337679.00      7031610.00
      2337829.03      7031409.96
#Sta/Elev= 30
  4787.8  746.68  4791.4  746.68  4802.0  744.48  4816.1  742.84  4830.2  738.61
  4844.4  732.73  4858.5  731.60  4929.3  731.40  4971.7  728.85  4982.9  727.52
  5003.1  727.34  5005.2  726.66  5005.5  726.16  5009.0  726.16  5009.2  726.66
  5013.5  727.60  5036.4  728.11  5042.7  729.11  5057.2  729.94  5063.5  731.05
  5078.1  731.76  5092.7  732.19  5136.4  731.72  5163.5  732.54  5171.8  733.85
  5178.1  734.01  5213.5  737.41  5221.8  741.28  5246.8  744.59  5250.0  744.59
#Mann=5,-1,0
  4787.8   0.075       0  4929.3    0.05       0  4982.9   0.075       0
  5005.2    0.07       0  5009.2   0.075       0
Bank Sta=5005.2,5009.2
Exp/Cntr=0.3,0.1

Type RM Length L Ch R = 1,544,246,246,246
BEGIN DESCRIPTION:
Tributary 3 to Powel Creek 2.0
END DESCRIPTION:
XS GIS Cut Line= 3
      2337728.98      7031810.00      2337779.00      7031810.00
      2337979.01      7031509.98
#Sta/Elev= 30
  4945.2  730.19  4965.2  726.91  4992.7  717.22  5002.7  717.09  5006.7  716.25
  5007.0  715.75  5010.7  716.25  5017.8  716.38  5023.8  720.24  5044.8  721.57
  5059.8  721.23  5074.8  719.23  5080.9  719.72  5103.4  719.05  5110.9  719.79
  5139.4  720.16  5153.0  718.98  5162.0  719.59  5183.0  718.90  5219.1  719.48
  5234.1  721.22  5261.1  726.67  5283.7  728.25  5306.2  735.57  5312.2  736.44
  5319.7  738.93  5333.2  740.91  5342.3  740.28  5348.3  741.67  5355.8  740.72
#Mann=3,-1,0
  4945.2    0.05       0  5006.7    0.05       0  5010.7    0.05       0
Bank Sta=5006.7,5010.7
Exp/Cntr=0.3,0.1

Type RM Length L Ch R = 1,298,233,233,233
BEGIN DESCRIPTION:
Tributary 3 to Powel Creek 1.0
END DESCRIPTION:
XS GIS Cut Line= 3
      2337878.98      7032010.02      2337979.00      7031860.00
      2338028.99      7031560.04
#Sta/Elev= 30
  4814.7  724.26  4864.3  724.71  4879.3  723.97  4900.4  718.99  4915.4  718.64
  4922.9  717.22  4959.0  713.45  4992.0  711.76  5043.7  711.44  5043.9  710.94
  5047.4  710.94  5047.7  711.44  5076.1  712.65  5083.7  713.86  5088.8  713.05
  5096.4  714.28  5136.9  716.99  5144.5  719.34  5149.6  719.06  5157.2  721.05
  5187.6  723.19  5197.8  724.65  5205.4  726.74  5210.4  729.86  5218.0  731.04
  5258.6  733.38  5266.2  735.68  5278.9  736.20  5289.0  739.88  5299.1  741.23
#Mann=3,-1,0
  4814.7    0.05       0  5043.7   0.033       0  5047.7    0.05       0
Bank Sta=5043.7,5047.7
Exp/Cntr=0.3,0.1

Type RM Length L Ch R = 1,65,0,0,0
BEGIN DESCRIPTION:
Stream HEN-5 26.5
END DESCRIPTION:
XS GIS Cut Line= 3
      2337813.61      7032141.24      2338151.84      7031960.12
      2338230.23      7031644.37
#Sta/Elev= 30
  4565.5  729.70  4578.0  726.27  4616.2  726.21  4643.8  721.14  4673.7  719.35
  4741.8  717.93  4763.9  719.11  4835.6  719.70  4857.5  716.97  4889.2  711.25
  4895.7  708.94  4911.9  707.90  4917.6  705.98  5000.8  705.12  5001.1  704.62
  5004.8  705.12  5062.6  707.50  5093.5  706.53  5103.8  707.94  5114.2  710.37
  5121.7  714.01  5126.9  711.75  5145.1  721.13  5155.4  724.39  5168.2  726.05
  5204.4  738.70  5209.6  737.78  5245.8  744.20  5250.9  743.24  5274.5  745.14
#Mann=4,-1,0
  4565.5   0.075       0  4763.9    0.05       0  5000.8    0.05       0
  5004.8    0.05       0
Bank Sta=5000.8,5004.8
Exp/Cntr=0.3,0.1

Chan Stop Cuts=-1