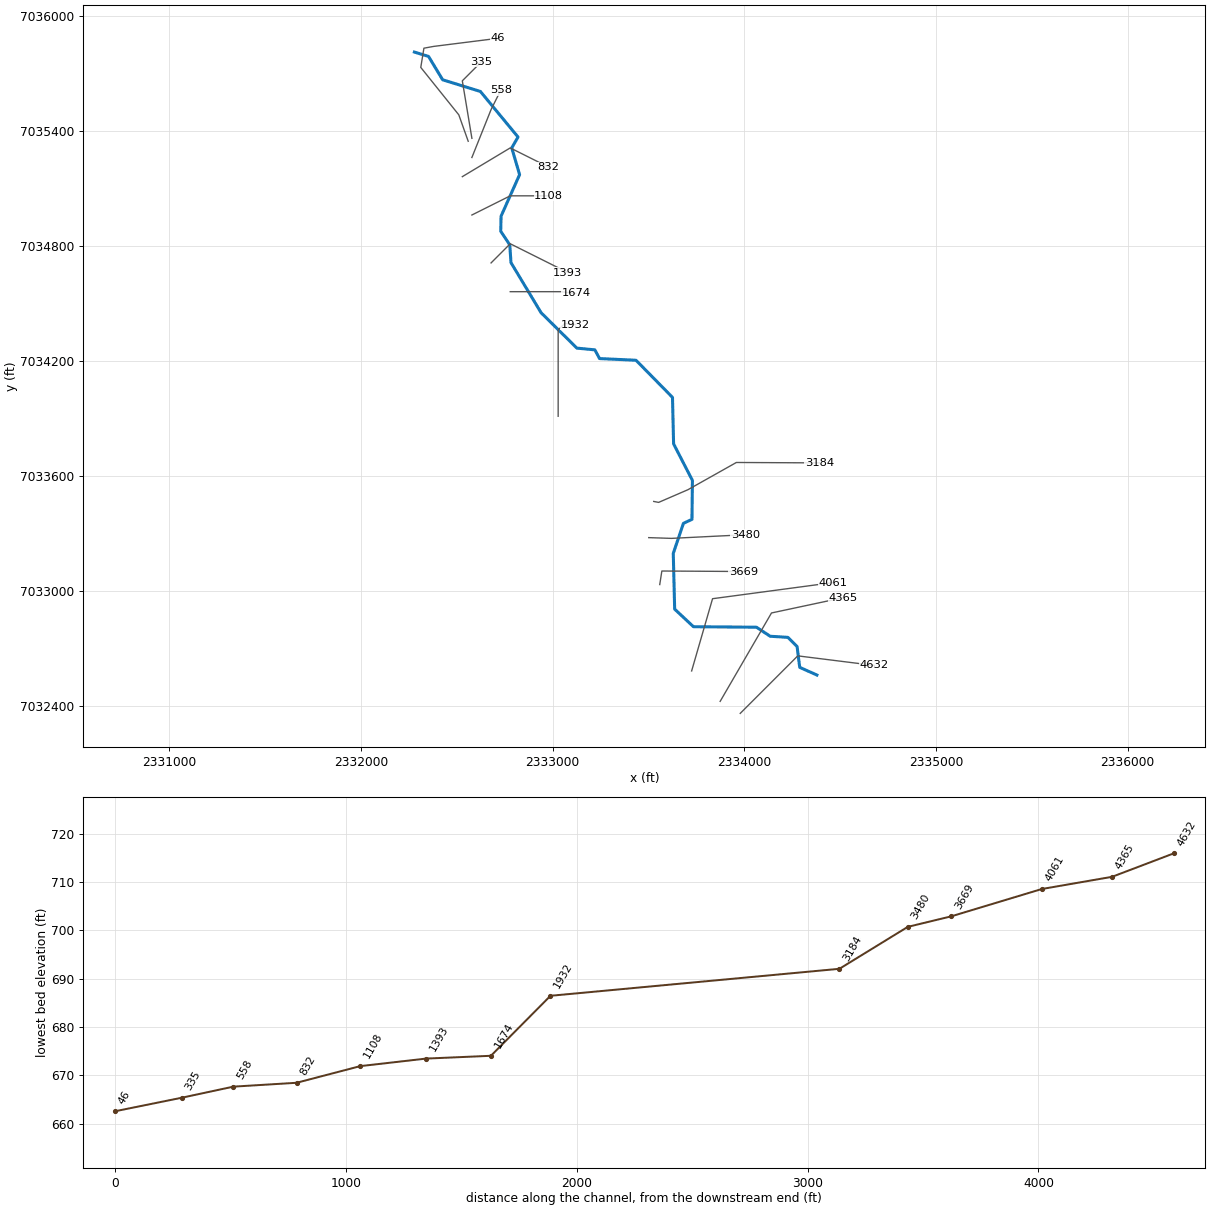
--- Tributary BC-1A to Buffalo Creek.prj (project) ---

Proj Title=Tributary BC-1A to Buffalo Creek Base Level Engineering
Current Plan=p01
Default Exp/Contr=0.3,0.1
English Units
Geom File=g01
Flow File=f01
Plan File=p01
BEGIN DESCRIPTION:
Tributary BC-1A to Buffalo Creek
END DESCRIPTION:

--- Tributary BC-1A to Buffalo Creek.p01 (plan) ---

Plan Title=Multiple Run
Short Identifier=Multiple
Geom File=g01
Flow File=f01
Subcritical Flow
K Sum by GR= 0
Std Step Tol= 0.01
Critical Tol= 0.01
Num of Std Step Trials= 20
Max Error Tol= 0.3
Flow Tol Ratio= 0.001
Split Flow NTrial= 30
Split Flow Tol= 0.02
Split Flow Ratio= 0.02
Log Output Level= 0
Friction Slope Method= 1
Unsteady Friction Slope Method= 2
Unsteady Bridges Friction Slope Method= 1
Parabolic Critical Depth
Global Vel Dist=  1 , 1 , 1
Global Log Level= 0
CheckData=True
Encroach Param= -1, 0, 0, 0
BEGIN DESCRIPTION:
Multiple Run
END DESCRIPTION:

--- Tributary BC-1A to Buffalo Creek.f01 (steady flow) ---

Flow Title=Multiple
Number of Profiles=7
Profile Names=10-year,25-year,50-year,1pct_min,100-year,1pct_plu,500-year
River Rch & RM= Tributary BC-1A ,Reach-1,4632
     346     457     546     325     648    1290     909
Boundary for River Rch & Prof#=Tributary BC-1A ,Reach-1,1
Up Type=0
Dn Type=3
Dn Slope=0.005
Boundary for River Rch & Prof#=Tributary BC-1A ,Reach-1,2
Up Type=0
Dn Type=3
Dn Slope=0.005
Boundary for River Rch & Prof#=Tributary BC-1A ,Reach-1,3
Up Type=0
Dn Type=3
Dn Slope=0.005
Boundary for River Rch & Prof#=Tributary BC-1A ,Reach-1,4
Up Type=0
Dn Type=3
Dn Slope=0.005
Boundary for River Rch & Prof#=Tributary BC-1A ,Reach-1,5
Up Type=0
Dn Type=3
Dn Slope=0.005
Boundary for River Rch & Prof#=Tributary BC-1A ,Reach-1,6
Up Type=0
Dn Type=3
Dn Slope=0.005
Boundary for River Rch & Prof#=Tributary BC-1A ,Reach-1,7
Up Type=0
Dn Type=3
Dn Slope=0.005

--- Tributary BC-1A to Buffalo Creek.g01 (geometry) ---

Geom Title=Existing Conditions

River Reach=Tributary BC-1A ,Reach-1
Reach XY= 30
      2334379.00      7032560.00      2334289.27      7032599.91
      2334275.49      7032708.75      2334227.75      7032756.49
      2334134.98      7032762.36      2334063.78      7032809.48
      2333734.84      7032812.05      2333636.80      7032903.79
      2333629.52      7033194.79      2333682.56      7033351.50
      2333727.04      7033371.97      2333729.44      7033575.18
      2333631.24      7033765.93      2333625.46      7034008.54
      2333435.19      7034202.19      2333244.96      7034210.95
      2333220.50      7034256.44      2333126.63      7034265.54
      2332939.78      7034450.32      2332782.82      7034711.58
      2332776.64      7034804.03      2332729.38      7034875.27
      2332731.17      7034954.03      2332827.89      7035170.55
      2332786.81      7035310.10      2332819.70      7035366.67
      2332623.39      7035604.41      2332426.33      7035665.42
      2332352.98      7035787.17      2332279.00      7035810.00

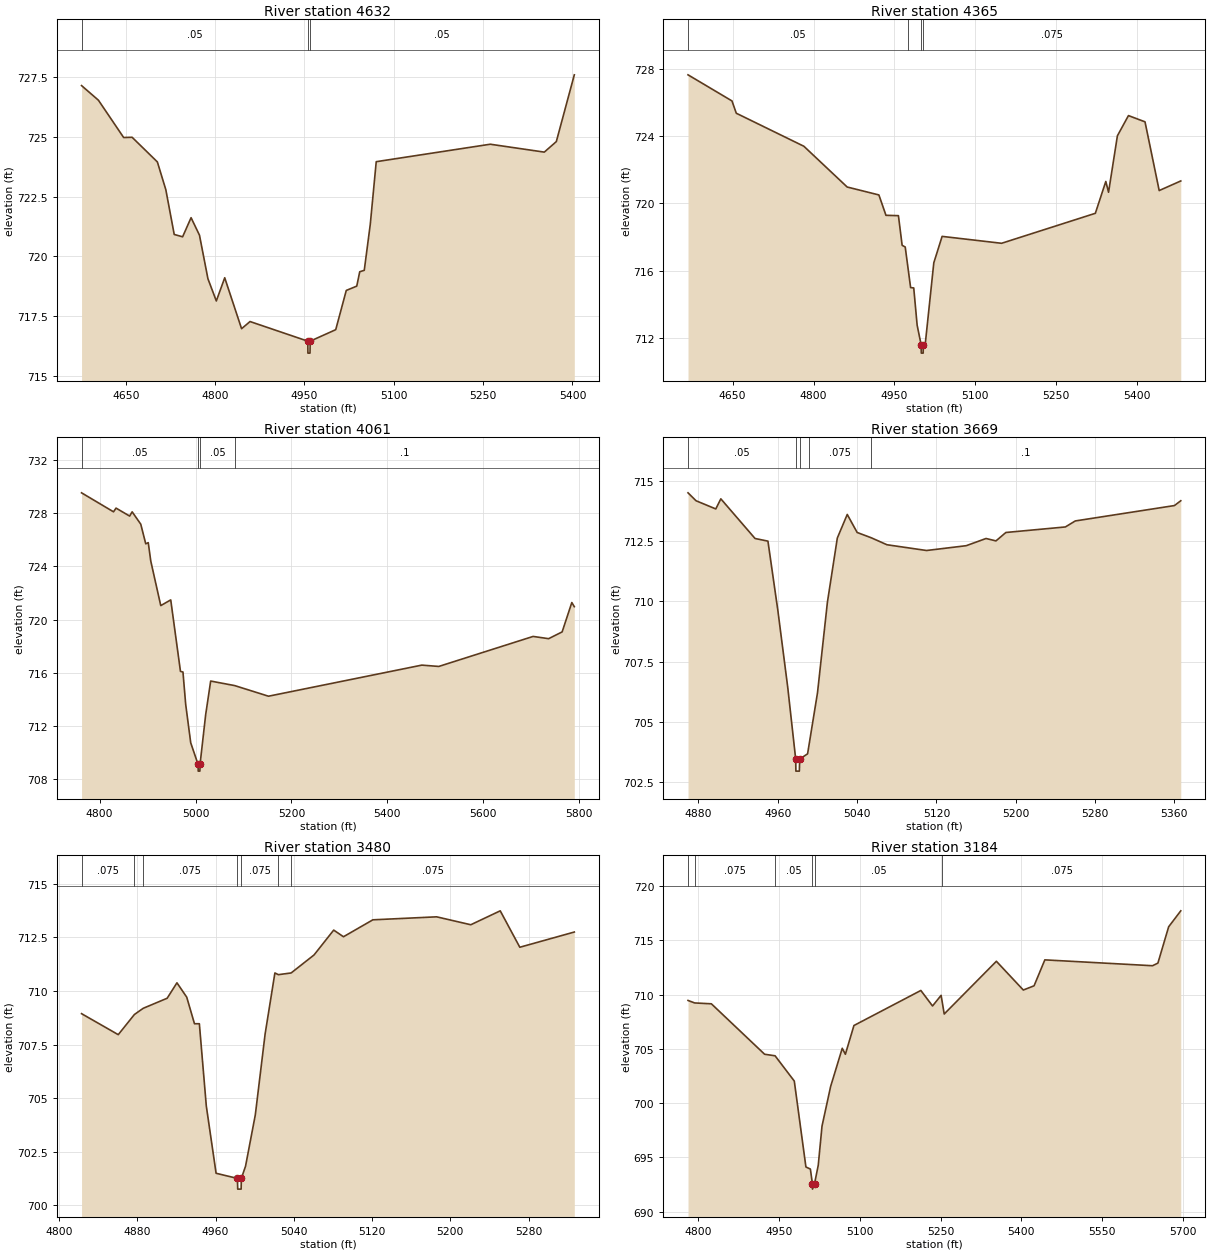
Type RM Length L Ch R = 1,4632,267,267,267
BEGIN DESCRIPTION:
Tributary BC-1A to Buffalo Creek 11.0
END DESCRIPTION:
XS GIS Cut Line= 3
      2333978.98      7032359.98      2334279.00      7032660.00
      2334678.99      7032610.00
#Sta/Elev= 30
  4575.7  727.14  4604.0  726.53  4646.4  724.97  4660.6  724.98  4703.0  723.95
  4717.2  722.79  4731.3  720.92  4745.4  720.82  4759.6  721.62  4773.7  720.89
  4787.9  719.07  4802.0  718.14  4816.1  719.11  4844.4  716.98  4858.6  717.28
  4955.6  716.46  4955.8  715.96  4959.3  715.96  4959.6  716.46  5002.5  716.94
  5020.2  718.58  5037.8  718.76  5042.8  719.36  5050.4  719.42  5060.5  721.34
  5070.5  723.96  5262.0  724.69  5352.7  724.36  5372.9  724.80  5403.1  727.59
#Mann=3,-1,0
  4575.7    0.05       0  4955.6   0.033       0  4959.6    0.05       0
Bank Sta=4955.6,4959.6
Exp/Cntr=0.3,0.1

Type RM Length L Ch R = 1,4365,304,304,304
BEGIN DESCRIPTION:
Trib BCA1 Buf 11.5
END DESCRIPTION:
XS GIS Cut Line= 3
      2333874.15      7032422.63      2334141.94      7032883.82
      2334513.87      7032963.17
#Sta/Elev= 30
  4567.3  727.63  4648.8  726.08  4656.8  725.35  4782.1  723.39  4862.4  720.97
  4921.2  720.50  4934.3  719.29  4957.4  719.27  4964.3  717.51  4970.0  717.41
  4974.4  716.35  4980.0  715.00  4985.8  714.98  4992.1  712.77  4999.5  711.61
  4999.8  711.11  5003.3  711.11  5003.5  711.61  5007.3  711.70  5023.0  716.47
  5038.4  718.04  5148.7  717.63  5322.5  719.41  5341.9  721.30  5347.0  720.66
  5363.4  724.01  5383.9  725.21  5414.6  724.84  5440.9  720.76  5480.9  721.33
#Mann=4,-1,0
  4567.3    0.05       0  4974.4   0.075       0  4999.5    0.07       0
  5003.5   0.075       0
Bank Sta=4999.5,5003.5
Exp/Cntr=0.3,0.1

Type RM Length L Ch R = 1,4061,392,392,392
BEGIN DESCRIPTION:
Trib BCA1 Buf 10.5
END DESCRIPTION:
XS GIS Cut Line= 3
      2333725.35      7032581.32      2333834.45      7032958.21
      2334464.17      7033042.51
#Sta/Elev= 30
  4762.3  729.54  4829.0  728.11  4834.2  728.39  4862.6  727.79  4867.8  728.11
  4885.8  727.18  4896.2  725.70  4901.4  725.79  4906.7  724.40  4927.5  721.05
  4948.3  721.48  4968.6  716.10  4973.8  716.05  4979.5  713.61  4990.0  710.72
  5005.4  709.09  5005.6  708.59  5009.1  708.59  5009.4  709.09  5021.2  712.85
  5031.6  715.37  5081.6  715.03  5152.2  714.23  5472.0  716.57  5507.3  716.47
  5704.1  718.73  5736.4  718.56  5764.6  719.07  5784.8  721.28  5790.0  720.97
#Mann=4,-1,0
  4762.3    0.05       0  5005.4    0.05       0  5009.4    0.05       0
  5081.6     0.1       0
Bank Sta=5005.4,5009.4
Exp/Cntr=0.3,0.1

Type RM Length L Ch R = 1,3669,189,189,189
BEGIN DESCRIPTION:
Tributary BC-1A to Buffalo Creek 10.0
END DESCRIPTION:
XS GIS Cut Line= 3
      2333558.96      7033032.00      2333569.95      7033102.68
      2333995.42      7033100.07
#Sta/Elev= 30
  4869.5  714.52  4877.6  714.19  4897.5  713.85  4902.6  714.27  4937.1  712.62
  4950.1  712.51  4960.1  709.63  4970.1  706.42  4978.1  703.44  4978.3  702.94
  4981.8  702.94  4982.1  703.44  4990.1  703.66  4991.4  703.99  5000.1  706.20
  5010.1  709.97  5020.1  712.64  5030.1  713.62  5040.1  712.87  5054.3  712.65
  5070.1  712.36  5110.1  712.12  5150.1  712.32  5170.1  712.62  5180.1  712.52
  5190.1  712.87  5250.1  713.10  5260.1  713.35  5360.1  713.99  5366.5  714.19
#Mann=5,-1,0
  4869.5    0.05       0  4978.1    0.07       0  4982.1    0.05       0
  4991.4   0.075       0  5054.3     0.1       0
Bank Sta=4978.1,4982.1
Exp/Cntr=0.3,0.1

Type RM Length L Ch R = 1,3480,296,296,296
BEGIN DESCRIPTION:
Trib BCA1 Buf 9.5
END DESCRIPTION:
XS GIS Cut Line= 3
      2333501.57      7033276.85      2333619.72      7033272.94
      2334004.64      7033291.93
#Sta/Elev= 30
  4823.1  708.94  4860.6  707.96  4877.1  708.90  4886.1  709.19  4910.6  709.66
  4920.6  710.38  4930.6  709.71  4938.5  708.47  4943.5  708.47  4950.6  704.63
  4960.6  701.49  4982.4  701.25  4982.7  700.75  4986.2  700.75  4986.4  701.25
  4990.7  701.82  5000.7  704.22  5010.7  707.99  5020.7  710.84  5024.2  710.76
  5037.3  710.84  5060.7  711.68  5080.8  712.84  5090.8  712.53  5120.8  713.32
  5186.0  713.46  5220.9  713.09  5251.0  713.74  5271.0  712.04  5326.7  712.75
#Mann=7,-1,0
  4823.1   0.075       0  4877.1    0.05       0  4886.1   0.075       0
  4982.4    0.07       0  4986.4   0.075       0  5024.2    0.05       0
  5037.3   0.075       0
Bank Sta=4982.4,4986.4
Exp/Cntr=0.3,0.1

Type RM Length L Ch R = 1,3184,1252,1252,1252
BEGIN DESCRIPTION:
Tributary BC-1A to Buffalo Creek 9.0
END DESCRIPTION:
XS GIS Cut Line= 5
      2333527.56      7033465.66      2333553.12      7033460.66
      2333706.42      7033527.01      2333958.68      7033668.90
      2334391.46      7033666.81
#Sta/Elev= 30
  4780.7  709.46  4793.0  709.23  4824.1  709.15  4923.0  704.50  4942.4  704.36
  4978.1  702.03  4999.7  694.11  5008.0  693.92  5011.7  692.57  5011.9  692.07
  5015.7  692.57  5022.6  694.27  5029.6  697.88  5045.6  701.53  5067.2  705.05
  5073.0  704.50  5088.9  707.15  5213.2  710.38  5234.9  708.95  5250.8  709.93
  5252.9  709.31  5256.6  708.21  5353.5  713.07  5403.5  710.42  5423.5  710.81
  5443.5  713.20  5643.5  712.66  5653.5  712.90  5673.5  716.25  5696.0  717.72
#Mann=6,-1,0
  4780.7    0.05       0  4793.0   0.075       0  4942.4    0.05       0
  5011.7    0.05       0  5015.7    0.05       0  5252.9   0.075       0
Bank Sta=5011.7,5015.7
Exp/Cntr=0.3,0.1

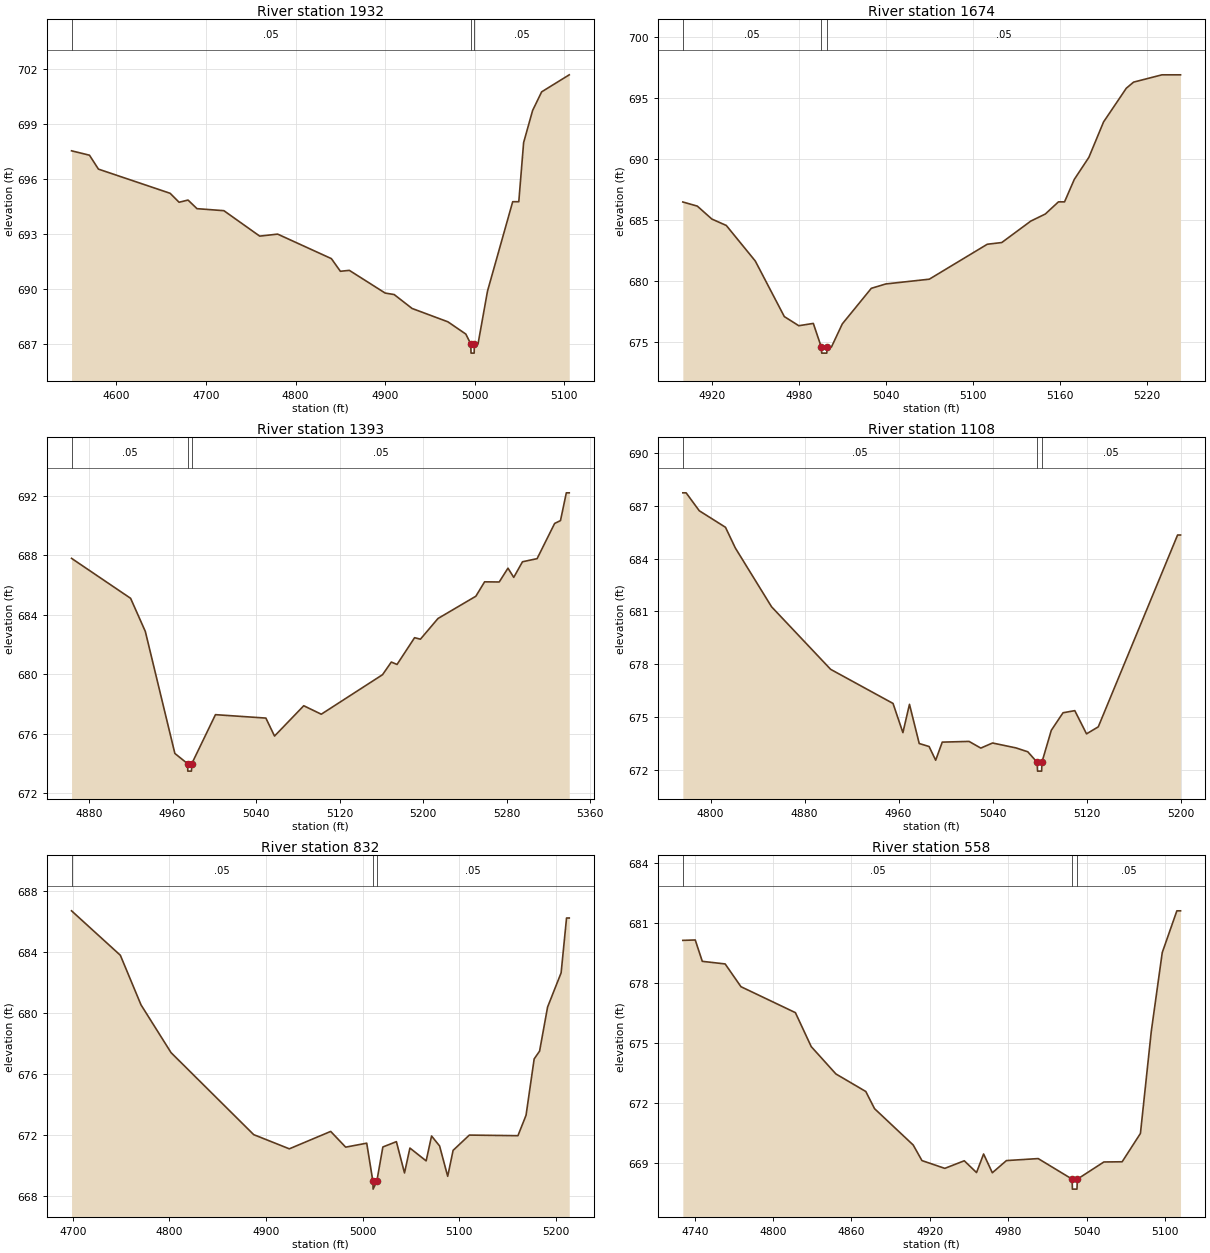
Type RM Length L Ch R = 1,1932,258,258,258
BEGIN DESCRIPTION:
Tributary BC-1A to Buffalo Creek 7.0
END DESCRIPTION:
XS GIS Cut Line= 4
      2333029.00      7033909.95      2333029.00      7034360.00
      2333063.69      7034394.69      2333119.58      7034387.97
#Sta/Elev= 30
  4550.0  697.53  4570.0  697.29  4580.0  696.53  4660.0  695.21  4670.0  694.72
  4680.0  694.84  4690.0  694.37  4720.0  694.26  4760.0  692.87  4780.0  692.98
  4840.0  691.64  4850.0  690.95  4860.0  691.00  4900.0  689.76  4910.0  689.68
  4930.0  688.92  4970.0  688.19  4990.0  687.52  4995.5  686.98  4995.8  686.48
  4999.3  686.48  4999.5  686.98  5003.6  686.98  5014.2  689.87  5042.3  694.75
  5049.1  694.75  5054.5  697.98  5064.5  699.73  5074.6  700.75  5105.4  701.68
#Mann=3,-1,0
  4550.0    0.05       0  4995.5   0.033       0  4999.5    0.05       0
Bank Sta=4995.5,4999.5
Exp/Cntr=0.3,0.1

Type RM Length L Ch R = 1,1674,281,281,281
BEGIN DESCRIPTION:
Tributary BC-1A to Buffalo Creek 6.0
END DESCRIPTION:
XS GIS Cut Line= 4
      2332779.00      7034560.00      2332879.00      7034560.00
      2333042.28      7034560.00      2333121.76      7034550.72
#Sta/Elev= 30
  4900.0  686.47  4910.0  686.13  4920.0  685.07  4930.0  684.54  4950.0  681.62
  4970.0  677.06  4980.0  676.31  4990.0  676.50  4995.5  674.56  4995.8  674.06
  4999.3  674.06  4999.5  674.56  5002.5  674.56  5010.0  676.46  5030.0  679.38
  5040.0  679.74  5070.0  680.13  5110.0  683.00  5120.0  683.14  5140.0  684.90
  5150.0  685.48  5159.1  686.48  5163.3  686.48  5170.0  688.32  5180.1  690.14
  5190.2  693.04  5205.9  695.81  5210.9  696.31  5230.5  696.91  5243.3  696.91
#Mann=3,-1,0
  4900.0    0.05       0  4995.5   0.033       0  4999.5    0.05       0
Bank Sta=4995.5,4999.5
Exp/Cntr=0.3,0.1

Type RM Length L Ch R = 1,1393,285,285,285
BEGIN DESCRIPTION:
Tributary BC-1A to Buffalo Creek 5.0
END DESCRIPTION:
XS GIS Cut Line= 3
      2332678.99      7034709.99      2332779.00      7034810.00
      2333079.04      7034659.98
#Sta/Elev= 30
  4863.2  687.80  4919.8  685.11  4933.9  682.88  4962.2  674.67  4974.4  673.98
  4974.6  673.48  4978.1  673.48  4978.4  673.98  5001.1  677.28  5049.4  677.05
  5057.7  675.84  5085.7  677.88  5102.5  677.31  5161.2  679.97  5169.6  680.82
  5175.1  680.66  5191.9  682.46  5197.5  682.36  5214.3  683.75  5250.6  685.25
  5259.0  686.22  5273.0  686.21  5281.4  687.14  5286.9  686.52  5295.3  687.57
  5309.3  687.78  5326.1  690.15  5331.7  690.34  5337.3  692.21  5340.1  692.21
#Mann=3,-1,0
  4863.2    0.05       0  4974.4   0.033       0  4978.4    0.05       0
Bank Sta=4974.4,4978.4
Exp/Cntr=0.3,0.1

Type RM Length L Ch R = 1,1108,276,276,276
BEGIN DESCRIPTION:
Tributary BC-1A to Buffalo Creek 4.0
END DESCRIPTION:
XS GIS Cut Line= 3
      2332579.01      7034960.00      2332779.00      7035060.00
      2332979.00      7035060.00
#Sta/Elev= 30
  4776.4  687.75  4779.2  687.75  4790.4  686.73  4812.7  685.79  4821.1  684.61
  4851.9  681.27  4902.2  677.71  4955.3  675.77  4963.7  674.11  4969.3  675.72
  4977.6  673.49  4986.0  673.32  4991.6  672.54  4997.2  673.57  5020.0  673.61
  5030.0  673.23  5040.0  673.52  5060.0  673.24  5070.0  673.02  5078.0  672.42
  5078.3  671.92  5081.8  671.92  5082.0  672.42  5090.0  674.24  5100.0  675.24
  5110.0  675.36  5120.0  674.04  5130.0  674.44  5197.5  685.35  5200.0  685.35
#Mann=3,-1,0
  4776.4    0.05       0  5078.0   0.033       0  5082.0    0.05       0
Bank Sta=5078,5082
Exp/Cntr=0.3,0.1

Type RM Length L Ch R = 1,832,274,274,274
BEGIN DESCRIPTION:
Tributary BC-1A to Buffalo Creek 3.0
END DESCRIPTION:
XS GIS Cut Line= 3
      2332529.04      7035160.03      2332779.00      7035310.00
      2332979.00      7035210.00
#Sta/Elev= 30
  4698.7  686.70  4749.2  683.79  4770.6  680.54  4801.7  677.41  4887.2  672.04
  4924.1  671.11  4966.9  672.25  4982.4  671.22  5004.2  671.48  5010.6  668.97
  5010.8  668.47  5014.6  668.97  5020.9  671.23  5034.9  671.58  5043.3  669.53
  5048.9  671.16  5065.7  670.32  5071.3  671.95  5079.6  671.30  5088.0  669.31
  5093.6  671.01  5110.4  672.01  5160.7  671.97  5169.1  673.31  5177.5  677.00
  5183.1  677.51  5191.4  680.40  5205.4  682.64  5211.0  686.23  5213.8  686.23
#Mann=3,-1,0
  4698.7    0.05       0  5010.6   0.033       0  5014.6    0.05       0
Bank Sta=5010.6,5014.6
Exp/Cntr=0.3,0.1

Type RM Length L Ch R = 1,558,223,223,223
BEGIN DESCRIPTION:
Tributary BC-1A to Buffalo Creek 2.0
END DESCRIPTION:
XS GIS Cut Line= 3
      2332578.98      7035259.96      2332679.00      7035510.00
      2332729.00      7035609.99
#Sta/Elev= 30
  4730.9  680.13  4740.4  680.15  4745.8  679.08  4763.3  678.95  4775.4  677.81
  4817.1  676.51  4829.2  674.81  4848.1  673.44  4871.0  672.56  4877.7  671.70
  4907.3  669.88  4914.0  669.10  4931.5  668.71  4946.4  669.09  4955.8  668.50
  4961.2  669.43  4967.9  668.49  4978.7  669.10  5003.0  669.20  5029.0  668.17
  5029.2  667.67  5032.7  667.67  5033.0  668.17  5053.3  669.03  5067.3  669.04
  5081.3  670.46  5089.6  675.57  5098.0  679.52  5109.2  681.61  5112.0  681.61
#Mann=3,-1,0
  4730.9    0.05       0  5029.0   0.033       0  5033.0    0.05       0
Bank Sta=5029,5033
Exp/Cntr=0.3,0.1

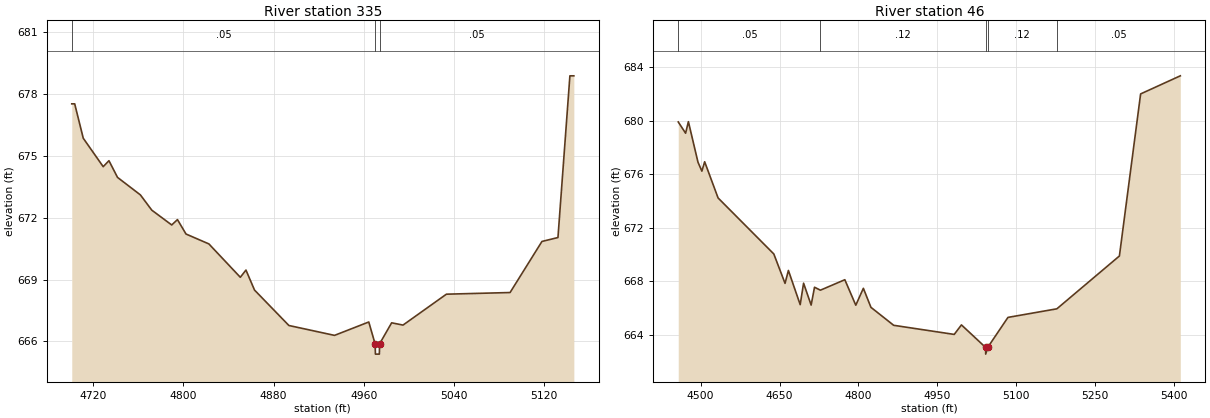
Type RM Length L Ch R = 1,335,289,289,289
BEGIN DESCRIPTION:
Tributary BC-1A to Buffalo Creek 1.0
END DESCRIPTION:
XS GIS Cut Line= 3
      2332579.01      7035359.97      2332529.00      7035660.00
      2332629.00      7035760.00
#Sta/Elev= 30
  4700.9  677.53  4703.5  677.53  4711.1  675.86  4728.8  674.48  4733.9  674.77
  4741.5  673.96  4761.8  673.11  4771.9  672.37  4789.6  671.65  4794.7  671.91
  4802.3  671.21  4822.6  670.73  4850.5  669.11  4855.5  669.46  4863.1  668.49
  4893.6  666.77  4934.1  666.29  4964.5  666.94  4970.1  665.88  4970.4  665.38
  4973.9  665.38  4974.1  665.88  4984.8  666.90  4994.9  666.79  5033.4  668.29
  5089.9  668.37  5118.2  670.85  5132.4  671.04  5143.0  678.89  5146.5  678.89
#Mann=3,-1,0
  4700.9    0.05       0  4970.1   0.033       0  4974.1    0.05       0
Bank Sta=4970.1,4974.1
Exp/Cntr=0.3,0.1

Type RM Length L Ch R = 1,46,0,0,0
BEGIN DESCRIPTION:
9990
END DESCRIPTION:
XS GIS Cut Line= 6
      2332559.74      7035344.67      2332510.70      7035482.45
      2332312.27      7035729.90      2332328.61      7035830.28
      2332379.97      7035839.62      2332713.80      7035881.64
#Sta/Elev= 30
  4457.6  679.90  4471.6  679.06  4476.9  679.92  4495.1  676.90  4502.5  676.23
  4507.8  676.93  4533.3  674.23  4639.2  670.05  4660.5  667.86  4666.9  668.82
  4689.3  666.27  4695.7  667.87  4710.1  666.24  4716.5  667.57  4727.7  667.35
  4774.1  668.13  4794.9  666.23  4809.3  667.49  4823.7  666.07  4866.9  664.73
  4981.9  664.05  4995.6  664.76  5041.5  663.08  5041.7  662.58  5045.5  663.08
  5084.0  665.32  5176.9  665.96  5295.7  669.90  5336.0  681.99  5411.4  683.34
#Mann=5,-1,0
  4457.6    0.05       0  4727.7    0.12       0  5041.5    0.07       0
  5045.5    0.12       0  5176.9    0.05       0
Bank Sta=5041.5,5045.5
Exp/Cntr=0.3,0.1

Chan Stop Cuts=-1