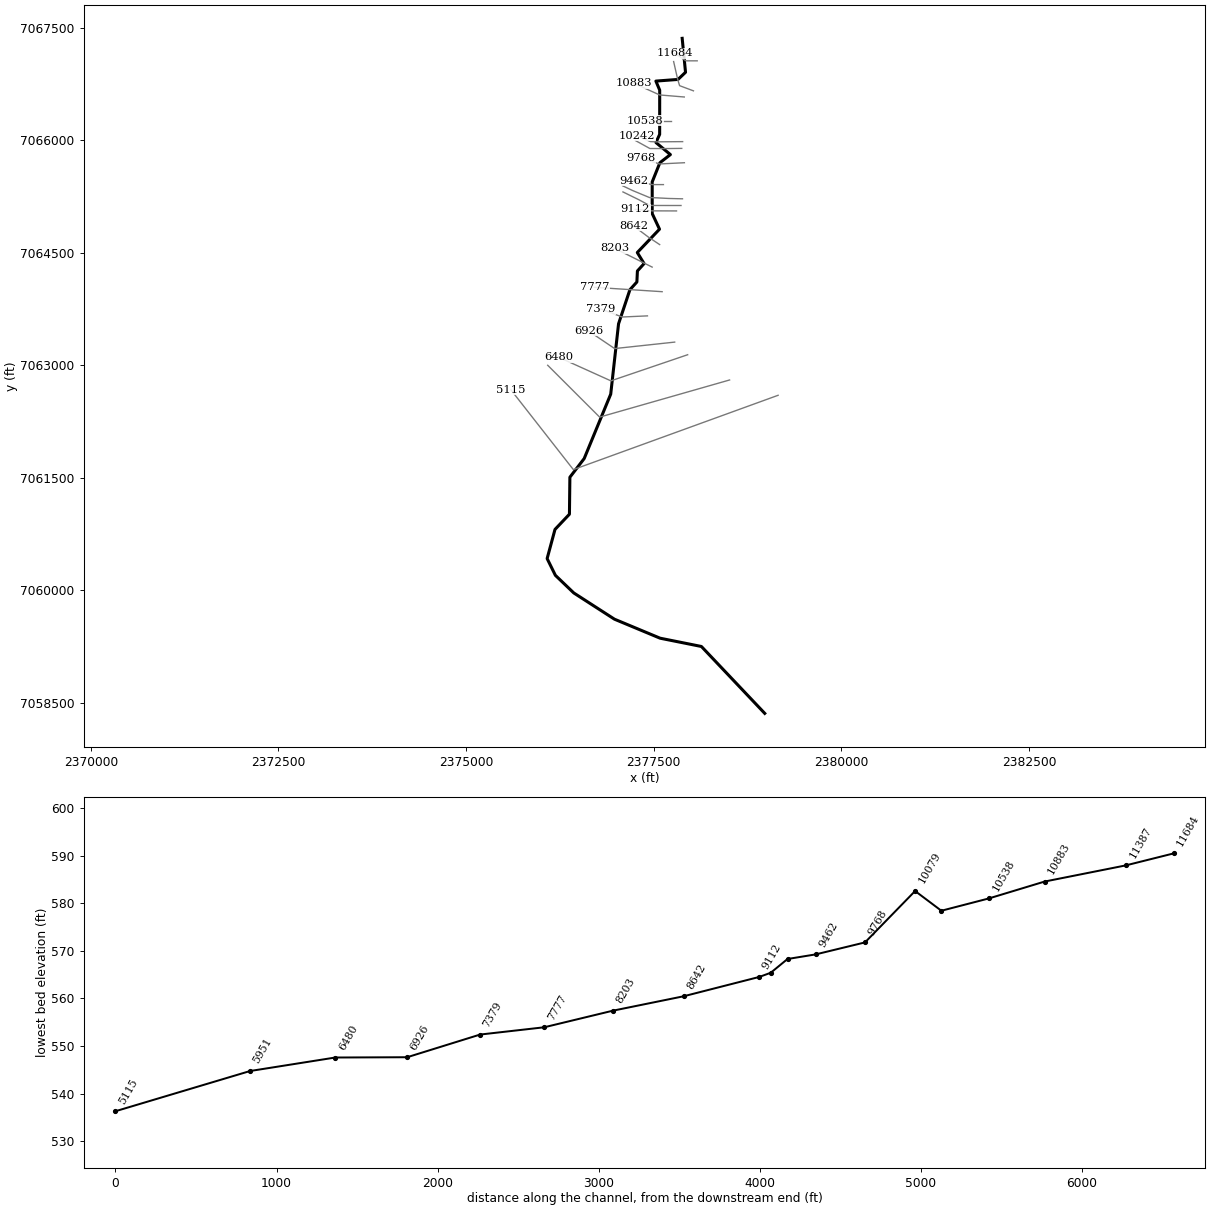
--- Unnamed 1.prj (project) ---

Proj Title=Unnamed 1 Base Level Engineering
Current Plan=p01
Default Exp/Contr=0.3,0.1
English Units
Geom File=g01
Flow File=f01
Plan File=p01
BEGIN DESCRIPTION:
Unnamed 1
END DESCRIPTION:

--- Unnamed 1.p01 (plan) ---

Plan Title=Multiple Run
Short Identifier=Multiple
Geom File=g01
Flow File=f01
Subcritical Flow
K Sum by GR= 0
Std Step Tol= 0.01
Critical Tol= 0.01
Num of Std Step Trials= 20
Max Error Tol= 0.3
Flow Tol Ratio= 0.001
Split Flow NTrial= 30
Split Flow Tol= 0.02
Split Flow Ratio= 0.02
Log Output Level= 0
Friction Slope Method= 1
Unsteady Friction Slope Method= 2
Unsteady Bridges Friction Slope Method= 1
Parabolic Critical Depth
Global Vel Dist=  1 , 1 , 1
Global Log Level= 0
CheckData=True
Encroach Param= -1, 0, 0, 0
BEGIN DESCRIPTION:
Multiple Run
END DESCRIPTION:

--- Unnamed 1.f01 (steady flow) ---

Flow Title=Multiple
Number of Profiles=7
Profile Names=10-year,25-year,50-year,1pct_min,100-year,1pct_plu,500-year
River Rch & RM= Unnamed 1,Reach-1,11684
     667     926    1144     703    1402    2797    2108
River Rch & RM= Unnamed 1,Reach-1,10883
     780    1091    1354     834    1664    3321    2521
River Rch & RM= Unnamed 1,Reach-1,7379
     985    1392    1739    1078    2150    4291    3297
Boundary for River Rch & Prof#=Unnamed 1,Reach-1,1
Up Type=0
Dn Type=3
Dn Slope=0.005
Boundary for River Rch & Prof#=Unnamed 1,Reach-1,2
Up Type=0
Dn Type=3
Dn Slope=0.005
Boundary for River Rch & Prof#=Unnamed 1,Reach-1,3
Up Type=0
Dn Type=3
Dn Slope=0.005
Boundary for River Rch & Prof#=Unnamed 1,Reach-1,4
Up Type=0
Dn Type=3
Dn Slope=0.005
Boundary for River Rch & Prof#=Unnamed 1,Reach-1,5
Up Type=0
Dn Type=3
Dn Slope=0.005
Boundary for River Rch & Prof#=Unnamed 1,Reach-1,6
Up Type=0
Dn Type=3
Dn Slope=0.005
Boundary for River Rch & Prof#=Unnamed 1,Reach-1,7
Up Type=0
Dn Type=3
Dn Slope=0.005

--- Unnamed 1.g01 (geometry) ---

Geom Title=Existing Conditions

River Reach=Unnamed 1,Reach-1
Reach XY= 30
      2377879.00      7067360.00      2377923.55      7066907.53
      2377823.57      7066812.16      2377528.58      7066789.91
      2377579.44      7066669.28      2377578.91      7066080.02
      2377529.53      7065970.47      2377721.94      7065810.00
      2377582.17      7065701.66      2377479.67      7065446.09
      2377479.54      7065023.86      2377576.93      7064815.47
      2377280.88      7064504.28      2377371.39      7064356.67
      2377282.57      7064258.53      2377275.44      7064111.47
      2377182.62      7064008.50      2377031.35      7063554.48
      2376926.76      7062615.93      2376573.48      7061757.57
      2376382.75      7061508.45      2376376.83      7061015.44
      2376184.47      7060812.45      2376079.54      7060423.97
      2376189.76      7060200.30      2376434.62      7059965.62
      2376976.71      7059615.84      2377584.53      7059362.39
      2378135.06      7059251.86      2378979.00      7058360.00

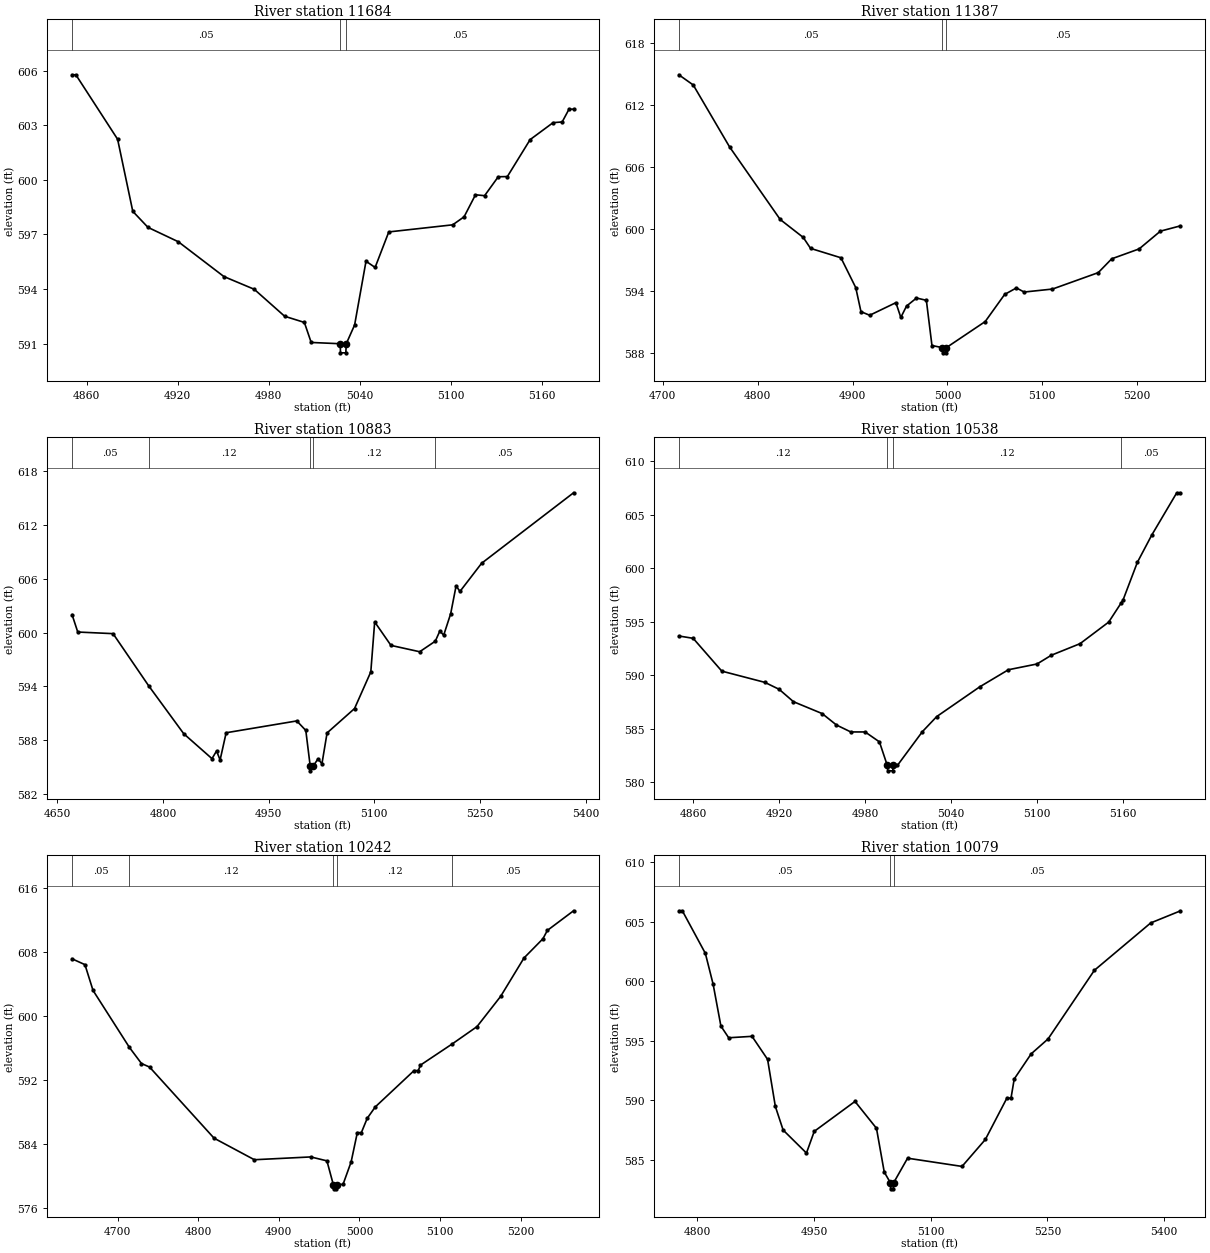
Type RM Length L Ch R = 1,11684,297,297,297
BEGIN DESCRIPTION:
Unnamed 1 24.0
END DESCRIPTION:
XS GIS Cut Line= 3
      2378079.02      7067060.00      2377929.00      7067060.00
      2377778.99      7067160.00
#Sta/Elev= 30
  4850.4  605.77  4852.9  605.77  4880.4  602.23  4890.4  598.27  4900.4  597.39
  4920.4  596.60  4950.4  594.69  4970.4  593.99  4990.4  592.51  5003.4  592.17
  5007.9  591.07  5027.0  591.00  5027.2  590.50  5030.7  590.50  5031.0  591.00
  5036.5  592.03  5044.0  595.53  5050.0  595.19  5059.0  597.14  5101.1  597.53
  5108.6  597.97  5116.1  599.18  5122.1  599.13  5131.1  600.17  5137.1  600.18
  5152.1  602.21  5167.2  603.14  5173.2  603.18  5177.7  603.88  5180.7  603.88
#Mann=3,-1,0
  4850.4    0.05       0  5027.0   0.033       0  5031.0    0.05       0
Bank Sta=5027,5031
Exp/Cntr=0.3,0.1

Type RM Length L Ch R = 1,11387,504,504,504
BEGIN DESCRIPTION:
Unnamed 1 23.0
END DESCRIPTION:
XS GIS Cut Line= 4
      2378029.03      7066659.99      2377844.56      7066728.86
      2377819.42      7066811.20      2377765.12      7067050.52
#Sta/Elev= 30
  4717.0  614.92  4732.2  613.93  4770.4  607.94  4823.8  600.90  4848.1  599.16
  4855.8  598.10  4887.8  597.19  4903.4  594.30  4908.9  591.97  4918.1  591.62
  4945.7  592.84  4950.9  591.41  4956.9  592.51  4967.4  593.29  4977.8  593.07
  4983.7  588.69  4994.8  588.48  4995.0  587.98  4998.5  587.98  4998.8  588.48
  5039.8  591.01  5060.3  593.64  5072.7  594.27  5080.8  593.87  5110.7  594.16
  5158.9  595.75  5173.1  597.09  5202.0  598.05  5224.4  599.77  5245.4  600.28
#Mann=3,-1,0
  4717.0    0.05       0  4994.8   0.033       0  4998.8    0.05       0
Bank Sta=4994.8,4998.8
Exp/Cntr=0.3,0.1

Type RM Length L Ch R = 1,10883,345,345,345
BEGIN DESCRIPTION:
Unnamed 1 22.0
END DESCRIPTION:
XS GIS Cut Line= 3
      2377907.04      7066577.82      2377579.08      7066605.17
      2377229.98      7066762.71
#Sta/Elev= 30
  4670.9  602.01  4679.0  600.07  4729.1  599.89  4779.6  594.08  4829.5  588.72
  4869.6  585.94  4876.1  586.80  4881.1  585.79  4889.7  588.83  4990.0  590.15
  5002.8  589.09  5009.1  585.08  5009.3  584.58  5013.1  585.08  5020.2  585.93
  5025.7  585.36  5033.0  588.81  5072.0  591.53  5095.1  595.62  5100.6  601.20
  5123.7  598.58  5164.5  597.87  5186.7  599.05  5193.1  600.18  5198.6  599.72
  5208.5  602.11  5216.2  605.22  5221.7  604.60  5252.4  607.74  5383.0  615.61
#Mann=5,-1,0
  4670.9    0.05       0  4779.6    0.12       0  5009.1    0.07       0
  5013.1    0.12       0  5186.7    0.05       0
Bank Sta=5009.1,5013.1
Exp/Cntr=0.3,0.1

Type RM Length L Ch R = 1,10538,296,296,296
BEGIN DESCRIPTION:
Unnamed 1 21.0
END DESCRIPTION:
XS GIS Cut Line= 3
      2377729.02      7066260.00      2377579.00      7066260.00
      2377379.02      7066260.00
#Sta/Elev= 30
  4850.0  593.66  4860.0  593.44  4880.0  590.37  4910.0  589.32  4920.0  588.67
  4930.0  587.51  4950.0  586.40  4960.0  585.33  4970.0  584.68  4980.0  584.68
  4990.0  583.75  4995.5  581.54  4995.8  581.04  4999.3  581.04  4999.5  581.54
  5002.5  581.54  5020.0  584.71  5030.0  586.12  5060.0  588.90  5080.0  590.50
  5100.0  591.04  5110.0  591.86  5130.0  592.94  5150.0  594.96  5158.5  596.71
  5160.0  597.02  5170.0  600.55  5180.0  603.09  5197.5  607.06  5200.0  607.06
#Mann=4,-1,0
  4850.0    0.12       0  4995.5    0.07       0  4999.5    0.12       0
  5158.5    0.05       0
Bank Sta=4995.5,4999.5
Exp/Cntr=0.3,0.1

Type RM Length L Ch R = 1,10242,163,163,163
BEGIN DESCRIPTION:
Unnamed 1 20.0
END DESCRIPTION:
XS GIS Cut Line= 4
      2377885.05      7065982.91      2377528.56      7065980.03
      2377457.79      7065982.88      2377279.04      7066059.98
#Sta/Elev= 30
  4643.5  607.13  4659.5  606.40  4669.5  603.19  4714.7  596.07  4729.6  594.07
  4739.6  593.63  4819.6  584.76  4869.6  582.07  4939.6  582.42  4959.6  581.93
  4967.6  578.94  4967.8  578.44  4971.3  578.44  4971.6  578.94  4979.6  579.00
  4989.6  581.79  4997.3  585.45  5002.3  585.45  5009.6  587.24  5019.6  588.66
  5067.7  593.19  5072.9  593.19  5075.6  593.87  5115.1  596.52  5145.7  598.67
  5175.1  602.45  5204.0  607.23  5227.5  609.63  5233.0  610.67  5265.5  613.12
#Mann=5,-1,0
  4643.5    0.05       0  4714.7    0.12       0  4967.6    0.07       0
  4971.6    0.12       0  5115.1    0.05       0
Bank Sta=4967.6,4971.6
Exp/Cntr=0.3,0.1

Type RM Length L Ch R = 1,10079,311,311,311
BEGIN DESCRIPTION:
Mapping XS 808970a2
END DESCRIPTION:
XS GIS Cut Line= 4
      2377873.05      7065892.60      2377649.17      7065890.21
      2377448.59      7065891.04      2377255.68      7065997.48
#Sta/Elev= 30
  4776.1  605.91  4780.6  605.91  4810.2  602.34  4820.2  599.75  4830.2  596.24
  4840.2  595.26  4870.2  595.38  4890.2  593.45  4900.2  589.50  4910.2  587.52
  4940.2  585.59  4950.2  587.41  5002.6  589.92  5030.2  587.67  5040.2  584.00
  5048.2  583.09  5048.4  582.59  5051.9  582.59  5052.2  583.09  5070.2  585.16
  5140.2  584.47  5170.2  586.73  5197.9  590.20  5203.2  590.20  5207.3  591.80
  5229.1  593.91  5250.8  595.16  5310.4  600.92  5382.8  604.89  5420.9  605.90
#Mann=3,-1,0
  4776.1    0.05       0  5048.2   0.033       0  5052.2    0.05       0
Bank Sta=5048.2,5052.2
Exp/Cntr=0.3,0.1

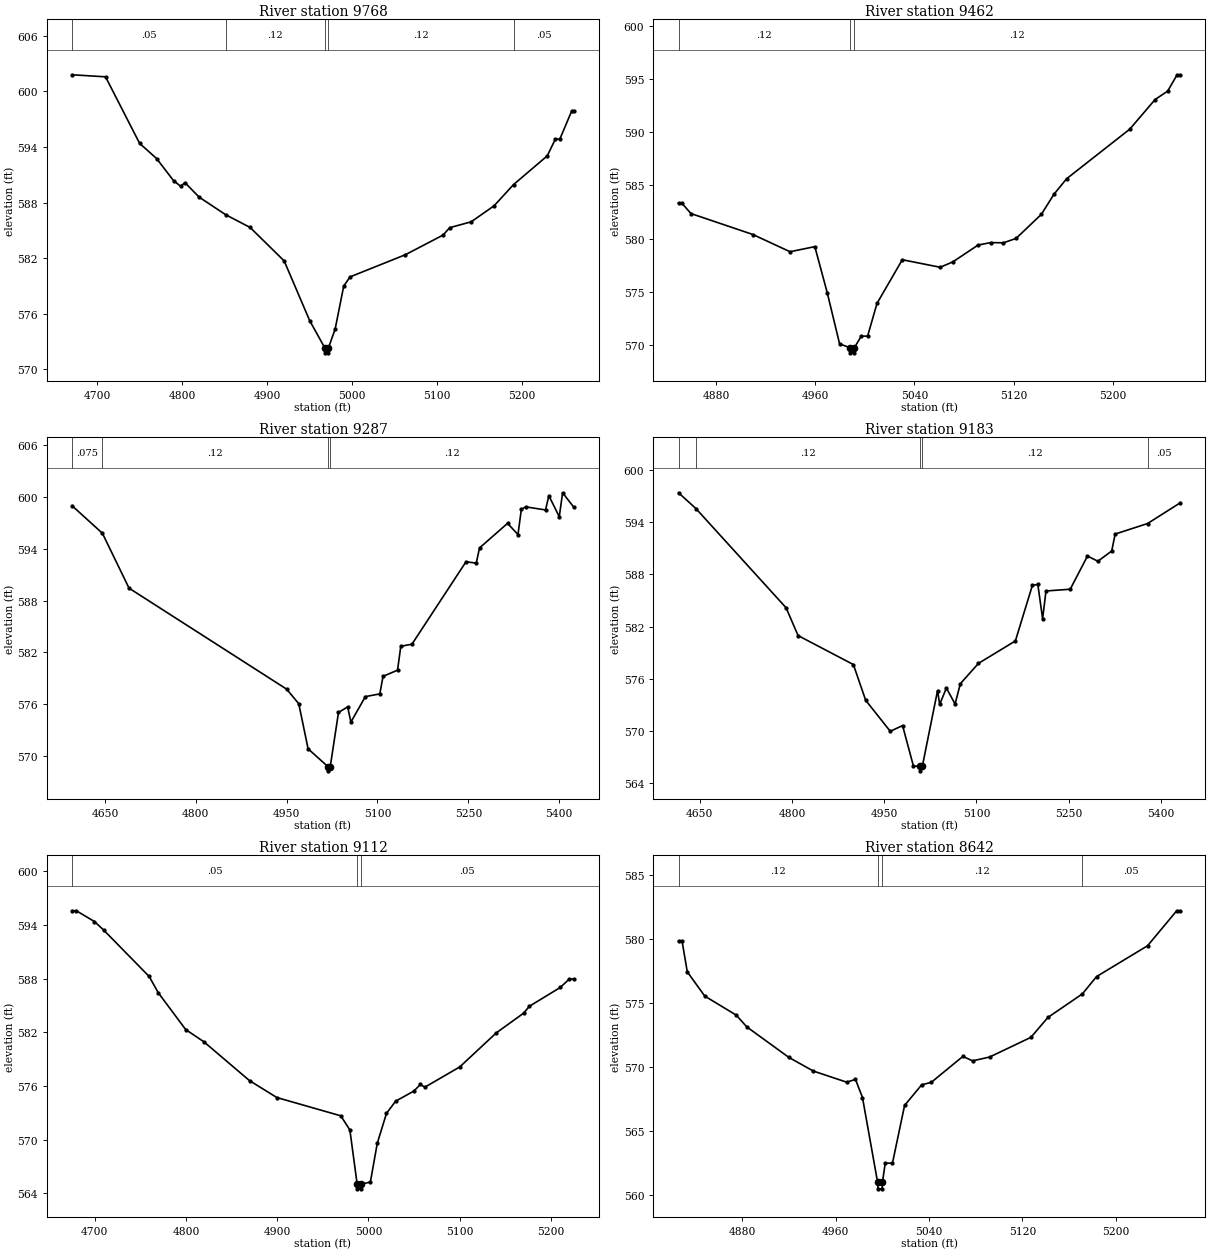
Type RM Length L Ch R = 1,9768,306,306,306
BEGIN DESCRIPTION:
Unnamed 1 19.0
END DESCRIPTION:
XS GIS Cut Line= 3
      2377908.36      7065701.52      2377578.87      7065685.12
      2377329.05      7065759.99
#Sta/Elev= 30
  4670.1  601.79  4709.5  601.57  4749.6  594.39  4769.6  592.75  4789.6  590.36
  4797.9  589.76  4803.0  590.15  4819.6  588.59  4850.9  586.69  4879.7  585.31
  4919.8  581.70  4949.8  575.26  4967.8  572.28  4968.1  571.78  4971.6  571.78
  4971.8  572.28  4979.8  574.35  4989.9  578.99  4997.4  579.98  5062.5  582.37
  5106.8  584.49  5114.7  585.29  5139.9  585.92  5166.9  587.65  5189.8  589.94
  5229.5  593.04  5239.1  594.86  5244.3  594.85  5258.2  597.87  5260.8  597.87
#Mann=5,-1,0
  4670.1    0.05       0  4850.9    0.12       0  4967.8    0.07       0
  4971.8    0.12       0  5189.8    0.05       0
Bank Sta=4967.8,4971.8
Exp/Cntr=0.3,0.1

Type RM Length L Ch R = 1,9462,175,175,175
BEGIN DESCRIPTION:
Unnamed 1 18.0
END DESCRIPTION:
XS GIS Cut Line= 3
      2377629.00      7065410.00      2377479.00      7065410.00
      2377228.96      7065460.01
#Sta/Elev= 30
  4849.6  583.35  4852.1  583.35  4859.6  582.35  4909.6  580.38  4939.6  578.76
  4959.6  579.24  4969.6  574.92  4979.6  570.10  4987.6  569.76  4987.9  569.26
  4991.4  569.26  4991.6  569.76  4997.1  570.83  5002.2  570.83  5009.8  573.91
  5030.2  578.01  5060.8  577.30  5071.0  577.81  5091.4  579.39  5101.6  579.62
  5111.8  579.60  5122.0  580.01  5142.4  582.27  5152.6  584.16  5162.8  585.62
  5213.8  590.28  5234.2  593.06  5244.4  593.86  5252.0  595.39  5254.6  595.39
#Mann=3,-1,0
  4849.6    0.12       0  4987.6    0.07       0  4991.6    0.12       0
Bank Sta=4987.6,4991.6
Exp/Cntr=0.3,0.1

Type RM Length L Ch R = 1,9287,104,104,104
BEGIN DESCRIPTION:
Mapping XS 1430959e
END DESCRIPTION:
XS GIS Cut Line= 6
      2377883.08      7065220.54      2377699.05      7065225.06
      2377541.41      7065233.39      2377442.80      7065237.56
      2377216.29      7065331.81      2377087.37      7065393.02
#Sta/Elev= 30
  4595.6  599.00  4645.7  595.81  4689.7  589.45  4950.0  577.75  4970.0  576.06
  4985.4  570.84  5018.0  568.79  5018.3  568.29  5022.0  568.79  5035.6  575.05
  5050.7  575.70  5056.1  573.94  5080.0  576.89  5103.8  577.20  5109.2  579.24
  5133.1  579.95  5138.5  582.72  5156.9  582.96  5246.2  592.51  5263.1  592.35
  5268.5  594.11  5314.8  596.96  5332.0  595.66  5337.6  598.59  5345.0  598.87
  5377.5  598.51  5383.0  600.16  5400.2  597.73  5405.7  600.50  5424.3  598.82
#Mann=4,-1,0
  4595.6   0.075       0  4645.7    0.12       0  5018.0    0.07       0
  5022.0    0.12       0
Bank Sta=5018,5022
Exp/Cntr=0.3,0.1

Type RM Length L Ch R = 1,9183,71,71,71
BEGIN DESCRIPTION:
Mapping XS d1dd742e
END DESCRIPTION:
XS GIS Cut Line= 6
      2377863.44      7065131.29      2377692.85      7065131.29
      2377478.94      7065131.65      2377437.07      7065135.30
      2377302.23      7065208.12      2377089.99      7065312.28
#Sta/Elev= 30
  4615.5  597.40  4643.7  595.59  4790.5  584.16  4809.9  580.97  4899.9  577.63
  4919.9  573.52  4959.9  569.95  4979.9  570.61  4997.5  565.97  5008.0  565.90
  5008.2  565.40  5012.0  565.90  5036.8  574.63  5040.3  573.05  5051.2  574.93
  5065.3  573.09  5073.9  575.43  5103.4  577.77  5163.4  580.35  5191.0  586.73
  5199.9  586.86  5207.7  582.91  5213.2  586.10  5252.6  586.30  5280.7  590.12
  5297.6  589.52  5320.1  590.70  5325.7  592.65  5378.4  593.86  5431.7  596.25
#Mann=5,-1,0
  4615.5   0.075       0  4643.7    0.12       0  5008.0    0.07       0
  5012.0    0.12       0  5378.4    0.05       0
Bank Sta=5008,5012
Exp/Cntr=0.3,0.1

Type RM Length L Ch R = 1,9112,470,470,470
BEGIN DESCRIPTION:
Unnamed 1 17.0
END DESCRIPTION:
XS GIS Cut Line= 3
      2377803.49      7065058.81      2377479.00      7065060.00
      2377254.30      7065079.04
#Sta/Elev= 30
  4675.1  595.59  4679.8  595.59  4699.6  594.39  4709.6  593.45  4759.6  588.25
  4769.6  586.43  4799.6  582.32  4819.6  580.95  4869.6  576.61  4899.6  574.72
  4969.6  572.68  4979.6  571.10  4987.6  565.02  4987.8  564.52  4991.3  564.52
  4991.6  565.02  5002.1  565.29  5009.6  569.60  5019.7  572.95  5029.7  574.31
  5049.8  575.45  5056.8  576.18  5061.8  575.88  5100.0  578.14  5140.1  581.95
  5170.2  584.16  5176.2  584.91  5210.3  587.03  5220.2  587.97  5225.1  587.97
#Mann=3,-1,0
  4675.1    0.05       0  4987.6   0.033       0  4991.6    0.05       0
Bank Sta=4987.6,4991.6
Exp/Cntr=0.3,0.1

Type RM Length L Ch R = 1,8642,439,439,439
BEGIN DESCRIPTION:
Unnamed 1 16.0
END DESCRIPTION:
XS GIS Cut Line= 3
      2377578.96      7064610.03      2377429.00      7064710.00
      2377229.02      7064859.98
#Sta/Elev= 30
  4825.2  579.86  4828.2  579.86  4832.7  577.44  4847.7  575.54  4874.7  574.05
  4883.7  573.13  4919.8  570.74  4940.8  569.67  4969.4  568.80  4976.9  569.02
  4982.9  567.60  4995.9  560.95  4996.2  560.45  4999.7  560.45  5000.0  560.95
  5002.4  562.46  5008.6  562.46  5019.0  566.98  5033.6  568.59  5041.9  568.79
  5069.0  570.82  5077.3  570.47  5091.9  570.77  5127.3  572.31  5141.9  573.87
  5171.4  575.71  5183.6  577.07  5227.3  579.48  5252.3  582.22  5255.4  582.22
#Mann=4,-1,0
  4825.2    0.12       0  4995.9    0.07       0  5000.0    0.12       0
  5171.4    0.05       0
Bank Sta=4995.9,5000
Exp/Cntr=0.3,0.1

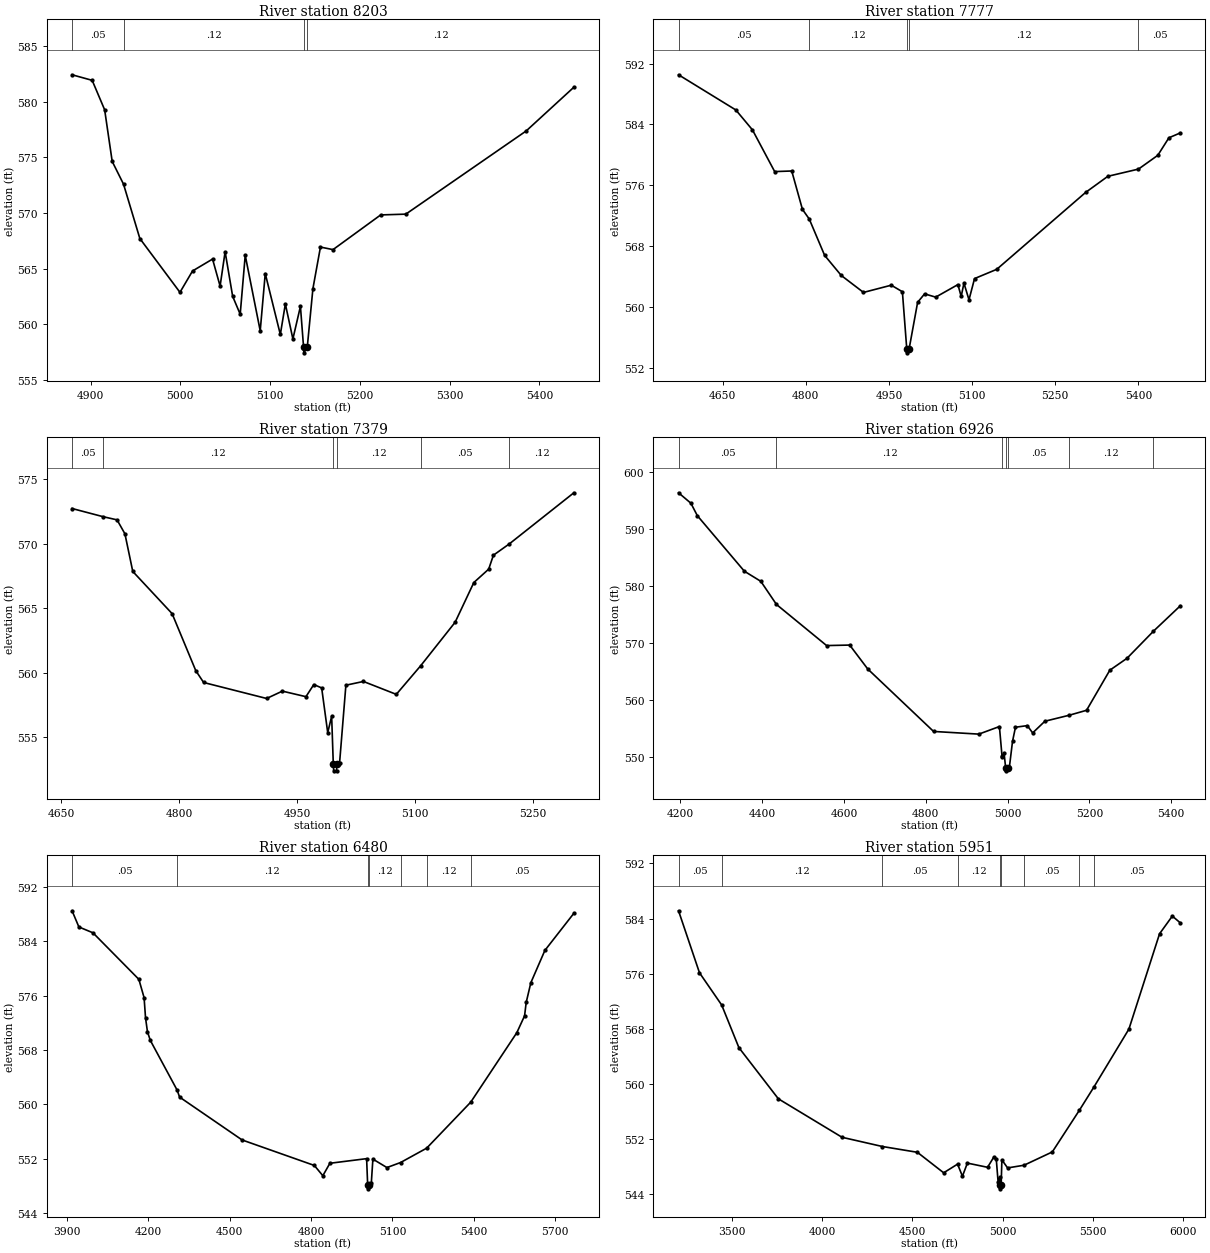
Type RM Length L Ch R = 1,8203,426,426,426
BEGIN DESCRIPTION:
Unnamed 1 15.0
END DESCRIPTION:
XS GIS Cut Line= 3
      2377479.01      7064310.00      2377379.00      7064360.00
      2376979.02      7064559.99
#Sta/Elev= 30
  4879.4  582.42  4901.8  581.92  4915.7  579.27  4924.1  574.63  4936.7  572.59
  4954.9  567.70  4999.6  562.86  5013.6  564.78  5035.9  565.85  5044.3  563.42
  5049.9  566.51  5058.3  562.50  5066.7  560.89  5072.3  566.19  5089.0  559.40
  5094.6  564.55  5111.4  559.07  5117.0  561.81  5125.4  558.67  5133.8  561.60
  5137.3  557.92  5137.6  557.42  5141.4  557.92  5147.7  563.19  5156.1  566.93
  5170.1  566.70  5223.2  569.82  5251.2  569.89  5385.3  577.37  5438.4  581.30
#Mann=4,-1,0
  4879.4    0.05       0  4936.7    0.12       0  5137.3    0.07       0
  5141.4    0.12       0
Bank Sta=5137.3,5141.4
Exp/Cntr=0.3,0.1

Type RM Length L Ch R = 1,7777,398,398,398
BEGIN DESCRIPTION:
Unnamed 1 14.0
END DESCRIPTION:
XS GIS Cut Line= 3
      2377612.14      7063982.17      2377179.00      7064010.00
      2376708.43      7064040.64
#Sta/Elev= 30
  4570.2  590.52  4673.6  585.89  4703.6  583.27  4743.7  577.78  4774.5  577.86
  4793.8  572.81  4806.1  571.54  4833.9  566.75  4863.9  564.11  4904.0  561.88
  4954.1  562.83  4974.2  561.97  4982.1  554.43  4982.4  553.93  4986.3  554.43
  5001.7  560.58  5014.3  561.69  5034.3  561.26  5074.4  562.91  5080.3  561.35
  5085.3  563.10  5094.4  560.91  5104.4  563.70  5144.5  564.92  5304.9  575.04
  5345.0  577.16  5400.3  578.11  5435.1  579.92  5455.2  582.23  5475.8  582.87
#Mann=5,-1,0
  4570.2    0.05       0  4806.1    0.12       0  4982.1    0.07       0
  4986.3    0.12       0  5400.3    0.05       0
Bank Sta=4982.1,4986.3
Exp/Cntr=0.3,0.1

Type RM Length L Ch R = 1,7379,453,453,453
BEGIN DESCRIPTION:
Unnamed 1 13.0
END DESCRIPTION:
XS GIS Cut Line= 3
      2377416.11      7063659.67      2377079.95      7063644.61
      2376797.67      7063750.80
#Sta/Elev= 30
  4663.5  572.74  4702.7  572.11  4720.7  571.86  4730.7  570.78  4740.7  567.86
  4790.7  564.59  4820.8  560.17  4830.8  559.25  4910.9  558.01  4930.9  558.58
  4960.9  558.15  4970.9  559.09  4980.9  558.83  4988.6  555.36  4993.6  556.63
  4995.7  552.90  4996.2  552.40  4999.8  552.40  5000.2  552.90  5003.7  553.03
  5011.7  559.04  5034.0  559.33  5075.8  558.33  5106.7  560.54  5150.6  563.92
  5174.4  567.00  5193.3  568.04  5199.3  569.12  5219.6  570.00  5301.6  573.96
#Mann=6,-1,0
  4663.5    0.05       0  4702.7    0.12       0  4995.7    0.07       0
  5000.2    0.12       0  5106.7    0.05       0  5219.6    0.12       0
Bank Sta=4995.7,5000.2
Exp/Cntr=0.3,0.1

Type RM Length L Ch R = 1,6926,446,446,446
BEGIN DESCRIPTION:
Unnamed 1 12.0
END DESCRIPTION:
XS GIS Cut Line= 3
      2377779.03      7063310.00      2376978.87      7063223.69
      2376629.00      7063460.00
#Sta/Elev= 30
  4195.2  596.40  4225.4  594.57  4241.2  592.38  4356.2  582.64  4396.4  580.87
  4434.7  576.81  4557.3  569.60  4613.7  569.69  4657.9  565.49  4818.8  554.54
  4929.5  554.07  4979.8  555.40  4986.3  550.14  4987.2  550.24  4991.3  550.70
  4995.1  548.13  4995.6  547.63  4999.8  548.13  5004.1  548.21  5011.9  552.81
  5019.1  555.28  5048.1  555.56  5061.1  554.28  5091.0  556.33  5150.4  557.38
  5192.9  558.25  5249.8  565.28  5291.8  567.37  5356.6  572.13  5422.2  576.58
#Mann=7,-1,0
  4195.2    0.05       0  4434.7    0.12       0  4987.2    0.05       0
  4995.1   0.033       0  4999.8    0.05       0  5150.4    0.12       0
  5356.6    0.05       0
Bank Sta=4995.1,4999.8
Exp/Cntr=0.3,0.1

Type RM Length L Ch R = 1,6480,529,529,529
BEGIN DESCRIPTION:
Unnamed 1 11.0
END DESCRIPTION:
XS GIS Cut Line= 3
      2377951.93      7063141.70      2376929.00      7062793.40
      2376228.97      7063110.01
#Sta/Elev= 30
  3919.4  588.46  3944.5  586.08  3996.4  585.22  4165.5  578.38  4184.8  575.68
  4190.1  572.70  4197.2  570.67  4207.7  569.40  4306.6  562.08  4315.6  561.06
  4545.8  554.76  4812.0  551.01  4843.4  549.50  4869.4  551.33  5004.7  552.01
  5008.6  548.07  5009.1  547.57  5013.4  548.07  5022.0  548.42  5027.8  551.94
  5079.5  550.70  5129.8  551.44  5225.9  553.55  5388.4  560.32  5558.1  570.53
  5586.7  573.01  5592.7  574.99  5609.8  577.88  5661.5  582.63  5768.3  588.09
#Mann=7,-1,0
  3919.4    0.05       0  4306.6    0.12       0  5008.6    0.07       0
  5013.4    0.12       0  5129.8    0.05       0  5225.9    0.12       0
  5388.4    0.05       0
Bank Sta=5008.6,5013.4
Exp/Cntr=0.3,0.1

Type RM Length L Ch R = 1,5951,836,836,836
BEGIN DESCRIPTION:
Unnamed 1 10.0
END DESCRIPTION:
XS GIS Cut Line= 3
      2378510.54      7062804.99      2376779.00      7062310.00
      2376087.40      7063001.07
#Sta/Elev= 30
  3204.8  585.13  3320.8  576.12  3443.7  571.44  3539.2  565.24  3757.6  557.81
  4110.2  552.22  4333.8  550.88  4527.3  550.04  4672.9  547.06  4749.9  548.32
  4776.9  546.56  4804.2  548.47  4916.0  547.86  4949.8  549.31  4964.1  549.09
  4974.5  545.70  4983.6  546.42  4986.4  545.23  4987.0  544.73  4991.2  545.23
  4995.3  548.94  5026.9  547.77  5117.9  548.16  5274.4  550.09  5424.5  556.15
  5505.8  559.56  5698.7  567.94  5868.4  581.79  5939.1  584.36  5983.4  583.37
#Mann=9,-1,0
  3204.8    0.05       0  3443.7    0.12       0  4333.8    0.05       0
  4749.9    0.12       0  4986.4    0.07       0  4991.2    0.12       0
  5117.9    0.05       0  5424.5    0.12       0  5505.8    0.05       0
Bank Sta=4986.4,4991.2
Exp/Cntr=0.3,0.1

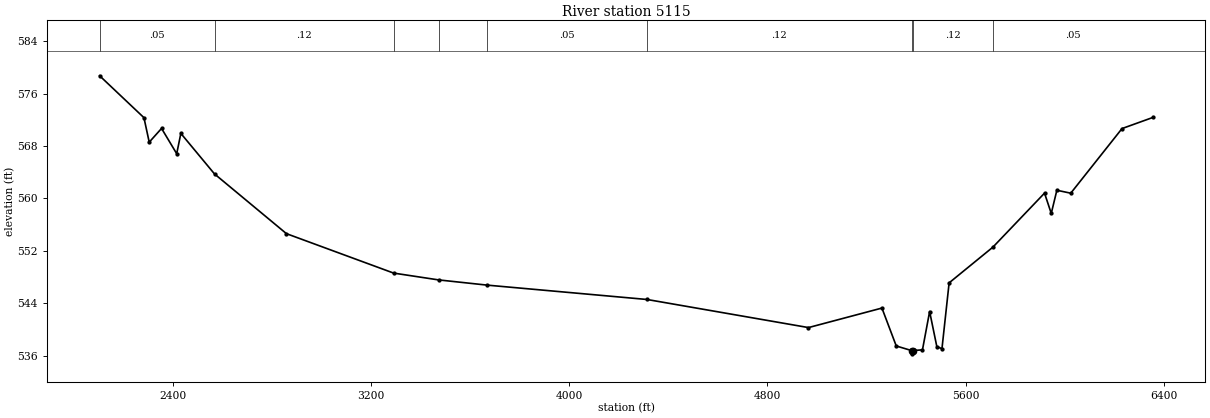
Type RM Length L Ch R = 1,5115,0,0,0
BEGIN DESCRIPTION:
Unnamed 1 8.0
END DESCRIPTION:
XS GIS Cut Line= 3
      2379157.19      7062600.97      2376429.00      7061610.00
      2375597.77      7062673.00
#Sta/Elev= 30
  2103.5  578.73  2282.4  572.33  2303.7  568.59  2353.5  570.69  2414.7  566.83
  2431.4  569.93  2567.3  563.74  2857.8  554.62  3290.5  548.60  3471.9  547.56
  3668.7  546.76  4313.6  544.57  4965.5  540.28  5262.0  543.26  5319.9  537.47
  5381.6  536.77  5382.2  536.27  5386.5  536.77  5425.7  536.88  5454.6  542.73
  5483.6  537.39  5504.4  537.05  5533.3  547.11  5710.0  552.56  5918.5  560.81
  5945.7  557.71  5968.3  561.25  6024.4  560.80  6231.4  570.67  6355.5  572.36
#Mann=9,-1,0
  2103.5    0.05       0  2567.3    0.12       0  3290.5    0.05       0
  3471.9    0.12       0  3668.7    0.05       0  4313.6    0.12       0
  5381.6    0.07       0  5386.5    0.12       0  5710.0    0.05       0
Bank Sta=5381.6,5386.5
Exp/Cntr=0.3,0.1

Chan Stop Cuts=-1