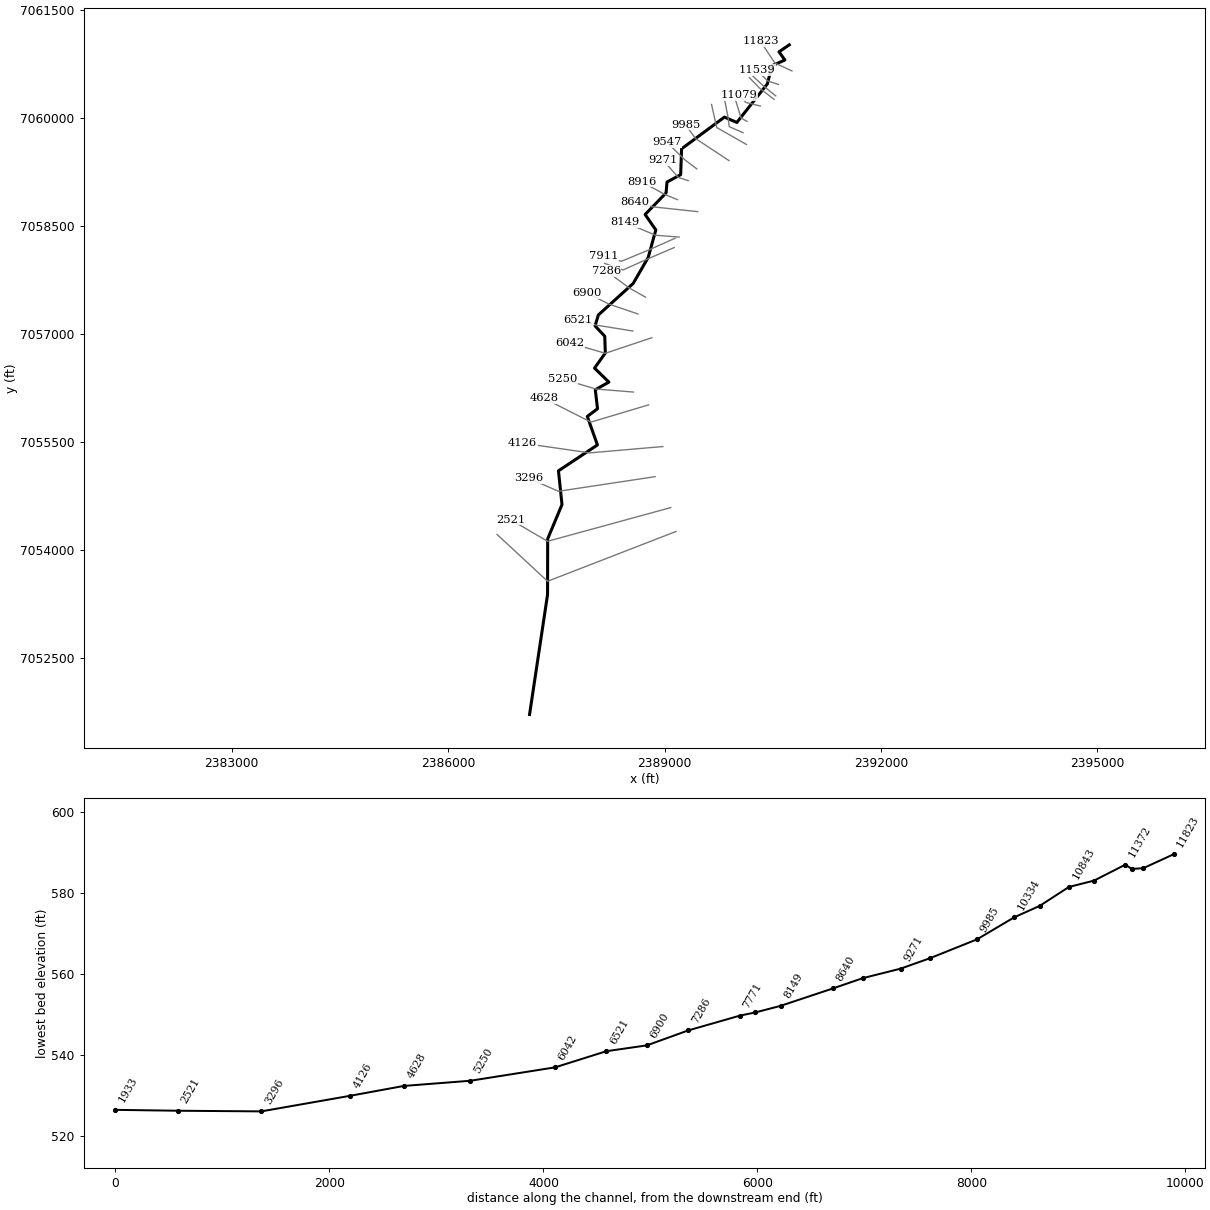
--- Unnamed 4.prj (project) ---

Proj Title=Unnamed 4 Base Level Engineering
Current Plan=p01
Default Exp/Contr=0.3,0.1
English Units
Geom File=g01
Flow File=f01
Plan File=p01
BEGIN DESCRIPTION:
Unnamed 4
END DESCRIPTION:

--- Unnamed 4.p01 (plan) ---

Plan Title=Multiple Run
Short Identifier=Multiple
Geom File=g01
Flow File=f01
Subcritical Flow
K Sum by GR= 0
Std Step Tol= 0.01
Critical Tol= 0.01
Num of Std Step Trials= 20
Max Error Tol= 0.3
Flow Tol Ratio= 0.001
Split Flow NTrial= 30
Split Flow Tol= 0.02
Split Flow Ratio= 0.02
Log Output Level= 0
Friction Slope Method= 1
Unsteady Friction Slope Method= 2
Unsteady Bridges Friction Slope Method= 1
Parabolic Critical Depth
Global Vel Dist=  1 , 1 , 1
Global Log Level= 0
CheckData=True
Encroach Param= -1, 0, 0, 0
BEGIN DESCRIPTION:
Multiple Run
END DESCRIPTION:

--- Unnamed 4.f01 (steady flow) ---

Flow Title=Multiple
Number of Profiles=7
Profile Names=10-year,25-year,50-year,1pct_min,100-year,1pct_plu,500-year
River Rch & RM= Unnamed 4,Reach-1,11823
     527     718     875     530    1057    2109    1546
River Rch & RM= Unnamed 4,Reach-1,9985
     717     992    1221     747    1490    2973    2223
River Rch & RM= Unnamed 4,Reach-1,5250
     866    1209    1498     921    1837    3665    2769
River Rch & RM= Unnamed 4,Reach-1,2521
     903    1264    1567     964    1923    3836    2903
Boundary for River Rch & Prof#=Unnamed 4,Reach-1,1
Up Type=0
Dn Type=3
Dn Slope=0.005
Boundary for River Rch & Prof#=Unnamed 4,Reach-1,2
Up Type=0
Dn Type=3
Dn Slope=0.005
Boundary for River Rch & Prof#=Unnamed 4,Reach-1,3
Up Type=0
Dn Type=3
Dn Slope=0.005
Boundary for River Rch & Prof#=Unnamed 4,Reach-1,4
Up Type=0
Dn Type=3
Dn Slope=0.005
Boundary for River Rch & Prof#=Unnamed 4,Reach-1,5
Up Type=0
Dn Type=3
Dn Slope=0.005
Boundary for River Rch & Prof#=Unnamed 4,Reach-1,6
Up Type=0
Dn Type=3
Dn Slope=0.005
Boundary for River Rch & Prof#=Unnamed 4,Reach-1,7
Up Type=0
Dn Type=3
Dn Slope=0.005

--- Unnamed 4.g01 (geometry) ---

Geom Title=Existing Conditions

River Reach=Unnamed 4,Reach-1
Reach XY= 30
      2390729.00      7061010.00      2390586.58      7060913.34
      2390668.19      7060799.63      2390489.33      7060720.17
      2390425.49      7060468.48      2390002.33      7059932.34
      2389830.35      7060006.66      2389236.35      7059566.38
      2389223.58      7059207.32      2389034.18      7059104.59
      2389021.26      7058953.54      2388730.59      7058653.95
      2388879.21      7058439.95      2388773.52      7058057.56
      2388565.61      7057696.67      2388082.55      7057258.70
      2388036.79      7057106.58      2388171.20      7056963.42
      2388179.30      7056730.34      2388029.59      7056520.62
      2388228.86      7056326.08      2388039.98      7056220.37
      2388071.28      7055956.34      2387929.45      7055849.18
      2388069.89      7055453.27      2387529.66      7055094.17
      2387578.62      7054625.27      2387380.20      7054149.50
      2387378.48      7053375.22      2387129.00      7051710.00

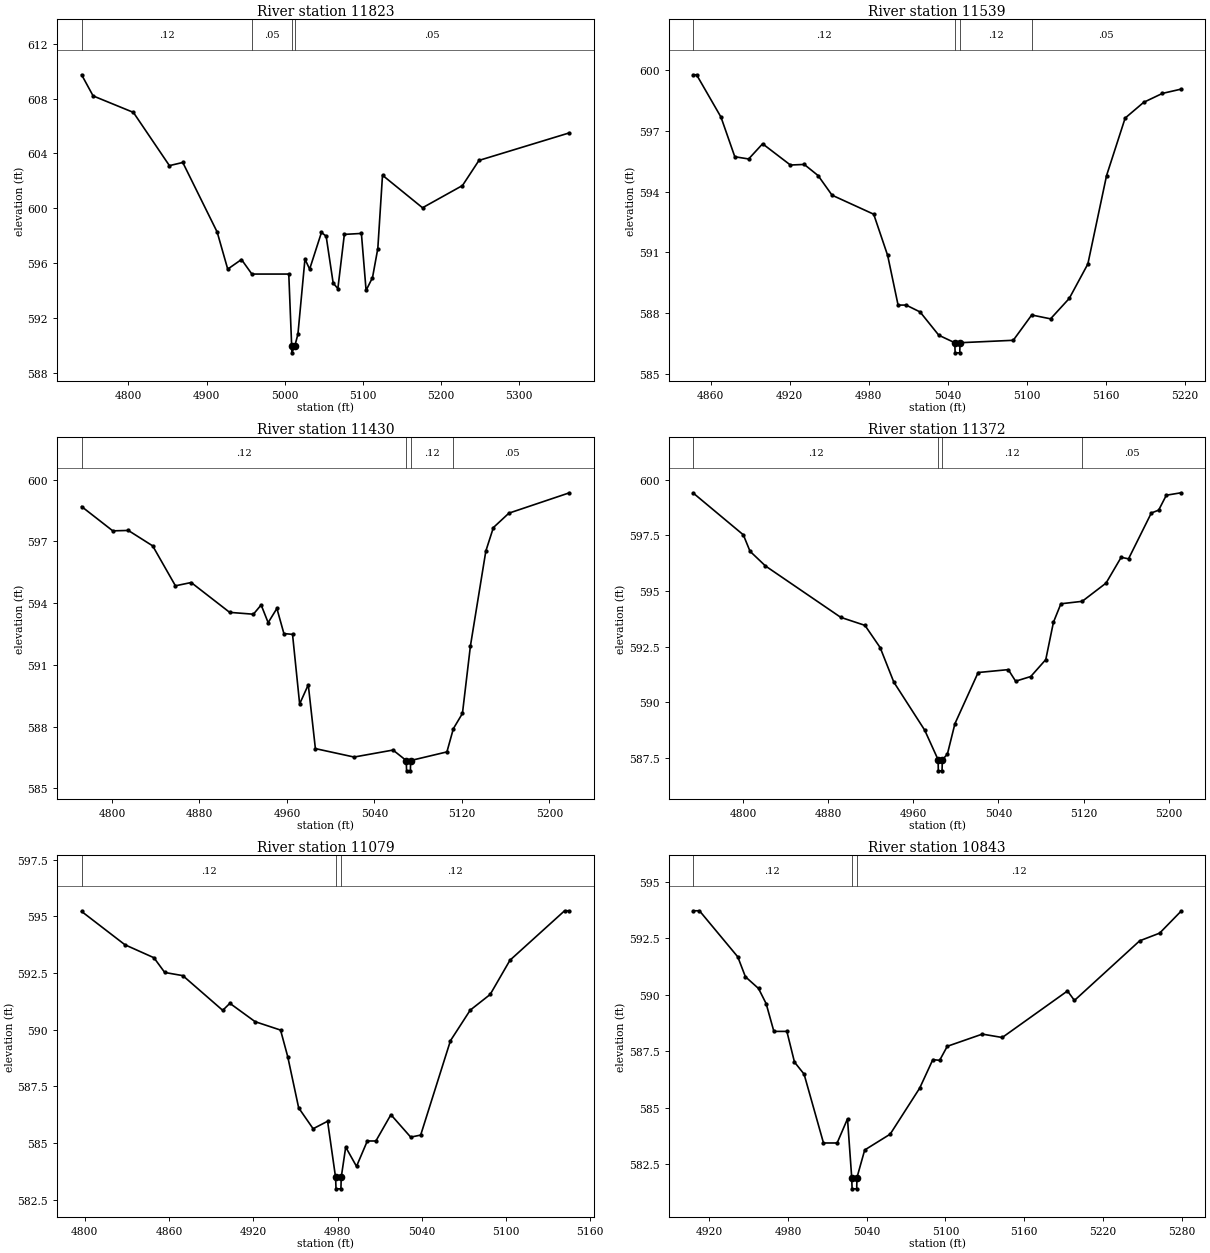
Type RM Length L Ch R = 1,11823,284,284,284
BEGIN DESCRIPTION:
Unnamed 4 30.0
END DESCRIPTION:
XS GIS Cut Line= 3
      2390766.72      7060648.63      2390530.26      7060756.49
      2390328.99      7061060.02
#Sta/Elev= 30
  4740.1  609.73  4754.8  608.19  4806.3  606.99  4852.4  603.11  4869.5  603.34
  4913.5  598.27  4927.0  595.57  4944.6  596.27  4957.9  595.21  5005.1  595.21
  5008.8  589.97  5009.0  589.47  5012.8  589.97  5016.8  590.83  5025.8  596.30
  5031.8  595.57  5046.9  598.24  5052.9  597.97  5061.9  594.55  5067.9  594.15
  5076.2  598.10  5098.0  598.17  5104.0  594.02  5112.2  594.95  5119.0  597.07
  5125.0  602.41  5176.2  600.04  5227.3  601.66  5248.4  603.49  5364.2  605.50
#Mann=4,-1,0
  4740.1    0.12       0  4957.9    0.05       0  5008.8   0.033       0
  5012.8    0.05       0
Bank Sta=5008.8,5012.8
Exp/Cntr=0.3,0.1

Type RM Length L Ch R = 1,11539,109,109,109
BEGIN DESCRIPTION:
Unnamed 4 29.0
END DESCRIPTION:
XS GIS Cut Line= 3
      2390578.98      7060460.01      2390429.00      7060510.00
      2390279.02      7060659.98
#Sta/Elev= 30
  4846.8  599.78  4849.4  599.78  4867.9  597.69  4878.4  595.73  4888.9  595.62
  4899.5  596.37  4920.6  595.32  4931.1  595.35  4941.6  594.80  4952.2  593.83
  4983.8  592.89  4994.4  590.85  5002.3  588.40  5008.4  588.40  5019.0  588.06
  5033.2  586.91  5045.3  586.54  5045.6  586.04  5049.1  586.04  5049.3  586.54
  5089.7  586.66  5103.7  587.91  5118.0  587.72  5132.2  588.73  5146.3  590.43
  5160.5  594.80  5174.6  597.64  5188.7  598.42  5202.9  598.86  5217.0  599.07
#Mann=4,-1,0
  4846.8    0.12       0  5045.3    0.07       0  5049.3    0.12       0
  5103.7    0.05       0
Bank Sta=5045.3,5049.3
Exp/Cntr=0.3,0.1

Type RM Length L Ch R = 1,11430,58,58,58
BEGIN DESCRIPTION:
Mapping XS 5d034f8b
END DESCRIPTION:
XS GIS Cut Line= 3
      2390541.14      7060301.33      2390363.54      7060445.08
      2390205.23      7060594.53
#Sta/Elev= 30
  4772.2  598.69  4800.7  597.51  4814.9  597.53  4837.2  596.78  4858.0  594.84
  4872.4  595.00  4907.6  593.55  4929.3  593.46  4936.4  593.91  4942.8  593.05
  4950.8  593.74  4957.2  592.52  4965.1  592.48  4971.6  589.10  4979.5  590.03
  4986.0  586.93  5021.4  586.52  5057.0  586.86  5069.1  586.35  5069.4  585.85
  5072.9  585.85  5073.1  586.35  5106.3  586.77  5112.2  587.90  5120.5  588.64
  5127.8  591.92  5141.9  596.53  5148.8  597.67  5163.0  598.37  5218.4  599.36
#Mann=4,-1,0
  4772.2    0.12       0  5069.1    0.07       0  5073.1    0.12       0
  5112.2    0.05       0
Bank Sta=5069.1,5073.1
Exp/Cntr=0.3,0.1

Type RM Length L Ch R = 1,11372,293,293,293
BEGIN DESCRIPTION:
Unnamed 4 28.0
END DESCRIPTION:
XS GIS Cut Line= 3
      2390518.24      7060253.92      2390322.62      7060404.23
      2390175.48      7060556.02
#Sta/Elev= 30
  4753.3  599.41  4800.4  597.53  4806.7  596.79  4821.2  596.13  4891.9  593.82
  4914.6  593.46  4928.9  592.46  4941.7  590.91  4970.7  588.75  4983.3  587.42
  4983.5  586.92  4987.0  586.92  4987.3  587.42  4992.0  587.67  4999.1  589.04
  5020.9  591.34  5049.2  591.47  5056.1  590.95  5070.3  591.16  5084.4  591.92
  5091.6  593.60  5098.6  594.43  5118.6  594.54  5141.0  595.36  5155.2  596.52
  5162.1  596.45  5183.5  598.51  5190.4  598.64  5197.6  599.31  5211.4  599.42
#Mann=4,-1,0
  4753.3    0.12       0  4983.3    0.07       0  4987.3    0.12       0
  5118.6    0.05       0
Bank Sta=4983.3,4987.3
Exp/Cntr=0.3,0.1

Type RM Length L Ch R = 1,11079,236,236,236
BEGIN DESCRIPTION:
Unnamed 4 27.0
END DESCRIPTION:
XS GIS Cut Line= 3
      2390328.96      7060160.01      2390129.00      7060210.00
      2390029.02      7060309.98
#Sta/Elev= 30
  4797.7  595.21  4828.6  593.74  4849.2  593.17  4856.9  592.52  4869.8  592.38
  4898.2  590.85  4903.3  591.16  4921.3  590.35  4939.4  589.98  4944.5  588.81
  4952.3  586.55  4962.6  585.63  4972.9  585.96  4978.6  583.48  4978.9  582.98
  4982.4  582.98  4982.6  583.48  4985.8  584.82  4993.5  583.97  5001.2  585.09
  5007.3  585.09  5018.0  586.25  5032.1  585.26  5039.2  585.35  5060.4  589.51
  5074.5  590.86  5088.7  591.55  5102.8  593.06  5141.7  595.24  5145.2  595.24
#Mann=3,-1,0
  4797.7    0.12       0  4978.6    0.07       0  4982.6    0.12       0
Bank Sta=4978.6,4982.6
Exp/Cntr=0.3,0.1

Type RM Length L Ch R = 1,10843,271,271,271
BEGIN DESCRIPTION:
Unnamed 4 26.0
END DESCRIPTION:
XS GIS Cut Line= 3
      2390142.39      7059947.47      2390062.36      7059993.25
      2389978.99      7060260.03
#Sta/Elev= 30
  4907.8  593.71  4912.6  593.71  4941.8  591.67  4947.6  590.79  4957.6  590.27
  4963.4  589.60  4969.3  588.37  4979.2  588.37  4985.0  587.01  4992.3  586.48
  5007.1  583.43  5017.5  583.43  5025.4  584.50  5028.6  581.90  5028.9  581.40
  5032.4  581.40  5032.6  581.90  5038.5  583.12  5057.9  583.82  5080.4  585.86
  5090.4  587.12  5095.6  587.09  5101.4  587.71  5128.1  588.25  5143.3  588.10
  5193.0  590.16  5198.3  589.74  5248.0  592.38  5263.2  592.72  5279.5  593.69
#Mann=3,-1,0
  4907.8    0.12       0  5028.6    0.07       0  5032.6    0.12       0
Bank Sta=5028.6,5032.6
Exp/Cntr=0.3,0.1

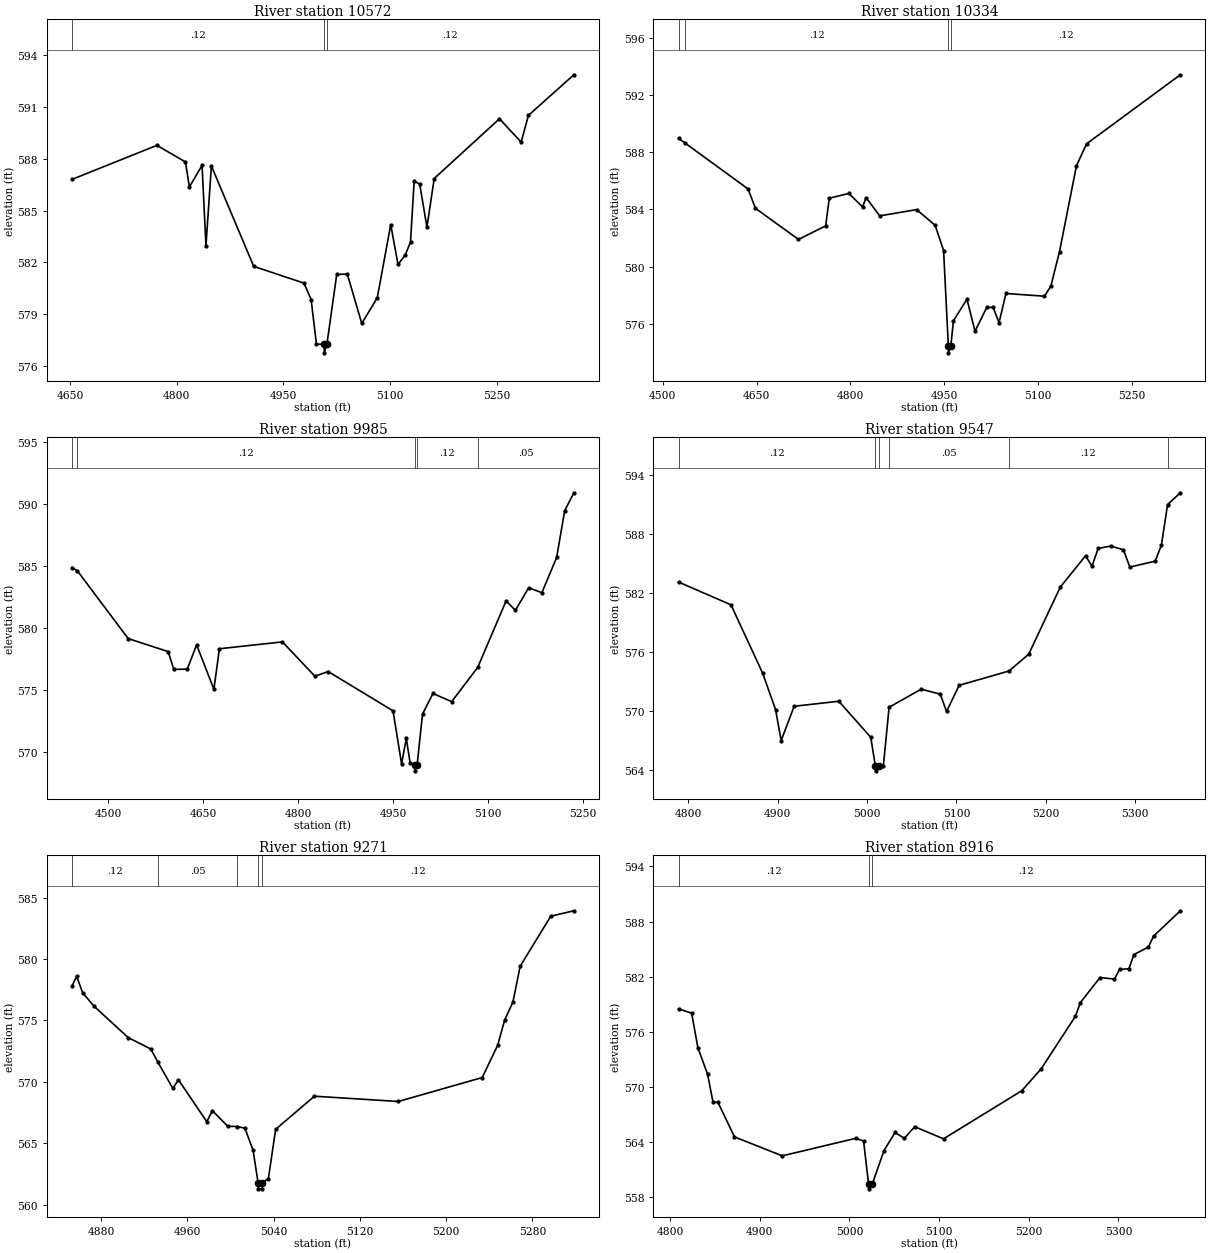
Type RM Length L Ch R = 1,10572,238,238,238
BEGIN DESCRIPTION:
Unnamed 4 25.0
END DESCRIPTION:
XS GIS Cut Line= 4
      2390088.05      7059789.74      2389896.65      7059874.37
      2389879.00      7060010.00      2389810.99      7060362.75
#Sta/Elev= 30
  4652.9  586.81  4772.1  588.78  4812.3  587.82  4817.8  586.37  4835.6  587.62
  4841.1  582.97  4848.7  587.59  4908.2  581.77  4978.8  580.80  4988.9  579.85
  4996.4  577.26  5007.1  577.26  5007.4  576.76  5011.1  577.26  5024.9  581.30
  5039.7  581.33  5060.1  578.46  5081.9  579.95  5100.8  584.19  5111.0  581.88
  5121.2  582.43  5128.6  583.18  5133.7  586.70  5141.5  586.54  5151.7  584.04
  5161.9  586.86  5253.6  590.32  5284.1  588.97  5294.4  590.52  5358.2  592.87
#Mann=3,-1,0
  4652.9    0.12       0  5007.1    0.07       0  5011.1    0.12       0
Bank Sta=5007.1,5011.1
Exp/Cntr=0.3,0.1

Type RM Length L Ch R = 1,10334,349,349,349
BEGIN DESCRIPTION:
Unnamed 4 24.0
END DESCRIPTION:
XS GIS Cut Line= 3
      2390135.61      7059626.64      2389723.29      7059862.08
      2389651.27      7060182.17
#Sta/Elev= 30
  4525.2  588.98  4536.1  588.64  4636.4  585.44  4648.3  584.08  4717.1  581.90
  4760.6  582.85  4766.4  584.79  4797.7  585.12  4819.7  584.18  4825.4  584.83
  4847.0  583.55  4906.1  583.99  4935.8  582.89  4949.3  581.12  4956.9  574.45
  4957.1  573.95  4960.9  574.45  4965.1  576.20  4986.7  577.71  4999.6  575.47
  5018.4  577.13  5028.6  577.14  5038.0  576.06  5049.1  578.11  5110.6  577.92
  5120.9  578.62  5134.8  581.05  5161.9  587.06  5178.1  588.60  5328.1  593.44
#Mann=4,-1,0
  4525.2    0.05       0  4536.1    0.12       0  4956.9    0.07       0
  4960.9    0.12       0
Bank Sta=4956.9,4960.9
Exp/Cntr=0.3,0.1

Type RM Length L Ch R = 1,9985,438,438,438
BEGIN DESCRIPTION:
Unnamed 4 23.0
END DESCRIPTION:
XS GIS Cut Line= 3
      2389893.08      7059402.96      2389428.71      7059710.00
      2389291.58      7059901.82
#Sta/Elev= 30
  4443.3  584.90  4451.7  584.63  4531.9  579.17  4595.0  578.12  4604.0  576.69
  4625.2  576.70  4640.0  578.66  4667.3  575.08  4676.0  578.35  4775.6  578.90
  4826.8  576.13  4847.8  576.51  4950.2  573.34  4963.7  569.07  4971.2  571.11
  4977.2  569.13  4984.3  569.00  4984.6  568.50  4988.3  569.00  4996.8  573.08
  5013.3  574.74  5042.8  574.08  5083.9  576.84  5128.8  582.21  5143.5  581.45
  5164.4  583.27  5185.3  582.87  5208.6  585.71  5221.3  589.48  5235.8  590.93
#Mann=5,-1,0
  4443.3    0.05       0  4451.7    0.12       0  4984.3    0.07       0
  4988.3    0.12       0  5083.9    0.05       0
Bank Sta=4984.3,4988.3
Exp/Cntr=0.3,0.1

Type RM Length L Ch R = 1,9547,276,276,276
BEGIN DESCRIPTION:
Unnamed 4 22.0
END DESCRIPTION:
XS GIS Cut Line= 3
      2389447.83      7059287.24      2389279.80      7059415.03
      2389028.99      7059660.01
#Sta/Elev= 30
  4788.9  583.08  4847.6  580.76  4883.0  573.82  4897.5  570.11  4903.8  566.95
  4918.3  570.44  4968.3  570.95  5004.1  567.28  5009.2  564.37  5009.4  563.87
  5013.2  564.37  5018.2  564.38  5024.6  570.34  5060.6  572.18  5081.9  571.67
  5088.9  569.91  5103.0  572.57  5158.9  574.03  5180.9  575.74  5216.2  582.56
  5244.5  585.75  5251.7  584.69  5258.6  586.50  5272.8  586.74  5286.9  586.36
  5294.1  584.60  5322.4  585.20  5329.4  586.82  5336.3  590.96  5350.6  592.16
#Mann=6,-1,0
  4788.9    0.12       0  5009.2    0.07       0  5013.2    0.12       0
  5024.6    0.05       0  5158.9    0.12       0  5336.3    0.05       0
Bank Sta=5009.2,5013.2
Exp/Cntr=0.3,0.1

Type RM Length L Ch R = 1,9271,355,355,355
BEGIN DESCRIPTION:
Unnamed 4 21.0
END DESCRIPTION:
XS GIS Cut Line= 3
      2389328.29      7059123.78      2389189.05      7059170.61
      2388978.99      7059410.01
#Sta/Elev= 30
  4853.1  577.81  4857.3  578.60  4862.9  577.26  4873.5  576.16  4905.1  573.61
  4926.2  572.67  4932.4  571.65  4946.5  569.47  4951.8  570.16  4978.0  566.76
  4983.3  567.65  4997.4  566.38  5006.4  566.36  5013.4  566.22  5021.0  564.42
  5025.6  561.78  5025.9  561.28  5029.4  561.28  5029.6  561.78  5035.2  562.12
  5041.9  566.13  5077.9  568.83  5155.7  568.40  5233.5  570.35  5247.8  572.97
  5254.4  575.06  5262.0  576.50  5268.7  579.42  5297.1  583.50  5318.5  583.94
#Mann=5,-1,0
  4853.1    0.12       0  4932.4    0.05       0  5006.4    0.12       0
  5025.6   0.033       0  5029.6    0.12       0
Bank Sta=5025.6,5029.6
Exp/Cntr=0.3,0.1

Type RM Length L Ch R = 1,8916,276,276,276
BEGIN DESCRIPTION:
Unnamed 4 20.0
END DESCRIPTION:
XS GIS Cut Line= 3
      2389178.97      7058860.01      2389002.83      7058932.85
      2388679.02      7059109.99
#Sta/Elev= 30
  4809.4  578.51  4824.0  578.04  4831.0  574.28  4841.8  571.40  4847.9  568.34
  4853.3  568.36  4871.8  564.58  4925.1  562.52  5007.3  564.43  5015.8  564.12
  5021.4  559.43  5021.6  558.93  5025.4  559.43  5038.6  563.10  5050.9  565.06
  5061.3  564.42  5072.8  565.69  5105.0  564.37  5192.2  569.60  5214.0  572.00
  5252.0  577.69  5257.7  579.20  5279.5  581.92  5295.6  581.75  5301.3  582.80
  5311.7  582.87  5317.4  584.42  5333.5  585.23  5339.2  586.42  5369.1  589.18
#Mann=3,-1,0
  4809.4    0.12       0  5021.4    0.07       0  5025.4    0.12       0
Bank Sta=5021.4,5025.4
Exp/Cntr=0.3,0.1

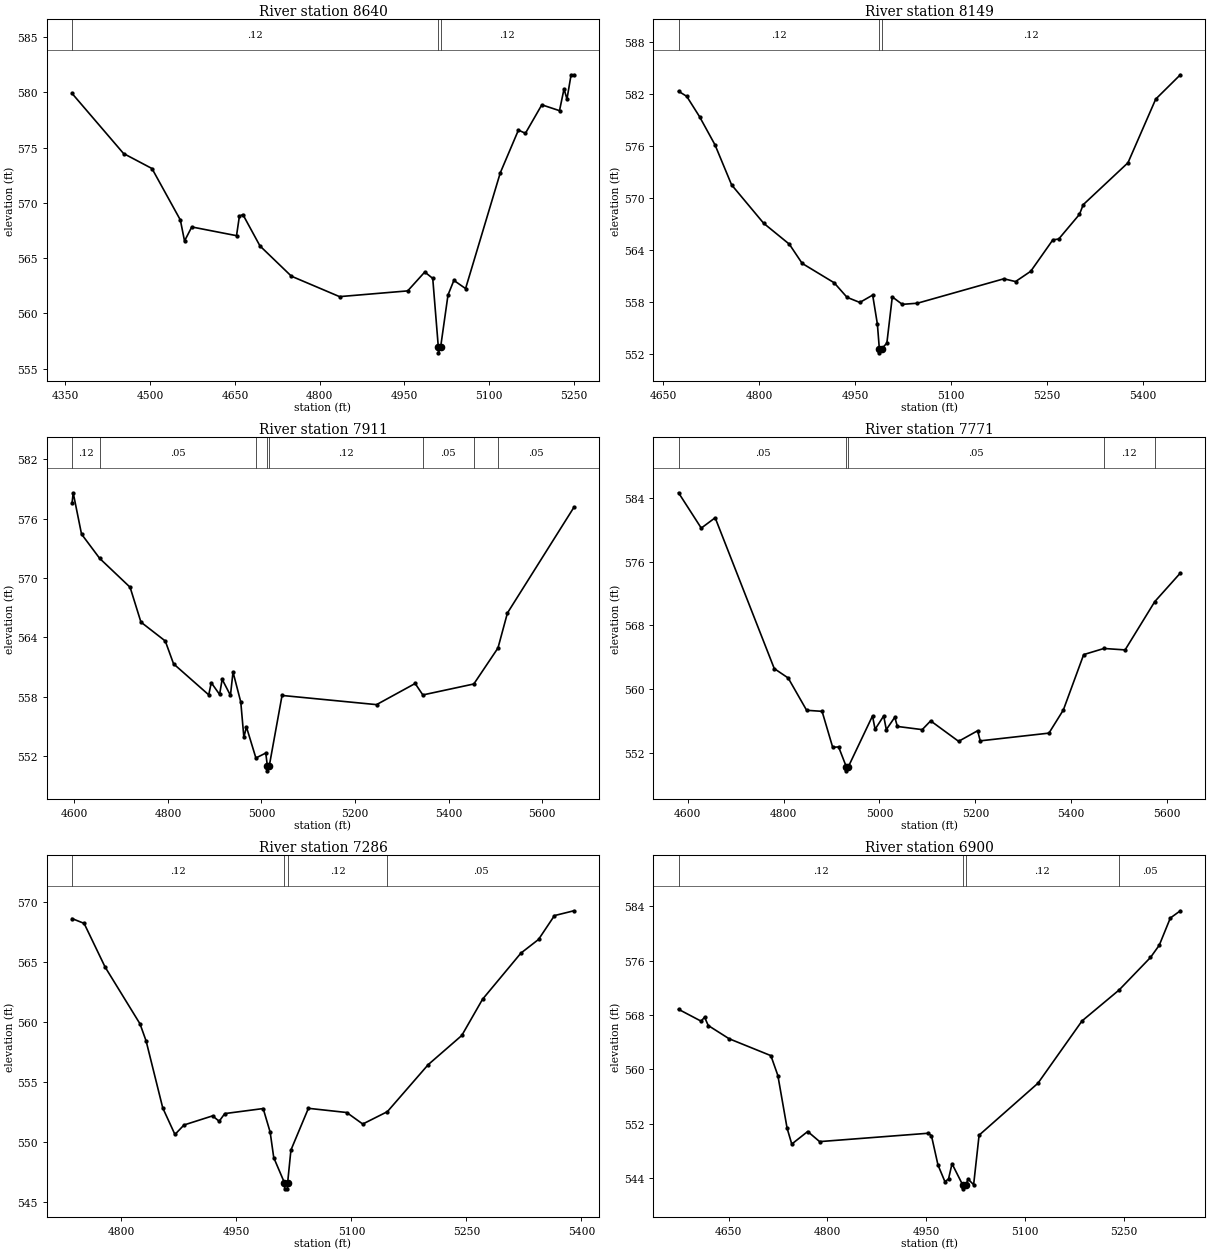
Type RM Length L Ch R = 1,8640,491,491,491
BEGIN DESCRIPTION:
Unnamed 4 19.0
END DESCRIPTION:
XS GIS Cut Line= 3
      2389459.55      7058693.50      2388825.00      7058761.68
      2388584.53      7058828.92
#Sta/Elev= 30
  4361.8  579.91  4452.9  574.47  4503.2  573.11  4553.4  568.45  4560.8  566.55
  4573.6  567.82  4652.8  567.03  4657.9  568.80  4664.1  568.94  4694.3  566.10
  4749.9  563.36  4835.1  561.51  4955.7  562.03  4985.9  563.74  5000.0  563.16
  5009.9  556.92  5010.1  556.42  5013.9  556.92  5027.0  561.66  5037.4  562.98
  5058.1  562.24  5119.5  572.72  5151.6  576.59  5164.0  576.30  5193.0  578.88
  5224.3  578.35  5232.3  580.32  5237.5  579.40  5244.8  581.60  5249.7  581.60
#Mann=3,-1,0
  4361.8    0.12       0  5009.9    0.07       0  5013.9    0.12       0
Bank Sta=5009.9,5013.9
Exp/Cntr=0.3,0.1

Type RM Length L Ch R = 1,8149,238,238,238
BEGIN DESCRIPTION:
Unnamed 4 18.0
END DESCRIPTION:
XS GIS Cut Line= 3
      2389201.77      7058340.63      2388876.86      7058365.97
      2388453.50      7058543.56
#Sta/Elev= 30
  4674.1  582.32  4686.9  581.73  4707.0  579.38  4731.2  576.12  4757.1  571.51
  4807.3  567.07  4847.4  564.66  4867.5  562.44  4917.6  560.20  4937.7  558.52
  4957.7  557.93  4977.8  558.78  4985.2  555.42  4988.2  552.61  4988.4  552.11
  4992.2  552.61  5000.0  553.23  5008.5  558.57  5024.1  557.71  5047.8  557.84
  5183.0  560.66  5201.3  560.34  5225.1  561.53  5259.7  565.16  5268.8  565.25
  5301.3  568.10  5307.2  569.22  5377.2  574.06  5420.6  581.41  5459.1  584.22
#Mann=3,-1,0
  4674.1    0.12       0  4988.2    0.07       0  4992.2    0.12       0
Bank Sta=4988.2,4992.2
Exp/Cntr=0.3,0.1

Type RM Length L Ch R = 1,7911,140,140,140
BEGIN DESCRIPTION:
Mapping XS 156d9d3f
END DESCRIPTION:
XS GIS Cut Line= 4
      2389148.37      7058325.02      2388778.67      7058160.14
      2388400.97      7058003.81      2388153.10      7058078.66
#Sta/Elev= 30
  4595.2  577.58  4597.6  578.62  4615.4  574.44  4654.2  571.98  4719.2  569.06
  4742.4  565.53  4794.4  563.62  4812.1  561.31  4887.3  558.17  4892.7  559.40
  4910.5  558.21  4916.0  559.74  4933.7  558.12  4939.2  560.48  4955.8  557.44
  4962.4  553.87  4967.9  554.92  4988.1  551.78  5009.2  552.28  5012.6  550.98
  5012.9  550.48  5016.7  550.98  5044.0  558.11  5246.0  557.18  5328.5  559.32
  5344.9  558.16  5453.9  559.27  5505.5  562.91  5525.7  566.45  5667.7  577.14
#Mann=8,-1,0
  4595.2    0.12       0  4654.2    0.05       0  4988.1    0.12       0
  5012.6    0.07       0  5016.7    0.12       0  5344.9    0.05       0
  5453.9    0.12       0  5505.5    0.05       0
Bank Sta=5012.6,5016.7
Exp/Cntr=0.3,0.1

Type RM Length L Ch R = 1,7771,485,485,485
BEGIN DESCRIPTION:
Unnamed 4 17.0
END DESCRIPTION:
XS GIS Cut Line= 4
      2389134.61      7058194.97      2388749.42      7058029.83
      2388425.65      7057883.57      2388169.11      7057974.96
#Sta/Elev= 30
  4580.9  584.67  4628.3  580.23  4657.3  581.53  4780.6  562.57  4809.6  561.39
  4848.1  557.33  4880.3  557.20  4902.5  552.67  4914.8  552.73  4930.9  550.22
  4931.2  549.72  4935.0  550.22  4985.5  556.62  4990.9  554.94  5008.8  556.62
  5014.3  554.90  5032.0  556.46  5037.4  555.30  5089.2  554.90  5106.8  556.00
  5165.1  553.43  5204.8  554.76  5210.2  553.49  5353.5  554.46  5383.6  557.37
  5426.0  564.33  5468.2  565.10  5512.4  564.92  5574.3  570.99  5627.6  574.58
#Mann=5,-1,0
  4580.9    0.05       0  4930.9    0.05       0  4935.0    0.05       0
  5468.2    0.12       0  5574.3    0.05       0
Bank Sta=4930.9,4935
Exp/Cntr=0.3,0.1

Type RM Length L Ch R = 1,7286,386,386,386
BEGIN DESCRIPTION:
Unnamed 4 16.0
END DESCRIPTION:
XS GIS Cut Line= 3
      2388736.21      7057506.44      2388505.88      7057636.27
      2388193.25      7057869.76
#Sta/Elev= 30
  4735.6  568.58  4751.3  568.18  4778.7  564.54  4824.2  559.81  4832.2  558.38
  4853.9  552.80  4869.8  550.59  4881.6  551.38  4918.9  552.14  4927.5  551.69
  4934.8  552.33  4984.9  552.75  4994.0  550.79  4998.7  548.66  5012.7  546.56
  5013.0  546.06  5016.5  546.06  5016.8  546.56  5021.1  549.29  5043.9  552.77
  5093.9  552.42  5114.8  551.46  5146.9  552.49  5200.2  556.41  5244.0  558.84
  5271.1  561.86  5321.1  565.70  5344.1  566.84  5364.9  568.83  5390.2  569.23
#Mann=4,-1,0
  4735.6    0.12       0  5012.7    0.07       0  5016.8    0.12       0
  5146.9    0.05       0
Bank Sta=5012.7,5016.8
Exp/Cntr=0.3,0.1

Type RM Length L Ch R = 1,6900,379,379,379
BEGIN DESCRIPTION:
Unnamed 4 15.0
END DESCRIPTION:
XS GIS Cut Line= 3
      2388631.68      7057272.30      2388229.00      7057410.00
      2387928.55      7057560.93
#Sta/Elev= 30
  4574.0  568.84  4608.3  567.09  4613.5  567.68  4619.1  566.45  4650.8  564.50
  4714.2  562.01  4724.8  559.08  4738.8  551.32  4745.9  548.98  4770.1  550.83
  4788.2  549.34  4952.6  550.57  4957.9  550.24  4967.9  545.89  4978.4  543.44
  4983.9  543.84  4989.2  546.08  5005.8  542.88  5006.2  542.38  5010.0  542.88
  5013.5  543.82  5022.0  542.99  5030.3  550.29  5119.6  557.94  5186.6  567.13
  5242.8  571.68  5290.5  576.48  5303.8  578.28  5320.6  582.29  5335.8  583.36
#Mann=4,-1,0
  4574.0    0.12       0  5005.8    0.07       0  5010.0    0.12       0
  5242.8    0.05       0
Bank Sta=5005.8,5010
Exp/Cntr=0.3,0.1

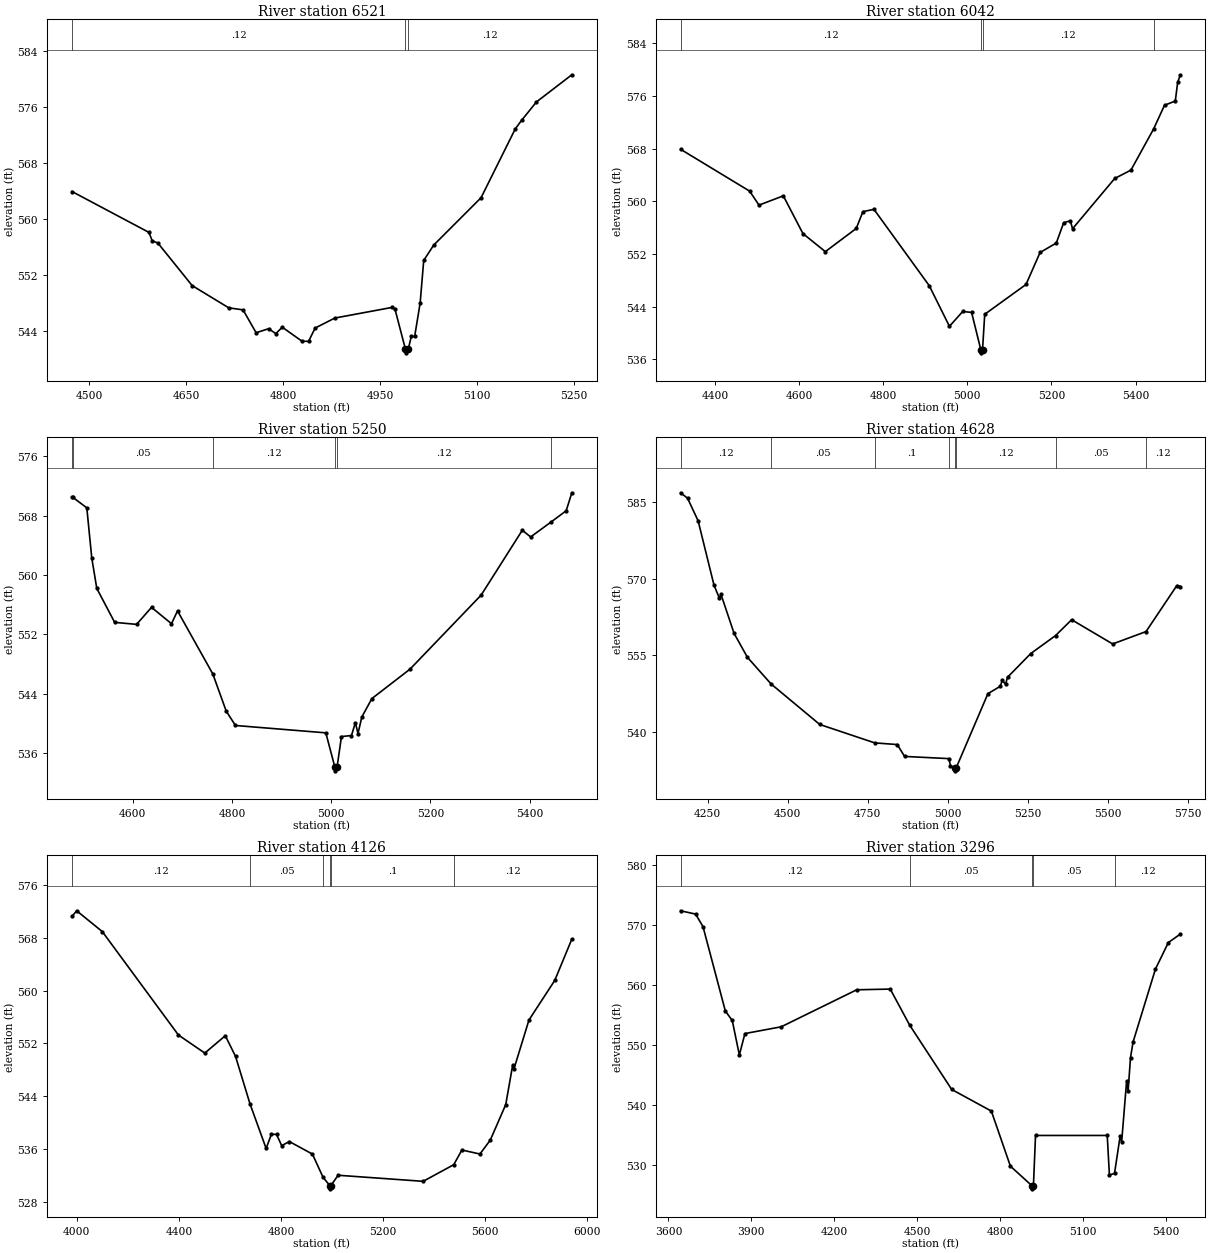
Type RM Length L Ch R = 1,6521,479,479,479
BEGIN DESCRIPTION:
Unnamed 4 14.0
END DESCRIPTION:
XS GIS Cut Line= 3
      2388560.07      7057035.76      2388040.32      7057119.85
      2387804.83      7057192.01
#Sta/Elev= 30
  4473.5  563.99  4592.5  558.15  4597.6  556.94  4606.3  556.63  4659.3  550.55
  4715.9  547.37  4738.0  547.08  4758.2  543.81  4777.6  544.39  4788.6  543.69
  4798.7  544.60  4829.1  542.60  4839.3  542.58  4849.4  544.48  4879.8  545.91
  4967.8  547.42  4972.8  547.21  4989.1  541.44  4989.4  540.94  4993.3  541.44
  4998.1  543.28  5003.3  543.28  5011.8  548.06  5017.3  554.14  5032.8  556.34
  5106.0  563.11  5158.8  572.93  5168.7  574.17  5191.6  576.79  5246.3  580.67
#Mann=3,-1,0
  4473.5    0.12       0  4989.1    0.07       0  4993.3    0.12       0
Bank Sta=4989.1,4993.3
Exp/Cntr=0.3,0.1

Type RM Length L Ch R = 1,6042,792,792,792
BEGIN DESCRIPTION:
Unnamed 4 13.0
END DESCRIPTION:
XS GIS Cut Line= 3
      2388824.80      7056942.97      2388178.75      7056726.02
      2387692.73      7056868.57
#Sta/Elev= 30
  4318.5  567.90  4482.8  561.53  4504.9  559.41  4562.7  560.82  4609.4  555.08
  4662.6  552.34  4736.0  555.86  4751.9  558.42  4778.1  558.77  4909.5  547.17
  4957.5  540.99  4989.2  543.25  5010.2  543.10  5032.0  537.46  5032.3  536.96
  5036.2  537.46  5041.4  542.82  5139.5  547.35  5172.9  552.21  5211.5  553.65
  5229.0  556.73  5244.9  557.04  5250.1  555.82  5350.3  563.46  5388.9  564.73
  5442.9  571.00  5468.7  574.59  5494.3  575.23  5500.0  578.09  5506.5  579.22
#Mann=4,-1,0
  4318.5    0.12       0  5032.0    0.07       0  5036.2    0.12       0
  5442.9    0.05       0
Bank Sta=5032,5036.2
Exp/Cntr=0.3,0.1

Type RM Length L Ch R = 1,5250,622,622,622
BEGIN DESCRIPTION:
Unnamed 4 11.0
END DESCRIPTION:
XS GIS Cut Line= 3
      2388568.81      7056187.93      2388048.14      7056230.42
      2387583.36      7056368.30
#Sta/Elev= 30
  4477.6  570.47  4478.9  570.47  4507.5  569.03  4517.5  562.28  4527.6  558.20
  4563.6  553.63  4607.8  553.36  4637.9  555.65  4678.1  553.45  4690.3  555.17
  4761.4  546.69  4788.4  541.69  4807.0  539.76  4989.1  538.77  5007.3  534.16
  5007.7  533.66  5011.8  534.16  5020.6  538.27  5040.8  538.41  5048.7  540.14
  5053.9  538.68  5061.7  540.91  5081.9  543.38  5158.8  547.34  5302.1  557.30
  5385.0  566.02  5401.8  565.12  5442.4  567.10  5473.4  568.64  5484.8  571.06
#Mann=6,-1,0
  4477.6    0.12       0  4478.9    0.05       0  4761.4    0.12       0
  5007.3    0.07       0  5011.8    0.12       0  5442.4    0.05       0
Bank Sta=5007.3,5011.8
Exp/Cntr=0.3,0.1

Type RM Length L Ch R = 1,4628,502,502,502
BEGIN DESCRIPTION:
Unnamed 4 10.0
END DESCRIPTION:
XS GIS Cut Line= 3
      2388779.03      7056010.01      2387979.52      7055770.54
      2387332.37      7056099.37
#Sta/Elev= 30
  4165.4  586.77  4187.2  585.71  4220.3  581.27  4269.8  568.70  4286.4  566.18
  4291.7  566.88  4332.5  559.26  4374.2  554.58  4448.0  549.37  4599.9  541.45
  4771.4  537.85  4841.9  537.52  4864.8  535.20  5002.9  534.77  5008.0  533.41
  5020.7  532.88  5021.2  532.38  5025.3  532.88  5124.9  547.47  5163.8  548.93
  5169.4  550.07  5180.1  549.32  5186.1  550.68  5258.6  555.32  5336.1  558.84
  5386.3  561.94  5514.3  557.20  5618.5  559.62  5714.6  568.61  5725.9  568.43
#Mann=8,-1,0
  4165.4    0.12       0  4448.0    0.05       0  4771.4     0.1       0
  5002.9    0.12       0  5020.7    0.07       0  5025.3    0.12       0
  5336.1    0.05       0  5618.5    0.12       0
Bank Sta=5020.7,5025.3
Exp/Cntr=0.3,0.1

Type RM Length L Ch R = 1,4126,830,830,830
BEGIN DESCRIPTION:
Unnamed 4 8.0
END DESCRIPTION:
XS GIS Cut Line= 3
      2388977.48      7055431.33      2387962.42      7055342.99
      2387032.78      7055478.09
#Sta/Elev= 30
  3981.1  571.27  3999.6  572.12  4100.0  568.96  4398.1  553.28  4501.5  550.54
  4581.8  553.17  4622.0  550.03  4678.6  542.83  4741.8  536.07  4762.5  538.24
  4782.6  538.20  4802.7  536.50  4832.8  537.12  4923.1  535.22  4964.8  531.70
  4991.1  530.45  4991.5  529.95  4995.7  530.45  5023.7  532.01  5356.9  531.09
  5476.7  533.61  5508.7  535.84  5579.4  535.23  5619.9  537.34  5680.5  542.73
  5707.5  548.68  5712.6  548.13  5771.4  555.55  5872.5  561.56  5939.4  567.82
#Mann=6,-1,0
  3981.1    0.12       0  4678.6    0.05       0  4964.8     0.1       0
  4991.1    0.07       0  4995.7     0.1       0  5476.7    0.12       0
Bank Sta=4991.1,4995.7
Exp/Cntr=0.3,0.1

Type RM Length L Ch R = 1,3296,775,775,775
BEGIN DESCRIPTION:
Unnamed 4 7.0
END DESCRIPTION:
XS GIS Cut Line= 3
      2388869.40      7055012.93      2387529.00      7054810.00
      2387113.55      7054992.40
#Sta/Elev= 30
  3643.9  572.42  3698.4  571.87  3725.2  569.77  3806.1  555.71  3831.0  554.15
  3856.7  548.41  3876.9  551.97  4008.4  553.10  4281.5  559.26  4402.9  559.38
  4473.0  553.39  4625.4  542.66  4768.9  539.06  4837.8  529.89  4916.2  526.61
  4916.8  526.11  4921.2  526.61  4928.8  535.00  5188.4  535.00  5196.2  528.42
  5214.7  528.67  5235.1  534.90  5240.6  533.94  5258.5  544.05  5264.0  542.43
  5272.6  547.97  5281.9  550.57  5362.9  562.71  5409.6  567.13  5453.3  568.55
#Mann=5,-1,0
  3643.9    0.12       0  4473.0    0.05       0  4916.2   0.033       0
  4921.2    0.05       0  5214.7    0.12       0
Bank Sta=4916.2,4921.2
Exp/Cntr=0.3,0.1

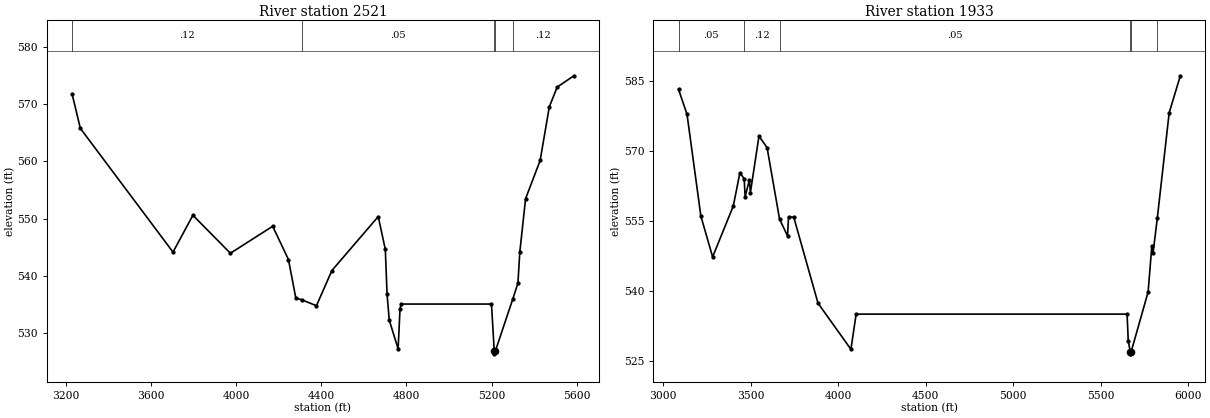
Type RM Length L Ch R = 1,2521,588,588,588
BEGIN DESCRIPTION:
Unnamed 4 5.0
END DESCRIPTION:
XS GIS Cut Line= 3
      2389086.47      7054583.26      2387378.55      7054115.18
      2386872.33      7054412.16
#Sta/Elev= 30
  3229.1  571.86  3268.0  565.81  3703.4  544.11  3796.8  550.57  3973.0  543.91
  4171.8  548.64  4245.9  542.80  4280.4  536.06  4309.2  535.73  4377.4  534.71
  4450.0  540.88  4667.7  550.34  4701.0  544.58  4709.2  536.69  4719.6  532.17
  4761.1  527.14  4770.0  534.12  4775.1  535.00  5199.8  535.00  5212.8  526.77
  5213.5  526.27  5218.2  526.77  5300.6  535.96  5324.1  538.67  5332.8  544.07
  5360.0  553.47  5428.5  560.18  5471.5  569.58  5508.6  573.05  5586.9  575.03
#Mann=5,-1,0
  3229.1    0.12       0  4309.2    0.05       0  5212.8   0.033       0
  5218.2    0.05       0  5300.6    0.12       0
Bank Sta=5212.8,5218.2
Exp/Cntr=0.3,0.1

Type RM Length L Ch R = 1,1933,0,0,0
BEGIN DESCRIPTION:
Unnamed 4 4.0
END DESCRIPTION:
XS GIS Cut Line= 3
      2389160.51      7054252.08      2387379.00      7053560.00
      2386678.98      7054210.02
#Sta/Elev= 30
  3088.8  583.15  3137.3  577.81  3216.3  556.02  3283.5  547.26  3401.5  558.15
  3439.4  565.28  3463.8  564.00  3469.3  560.13  3493.8  563.80  3499.2  561.01
  3548.3  573.13  3594.6  570.68  3665.8  555.37  3711.6  551.74  3717.0  555.77
  3746.9  555.78  3885.6  537.34  4073.5  527.46  4103.4  535.00  5651.1  535.00
  5657.9  529.18  5669.4  526.99  5670.2  526.49  5674.8  526.99  5771.3  539.75
  5792.3  549.51  5799.6  548.11  5823.8  555.56  5891.5  578.12  5955.3  586.07
#Mann=6,-1,0
  3088.8    0.05       0  3463.8    0.12       0  3665.8    0.05       0
  5669.4   0.033       0  5674.8    0.05       0  5823.8    0.12       0
Bank Sta=5669.4,5674.8
Exp/Cntr=0.3,0.1

Chan Stop Cuts=-1