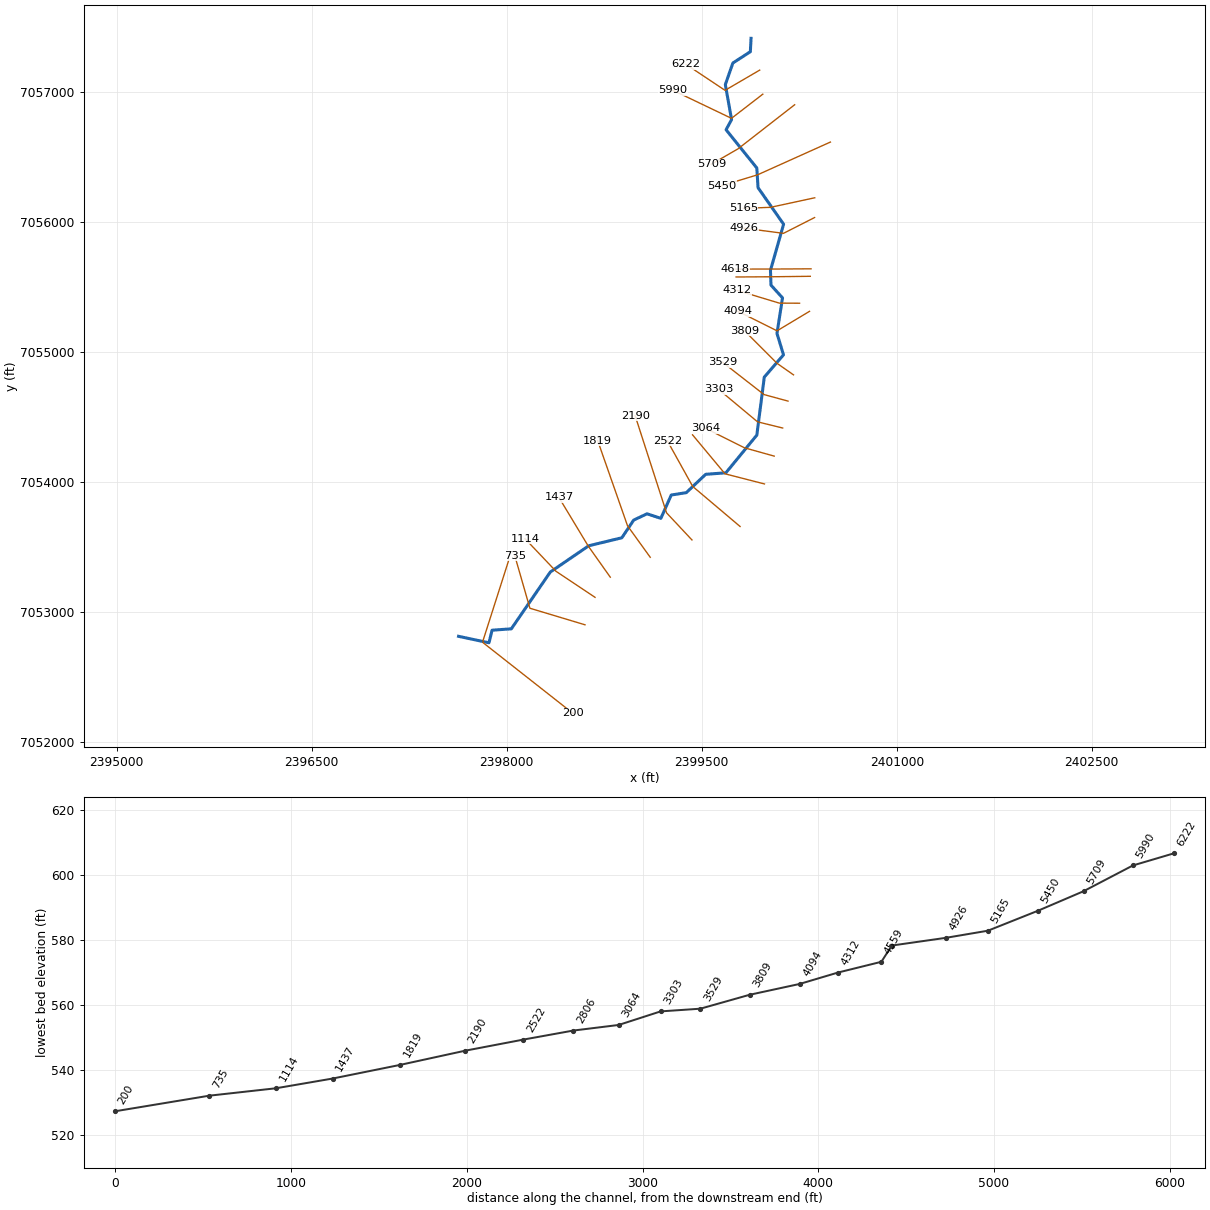
--- Unnamed 5 Tr 1.prj (project) ---

Proj Title=Unnamed 5 Tr 1 Base Level Engineering
Current Plan=p01
Default Exp/Contr=0.3,0.1
English Units
Geom File=g01
Flow File=f01
Plan File=p01
BEGIN DESCRIPTION:
Unnamed 5 Tr 1
END DESCRIPTION:

--- Unnamed 5 Tr 1.p01 (plan) ---

Plan Title=Multiple Run
Short Identifier=Multiple
Geom File=g01
Flow File=f01
Subcritical Flow
K Sum by GR= 0
Std Step Tol= 0.01
Critical Tol= 0.01
Num of Std Step Trials= 20
Max Error Tol= 0.3
Flow Tol Ratio= 0.001
Split Flow NTrial= 30
Split Flow Tol= 0.02
Split Flow Ratio= 0.02
Log Output Level= 0
Friction Slope Method= 1
Unsteady Friction Slope Method= 2
Unsteady Bridges Friction Slope Method= 1
Parabolic Critical Depth
Global Vel Dist=  1 , 1 , 1
Global Log Level= 0
CheckData=True
Encroach Param= -1, 0, 0, 0
BEGIN DESCRIPTION:
Multiple Run
END DESCRIPTION:

--- Unnamed 5 Tr 1.f01 (steady flow) ---

Flow Title=Multiple
Number of Profiles=7
Profile Names=10-year,25-year,50-year,1pct_min,100-year,1pct_plu,500-year
River Rch & RM= Unnamed 5 Tr 1,Reach-1,6222
     199     255     299     175     350     698     477
River Rch & RM= Unnamed 5 Tr 1,Reach-1,4618
     489     668     816     496     990    1976    1460
River Rch & RM= Unnamed 5 Tr 1,Reach-1,1819
     559     769     944     576    1149    2293    1707
Boundary for River Rch & Prof#=Unnamed 5 Tr 1,Reach-1,1
Up Type=0
Dn Type=3
Dn Slope=0.005
Boundary for River Rch & Prof#=Unnamed 5 Tr 1,Reach-1,2
Up Type=0
Dn Type=3
Dn Slope=0.005
Boundary for River Rch & Prof#=Unnamed 5 Tr 1,Reach-1,3
Up Type=0
Dn Type=3
Dn Slope=0.005
Boundary for River Rch & Prof#=Unnamed 5 Tr 1,Reach-1,4
Up Type=0
Dn Type=3
Dn Slope=0.005
Boundary for River Rch & Prof#=Unnamed 5 Tr 1,Reach-1,5
Up Type=0
Dn Type=3
Dn Slope=0.005
Boundary for River Rch & Prof#=Unnamed 5 Tr 1,Reach-1,6
Up Type=0
Dn Type=3
Dn Slope=0.005
Boundary for River Rch & Prof#=Unnamed 5 Tr 1,Reach-1,7
Up Type=0
Dn Type=3
Dn Slope=0.005

--- Unnamed 5 Tr 1.g01 (geometry) ---

Geom Title=Existing Conditions

River Reach=Unnamed 5 Tr 1,Reach-1
Reach XY= 30
      2399879.00      7057410.00      2399873.77      7057307.22
      2399739.39      7057220.10      2399681.26      7057054.06
      2399729.31      7056784.96      2399687.07      7056706.69
      2399923.53      7056412.45      2399932.76      7056261.56
      2400129.46      7055980.17      2400028.52      7055625.17
      2400032.55      7055511.47      2400121.19      7055413.41
      2400078.64      7055139.85      2400128.76      7054975.22
      2399981.06      7054804.15      2399923.48      7054357.57
      2399685.47      7054067.70      2399530.47      7054056.46
      2399381.42      7053915.53      2399265.28      7053896.77
      2399185.38      7053717.37      2399079.00      7053752.44
      2398976.46      7053704.30      2398885.34      7053568.02
      2398630.47      7053506.45      2398334.62      7053304.38
      2398035.20      7052867.81      2397887.00      7052856.99
      2397863.23      7052760.17      2397629.00      7052810.00

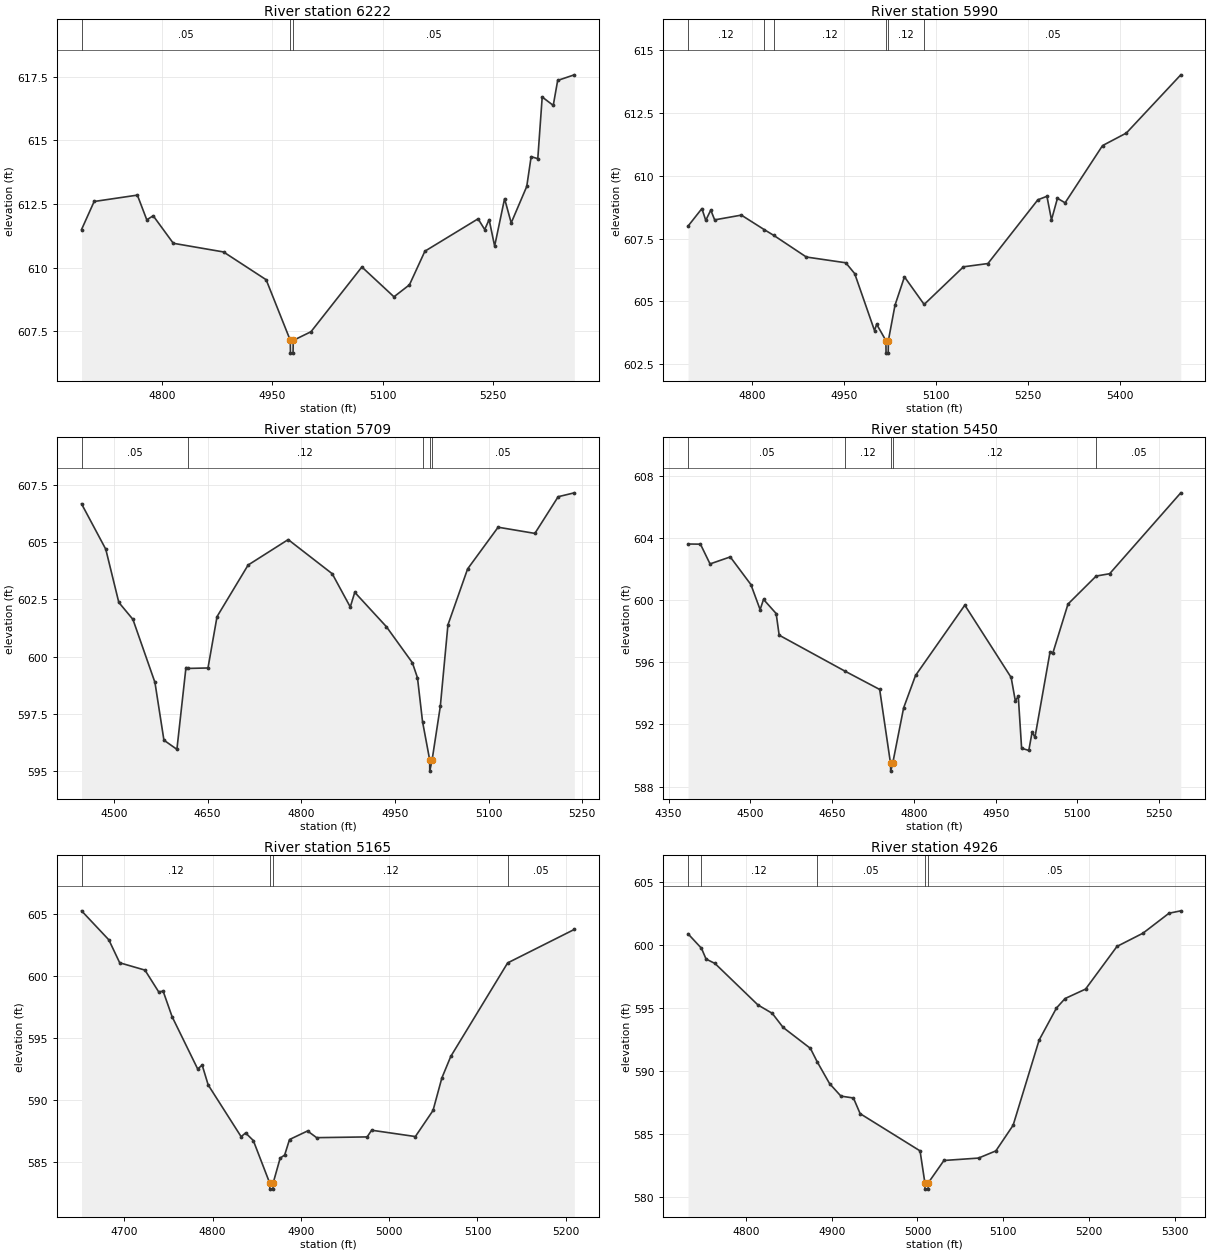
Type RM Length L Ch R = 1,6222,232,232,232
BEGIN DESCRIPTION:
Unnamed 5 Tr 1 21.0
END DESCRIPTION:
XS GIS Cut Line= 3
      2399945.57      7057165.50      2399679.00      7057010.00
      2399378.97      7057210.02
#Sta/Elev= 30
  4690.9  611.50  4708.0  612.60  4766.7  612.85  4779.5  611.88  4788.2  612.04
  4815.5  610.96  4883.7  610.62  4941.6  609.53  4974.4  607.15  4974.6  606.65
  4978.1  606.65  4978.4  607.15  5002.5  607.49  5071.6  610.03  5115.2  608.86
  5136.2  609.33  5157.2  610.65  5229.4  611.92  5238.4  611.50  5244.4  611.89
  5251.9  610.85  5265.4  612.71  5274.4  611.76  5295.5  613.19  5301.5  614.36
  5310.5  614.28  5316.5  616.70  5331.5  616.37  5337.5  617.35  5360.1  617.57
#Mann=3,-1,0
  4690.9    0.05       0  4974.4    0.04       0  4978.4    0.05       0
Bank Sta=4974.4,4978.4
Exp/Cntr=0.3,0.1

Type RM Length L Ch R = 1,5990,281,281,281
BEGIN DESCRIPTION:
Unnamed 5 Tr 1 20.0
END DESCRIPTION:
XS GIS Cut Line= 3
      2399969.59      7056980.54      2399728.85      7056794.58
      2399278.97      7057010.01
#Sta/Elev= 30
  4695.8  608.00  4718.4  608.70  4724.7  608.23  4732.9  608.64  4739.2  608.25
  4782.7  608.44  4820.1  607.86  4835.7  607.63  4888.6  606.77  4952.9  606.54
  4967.4  606.11  4999.7  603.84  5003.2  604.09  5018.3  603.44  5018.5  602.94
  5022.0  602.94  5022.3  603.44  5033.1  604.85  5048.5  605.98  5080.6  604.88
  5144.7  606.38  5184.5  606.51  5265.9  609.05  5280.7  609.19  5288.1  608.25
  5297.8  609.11  5310.3  608.93  5371.3  611.21  5410.1  611.71  5498.8  614.03
#Mann=6,-1,0
  4695.8    0.12       0  4820.1    0.05       0  4835.7    0.12       0
  5018.3    0.07       0  5022.3    0.12       0  5080.6    0.05       0
Bank Sta=5018.3,5022.3
Exp/Cntr=0.3,0.1

Type RM Length L Ch R = 1,5709,259,259,259
BEGIN DESCRIPTION:
Unnamed 5 Tr 1 19.0
END DESCRIPTION:
XS GIS Cut Line= 3
      2400214.45      7056899.02      2399779.00      7056560.00
      2399573.05      7056441.24
#Sta/Elev= 30
  4447.9  606.66  4486.7  604.68  4507.6  602.36  4530.2  601.62  4565.5  598.87
  4579.9  596.35  4600.7  595.95  4615.2  599.52  4618.5  599.48  4650.5  599.50
  4665.0  601.74  4714.8  603.99  4779.0  605.10  4849.6  603.61  4878.5  602.16
  4885.7  602.80  4936.4  601.30  4978.0  599.73  4986.2  599.07  4994.3  597.16
  5005.7  595.50  5005.9  595.00  5009.7  595.50  5022.8  597.83  5035.0  601.38
  5066.5  603.82  5115.4  605.64  5174.3  605.37  5211.6  606.97  5237.5  607.14
#Mann=5,-1,0
  4447.9    0.05       0  4618.5    0.12       0  4994.3    0.05       0
  5005.7   0.033       0  5009.7    0.05       0
Bank Sta=5005.7,5009.7
Exp/Cntr=0.3,0.1

Type RM Length L Ch R = 1,5450,285,285,285
BEGIN DESCRIPTION:
Unnamed 5 Tr 1 18.0
END DESCRIPTION:
XS GIS Cut Line= 3
      2400489.67      7056612.13      2399929.00      7056360.00
      2399652.12      7056276.33
#Sta/Elev= 30
  4385.6  603.60  4408.4  603.59  4426.0  602.32  4463.1  602.77  4501.0  600.99
  4517.9  599.38  4524.1  600.04  4547.3  599.13  4552.8  597.74  4673.4  595.43
  4737.2  594.25  4757.1  589.50  4757.4  589.00  4761.1  589.50  4781.1  593.06
  4803.0  595.15  4893.4  599.67  4978.4  595.02  4986.0  593.53  4991.5  593.80
  4997.6  590.47  5010.8  590.33  5016.8  591.50  5022.1  591.18  5049.8  596.67
  5055.0  596.60  5082.7  599.74  5134.4  601.54  5159.1  601.69  5289.6  606.89
#Mann=5,-1,0
  4385.6    0.05       0  4673.4    0.12       0  4757.1    0.07       0
  4761.1    0.12       0  5134.4    0.05       0
Bank Sta=4757.1,4761.1
Exp/Cntr=0.3,0.1

Type RM Length L Ch R = 1,5165,239,239,239
BEGIN DESCRIPTION:
Unnamed 5 Tr 1 17.0
END DESCRIPTION:
XS GIS Cut Line= 3
      2400369.16      7056183.49      2400029.00      7056110.00
      2399819.15      7056102.23
#Sta/Elev= 30
  4651.7  605.29  4682.6  602.95  4694.9  601.10  4723.5  600.51  4739.0  598.76
  4744.1  598.81  4754.2  596.76  4783.2  592.54  4788.3  592.85  4795.1  591.25
  4832.4  587.08  4837.5  587.38  4846.2  586.77  4864.7  583.35  4865.0  582.85
  4868.5  582.85  4868.7  583.35  4876.6  585.35  4881.7  585.60  4887.2  586.85
  4907.6  587.54  4917.9  587.00  4975.1  587.06  4980.2  587.60  5029.7  587.09
  5049.7  589.19  5059.7  591.81  5069.8  593.55  5134.2  601.09  5209.7  603.79
#Mann=4,-1,0
  4651.7    0.12       0  4864.7    0.07       0  4868.7    0.12       0
  5134.2    0.05       0
Bank Sta=4864.7,4868.7
Exp/Cntr=0.3,0.1

Type RM Length L Ch R = 1,4926,308,308,308
BEGIN DESCRIPTION:
Unnamed 5 Tr 1 16.0
END DESCRIPTION:
XS GIS Cut Line= 3
      2400367.72      7056031.39      2400129.00      7055910.00
      2399825.36      7055949.45
#Sta/Elev= 30
  4732.7  600.89  4748.4  599.74  4753.7  598.89  4764.1  598.54  4814.2  595.25
  4830.8  594.59  4843.5  593.47  4875.3  591.81  4883.0  590.77  4897.6  589.02
  4910.8  588.03  4925.4  587.88  4933.2  586.64  5003.0  583.69  5008.6  581.16
  5008.8  580.66  5012.3  580.66  5012.6  581.16  5030.8  582.93  5071.1  583.12
  5091.3  583.69  5111.4  585.72  5141.7  592.47  5161.9  595.01  5171.9  595.76
  5195.8  596.51  5232.4  599.89  5262.7  600.94  5293.0  602.52  5306.7  602.71
#Mann=5,-1,0
  4732.7    0.05       0  4748.4    0.12       0  4883.0    0.05       0
  5008.6   0.033       0  5012.6    0.05       0
Bank Sta=5008.6,5012.6
Exp/Cntr=0.3,0.1

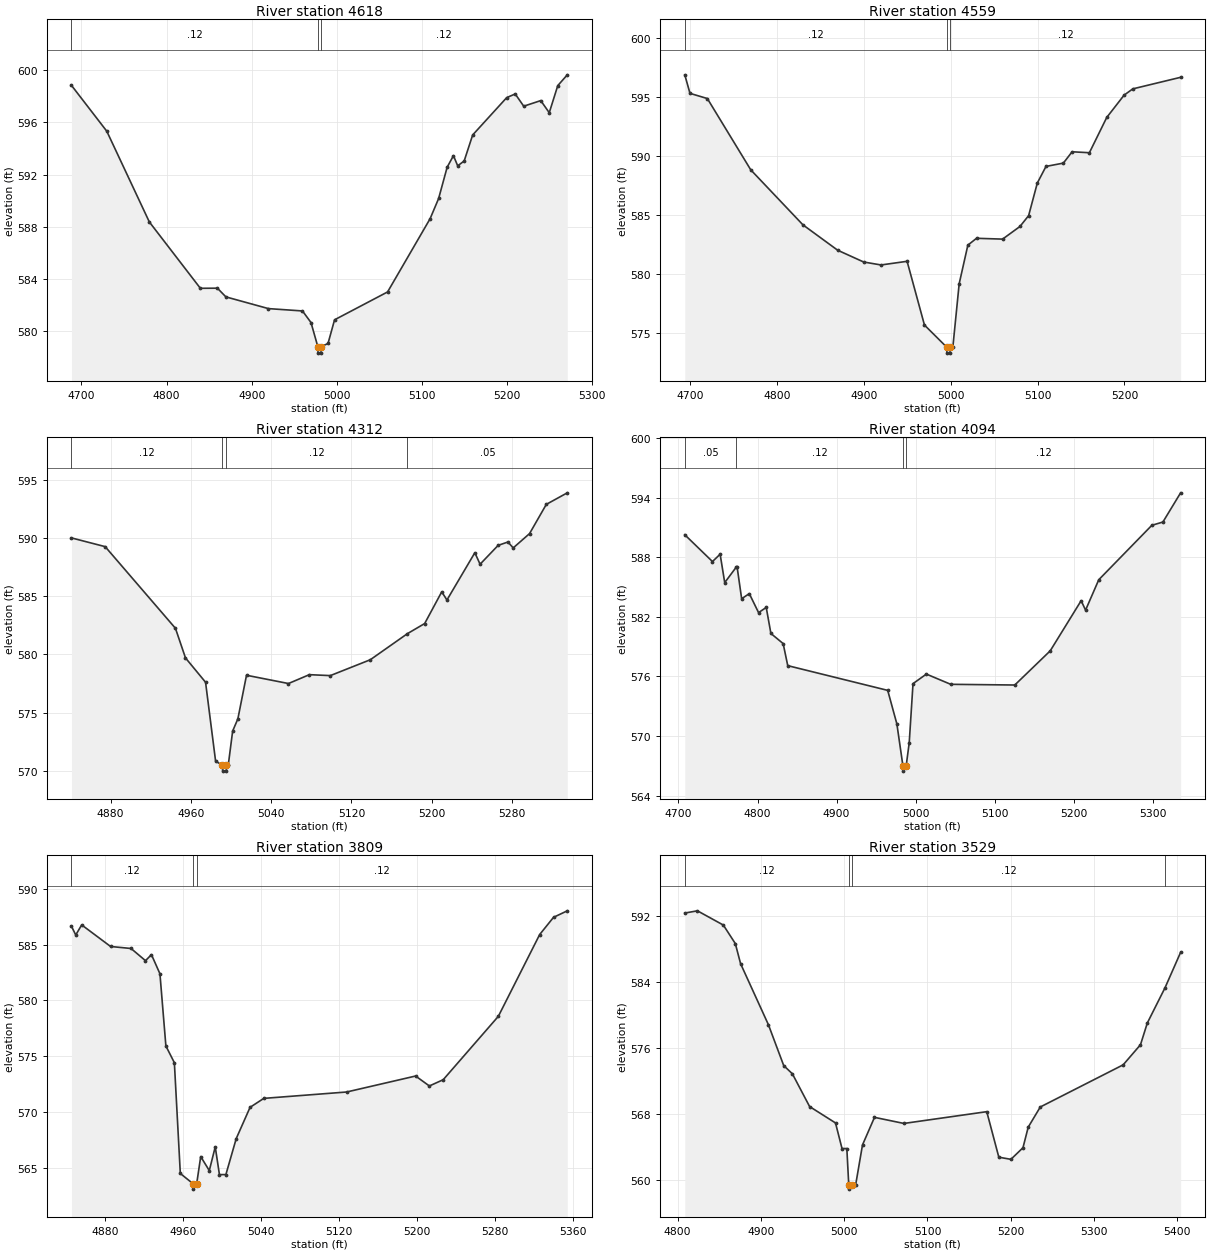
Type RM Length L Ch R = 1,4618,59,59,59
BEGIN DESCRIPTION:
Unnamed 5 Tr 1 15.0
END DESCRIPTION:
XS GIS Cut Line= 3
      2400340.53      7055637.09      2400028.74      7055635.09
      2399757.84      7055634.92
#Sta/Elev= 30
  4688.2  598.85  4729.7  595.33  4779.7  588.36  4839.7  583.26  4859.7  583.27
  4869.7  582.60  4919.7  581.70  4959.7  581.52  4969.7  580.63  4977.7  578.78
  4978.0  578.28  4981.5  578.28  4981.7  578.78  4989.7  579.02  4997.4  580.84
  5059.7  582.98  5109.7  588.61  5119.7  590.16  5129.7  592.56  5137.1  593.45
  5142.1  592.67  5149.7  593.04  5159.7  595.04  5199.7  597.91  5209.7  598.19
  5219.7  597.25  5239.7  597.68  5249.7  596.75  5259.7  598.83  5270.9  599.66
#Mann=3,-1,0
  4688.2    0.12       0  4977.7    0.07       0  4981.7    0.12       0
Bank Sta=4977.7,4981.7
Exp/Cntr=0.3,0.1

Type RM Length L Ch R = 1,4559,247,247,247
BEGIN DESCRIPTION:
Mapping XS a2fb7290
END DESCRIPTION:
XS GIS Cut Line= 3
      2400335.04      7055579.44      2400028.56      7055575.80
      2399763.87      7055574.23
#Sta/Elev= 30
  4693.5  596.86  4699.5  595.29  4719.5  594.85  4769.5  588.81  4829.6  584.15
  4869.6  582.00  4899.6  581.00  4919.6  580.75  4949.6  581.06  4969.6  575.66
  4995.3  573.78  4995.5  573.28  4999.0  573.28  4999.3  573.78  5002.3  573.78
  5009.6  579.16  5019.6  582.43  5029.6  583.01  5059.6  582.94  5079.6  584.01
  5089.6  584.93  5099.6  587.69  5109.6  589.10  5129.6  589.38  5139.7  590.34
  5159.6  590.26  5179.6  593.25  5199.6  595.14  5209.6  595.67  5264.7  596.65
#Mann=3,-1,0
  4693.5    0.12       0  4995.3    0.07       0  4999.3    0.12       0
Bank Sta=4995.3,4999.3
Exp/Cntr=0.3,0.1

Type RM Length L Ch R = 1,4312,218,218,218
BEGIN DESCRIPTION:
Unnamed 5 Tr 1 14.0
END DESCRIPTION:
XS GIS Cut Line= 3
      2400252.60      7055372.33      2400096.40      7055373.20
      2399773.00      7055470.76
#Sta/Elev= 30
  4841.1  589.99  4874.7  589.24  4944.7  582.23  4954.7  579.69  4974.7  577.60
  4984.7  570.83  4991.5  570.47  4991.8  569.97  4995.3  569.97  4995.5  570.47
  4997.3  570.47  5001.7  573.41  5006.9  574.46  5015.5  578.20  5057.3  577.49
  5078.1  578.25  5099.0  578.17  5138.8  579.53  5175.8  581.77  5193.0  582.64
  5210.0  585.36  5215.2  584.66  5243.0  588.72  5248.2  587.73  5266.2  589.35
  5276.0  589.64  5281.2  589.13  5297.5  590.36  5314.2  592.87  5335.1  593.86
#Mann=4,-1,0
  4841.1    0.12       0  4991.5    0.07       0  4995.5    0.12       0
  5175.8    0.05       0
Bank Sta=4991.5,4995.5
Exp/Cntr=0.3,0.1

Type RM Length L Ch R = 1,4094,285,285,285
BEGIN DESCRIPTION:
Unnamed 5 Tr 1 13.0
END DESCRIPTION:
XS GIS Cut Line= 3
      2400329.01      7055310.00      2400079.00      7055160.00
      2399778.97      7055310.02
#Sta/Elev= 30
  4708.0  590.26  4743.0  587.56  4752.7  588.30  4758.5  585.44  4772.9  586.98
  4774.1  587.06  4779.9  583.82  4789.6  584.33  4801.3  582.42  4811.0  582.94
  4816.9  580.32  4832.4  579.30  4838.2  577.08  4964.6  574.59  4976.2  571.21
  4983.9  566.96  4984.2  566.46  4987.9  566.96  4991.8  569.31  4996.6  575.27
  5013.5  576.23  5044.3  575.20  5125.3  575.13  5170.1  578.57  5209.2  583.62
  5214.8  582.67  5231.5  585.73  5298.6  591.21  5312.6  591.54  5335.0  594.48
#Mann=4,-1,0
  4708.0    0.05       0  4772.9    0.12       0  4983.9    0.07       0
  4987.9    0.12       0
Bank Sta=4983.9,4987.9
Exp/Cntr=0.3,0.1

Type RM Length L Ch R = 1,3809,280,280,280
BEGIN DESCRIPTION:
Unnamed 5 Tr 1 12.0
END DESCRIPTION:
XS GIS Cut Line= 3
      2400205.78      7054821.21      2400079.00      7054910.00
      2399829.02      7055159.98
#Sta/Elev= 30
  4845.5  586.64  4849.9  585.86  4856.0  586.76  4885.6  584.83  4906.6  584.65
  4921.4  583.56  4927.5  584.10  4936.2  582.39  4942.3  575.93  4951.0  574.43
  4957.1  564.52  4969.9  563.62  4970.2  563.12  4973.9  563.62  4978.0  566.03
  4986.8  564.78  4992.9  566.90  4997.2  564.42  5003.8  564.42  5014.4  567.64
  5028.6  570.44  5042.7  571.24  5127.6  571.81  5198.3  573.24  5212.4  572.35
  5226.6  572.91  5283.1  578.58  5325.5  585.90  5339.7  587.44  5353.8  588.02
#Mann=3,-1,0
  4845.5    0.12       0  4969.9    0.07       0  4973.9    0.12       0
Bank Sta=4969.9,4973.9
Exp/Cntr=0.3,0.1

Type RM Length L Ch R = 1,3529,226,226,226
BEGIN DESCRIPTION:
Unnamed 5 Tr 1 11.0
END DESCRIPTION:
XS GIS Cut Line= 3
      2400163.64      7054619.35      2399978.98      7054669.68
      2399660.25      7054917.92
#Sta/Elev= 30
  4808.6  592.38  4823.8  592.65  4854.9  590.92  4869.3  588.67  4875.6  586.23
  4909.0  578.82  4927.4  573.85  4937.8  572.85  4958.5  568.87  4989.6  566.88
  4997.4  563.77  5003.2  563.77  5005.5  559.34  5005.7  558.84  5009.5  559.34
  5013.8  559.37  5022.0  564.21  5036.4  567.56  5071.7  566.82  5171.2  568.25
  5185.7  562.72  5200.2  562.46  5214.7  563.87  5221.0  566.37  5235.5  568.82
  5335.0  573.94  5355.8  576.38  5364.0  579.02  5385.3  583.31  5404.0  587.61
#Mann=4,-1,0
  4808.6    0.12       0  5005.5    0.07       0  5009.5    0.12       0
  5385.3    0.05       0
Bank Sta=5005.5,5009.5
Exp/Cntr=0.3,0.1

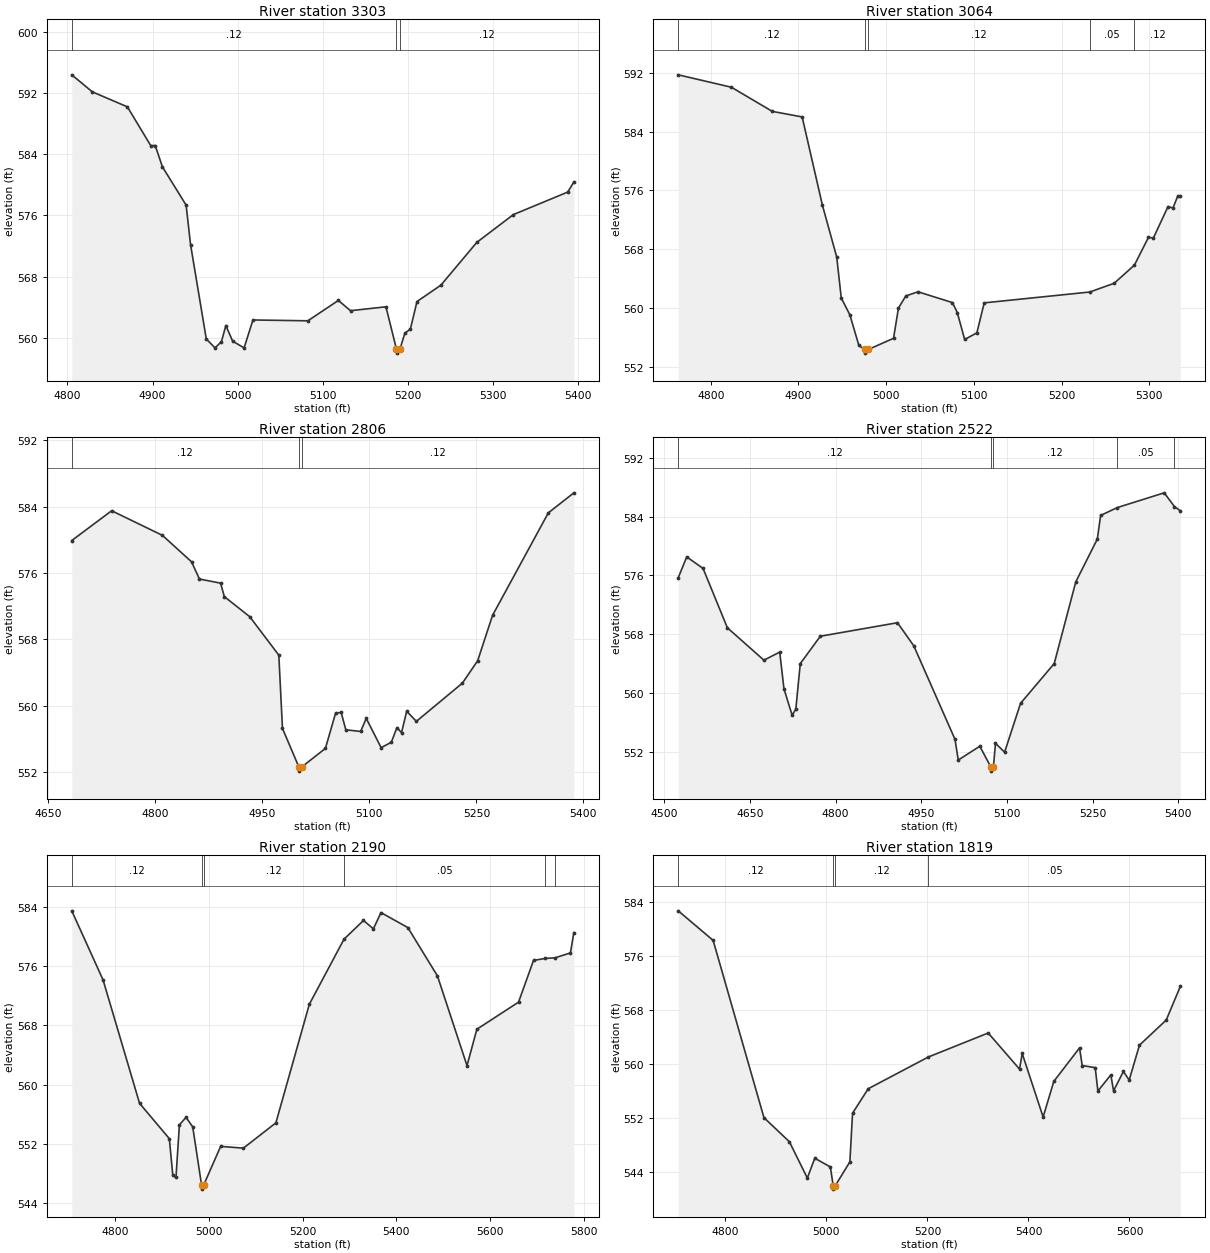
Type RM Length L Ch R = 1,3303,239,239,239
BEGIN DESCRIPTION:
Unnamed 5 Tr 1 10.0
END DESCRIPTION:
XS GIS Cut Line= 3
      2400122.39      7054412.37      2399929.00      7054460.00
      2399628.99      7054710.01
#Sta/Elev= 30
  4805.1  594.35  4829.2  592.13  4870.4  590.17  4897.9  585.10  4903.1  585.12
  4911.6  582.33  4939.4  577.34  4944.6  572.19  4963.1  559.86  4973.4  558.69
  4980.9  559.52  4986.1  561.61  4994.0  559.58  5007.5  558.69  5017.9  562.34
  5082.4  562.23  5118.2  564.89  5132.5  563.55  5174.1  564.06  5186.5  558.51
  5186.7  558.01  5190.5  558.51  5196.3  560.61  5202.8  561.15  5210.6  564.75
  5238.6  566.88  5280.9  572.48  5323.8  576.10  5387.6  579.04  5394.8  580.35
#Mann=3,-1,0
  4805.1    0.12       0  5186.5    0.07       0  5190.5    0.12       0
Bank Sta=5186.5,5190.5
Exp/Cntr=0.3,0.1

Type RM Length L Ch R = 1,3064,258,258,258
BEGIN DESCRIPTION:
Unnamed 5 Tr 1 9.0
END DESCRIPTION:
XS GIS Cut Line= 3
      2400057.37      7054196.21      2399829.00      7054260.00
      2399529.02      7054409.99
#Sta/Elev= 30
  4762.9  591.76  4823.5  590.07  4870.1  586.78  4904.2  586.02  4927.3  573.99
  4943.6  566.93  4948.8  561.34  4958.5  559.08  4968.9  554.87  4975.7  554.33
  4976.0  553.83  4979.7  554.33  5008.4  555.85  5014.0  559.97  5022.4  561.62
  5036.3  562.19  5075.5  560.72  5081.1  559.36  5089.5  555.69  5103.4  556.59
  5111.8  560.68  5232.2  562.16  5260.0  563.35  5283.1  565.83  5299.1  569.62
  5304.7  569.52  5321.4  573.81  5327.0  573.61  5332.6  575.27  5335.4  575.27
#Mann=5,-1,0
  4762.9    0.12       0  4975.7    0.07       0  4979.7    0.12       0
  5232.2    0.05       0  5283.1    0.12       0
Bank Sta=4975.7,4979.7
Exp/Cntr=0.3,0.1

Type RM Length L Ch R = 1,2806,284,284,284
BEGIN DESCRIPTION:
Unnamed 5 Tr 1 8.0
END DESCRIPTION:
XS GIS Cut Line= 3
      2399982.33      7053982.19      2399679.00      7054060.00
      2399428.98      7054360.03
#Sta/Elev= 30
  4682.9  579.91  4738.8  583.50  4810.0  580.53  4850.8  577.34  4861.8  575.27
  4891.5  574.77  4896.7  573.15  4932.3  570.73  4973.1  566.09  4978.2  557.26
  5001.2  552.61  5001.5  552.11  5005.2  552.61  5038.4  554.85  5052.7  559.11
  5060.5  559.18  5067.0  557.09  5087.8  556.89  5095.6  558.47  5116.5  554.94
  5130.8  555.59  5138.6  557.35  5145.1  556.75  5152.3  559.33  5165.9  558.11
  5230.4  562.72  5251.8  565.42  5272.7  570.90  5350.8  583.24  5386.6  585.66
#Mann=3,-1,0
  4682.9    0.12       0  5001.2    0.07       0  5005.2    0.12       0
Bank Sta=5001.2,5005.2
Exp/Cntr=0.3,0.1

Type RM Length L Ch R = 1,2522,332,332,332
BEGIN DESCRIPTION:
Mapping XS 64f19f5a
END DESCRIPTION:
XS GIS Cut Line= 3
      2399794.78      7053654.91      2399430.18      7053963.09
      2399234.85      7054314.67
#Sta/Elev= 30
  4524.2  575.66  4539.1  578.51  4567.7  576.93  4610.3  568.85  4674.3  564.44
  4702.0  565.54  4709.4  560.55  4723.7  556.95  4730.2  557.77  4738.0  563.97
  4773.1  567.70  4908.3  569.54  4936.9  566.39  5009.1  553.65  5014.8  550.84
  5052.5  552.72  5072.3  549.83  5072.5  549.33  5076.3  549.83  5080.0  553.12
  5096.0  551.91  5123.9  558.56  5182.9  563.98  5220.7  575.11  5258.4  580.93
  5264.2  584.15  5293.3  585.22  5375.6  587.23  5393.6  585.35  5403.8  584.79
#Mann=5,-1,0
  4524.2    0.12       0  5072.3    0.07       0  5076.3    0.12       0
  5293.3    0.05       0  5393.6    0.12       0
Bank Sta=5072.3,5076.3
Exp/Cntr=0.3,0.1

Type RM Length L Ch R = 1,2190,371,371,371
BEGIN DESCRIPTION:
Unnamed 5 Tr 1 6.0
END DESCRIPTION:
XS GIS Cut Line= 3
      2399424.59      7053551.26      2399229.00      7053760.00
      2398987.60      7054506.90
#Sta/Elev= 30
  4707.5  583.45  4774.3  574.12  4852.1  557.48  4915.6  552.71  4923.0  547.79
  4929.8  547.47  4937.1  554.58  4951.3  555.58  4965.5  554.30  4984.5  546.40
  4984.7  545.90  4988.5  546.40  5025.1  551.67  5073.6  551.43  5142.9  554.84
  5214.3  570.85  5288.3  579.63  5329.8  582.15  5350.9  581.02  5367.1  583.21
  5424.4  581.19  5487.5  574.67  5550.6  562.56  5571.6  567.47  5660.5  571.13
  5692.5  576.76  5717.9  577.03  5737.7  577.10  5771.2  577.77  5778.5  580.51
#Mann=6,-1,0
  4707.5    0.12       0  4984.5    0.07       0  4988.5    0.12       0
  5288.3    0.05       0  5717.9    0.12       0  5737.7    0.05       0
Bank Sta=4984.5,4988.5
Exp/Cntr=0.3,0.1

Type RM Length L Ch R = 1,1819,382,382,382
BEGIN DESCRIPTION:
Unnamed 5 Tr 1 5.0
END DESCRIPTION:
XS GIS Cut Line= 3
      2399103.69      7053417.87      2398929.00      7053660.00
      2398699.11      7054316.34
#Sta/Elev= 30
  4706.6  582.66  4775.7  578.29  4876.3  552.09  4926.6  548.53  4962.2  543.16
  4976.9  546.09  5007.8  544.80  5013.4  542.02  5013.6  541.52  5017.4  542.02
  5046.4  545.55  5051.7  552.74  5082.7  556.36  5202.0  561.06  5320.3  564.60
  5382.3  559.26  5387.6  561.57  5429.0  552.18  5450.2  557.45  5501.1  562.40
  5506.4  559.79  5532.1  559.48  5537.4  556.02  5563.1  558.41  5568.4  556.04
  5587.9  558.91  5599.4  557.64  5619.7  562.80  5672.7  566.51  5700.6  571.48
#Mann=4,-1,0
  4706.6    0.12       0  5013.4    0.07       0  5017.4    0.12       0
  5202.0    0.05       0
Bank Sta=5013.4,5017.4
Exp/Cntr=0.3,0.1

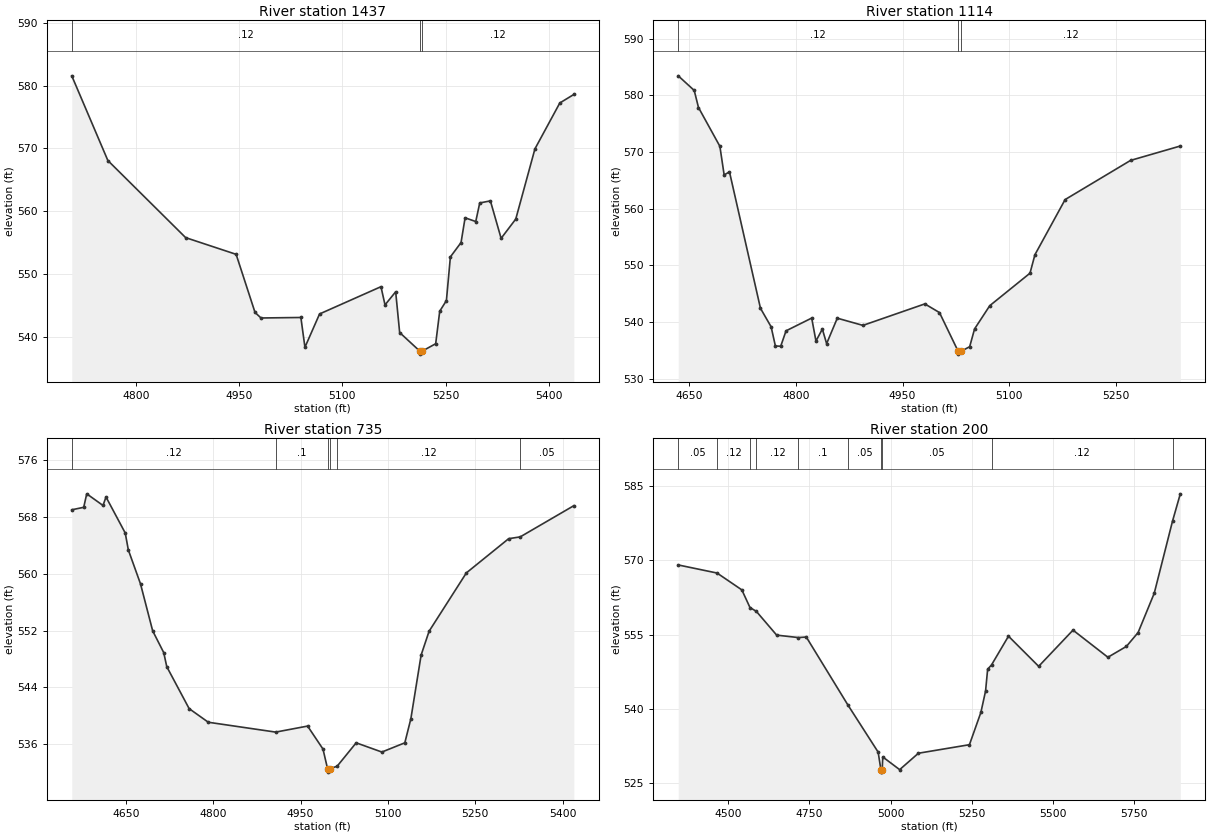
Type RM Length L Ch R = 1,1437,323,323,323
BEGIN DESCRIPTION:
Unnamed 5 Tr 1 4.0
END DESCRIPTION:
XS GIS Cut Line= 3
      2398796.29      7053264.83      2398626.56      7053504.52
      2398401.07      7053878.51
#Sta/Elev= 30
  4706.3  581.54  4758.8  568.09  4872.0  555.84  4945.4  553.19  4972.9  543.96
  4981.6  543.08  5039.6  543.16  5045.5  538.43  5066.8  543.72  5156.1  548.05
  5162.0  545.16  5177.5  547.24  5183.3  540.77  5212.4  537.84  5212.6  537.34
  5216.4  537.84  5235.7  538.99  5241.6  544.16  5251.3  545.84  5257.1  552.78
  5272.6  555.06  5278.5  558.99  5294.0  558.40  5299.8  561.35  5315.3  561.68
  5330.9  555.73  5352.2  558.79  5380.1  569.94  5416.3  577.23  5436.7  578.58
#Mann=3,-1,0
  4706.3    0.12       0  5212.4    0.07       0  5216.4    0.12       0
Bank Sta=5212.4,5216.4
Exp/Cntr=0.3,0.1

Type RM Length L Ch R = 1,1114,379,379,379
BEGIN DESCRIPTION:
Unnamed 5 Tr 1 3.0
END DESCRIPTION:
XS GIS Cut Line= 3
      2398679.00      7053110.00      2398379.00      7053310.00
      2398140.68      7053560.77
#Sta/Elev= 30
  4634.4  583.43  4656.9  580.85  4662.9  577.84  4693.0  571.00  4699.0  565.95
  4706.5  566.49  4750.1  542.43  4765.1  539.16  4771.1  535.78  4778.6  535.73
  4786.1  538.45  4822.2  540.70  4828.2  536.65  4837.2  538.76  4843.2  536.19
  4858.2  540.68  4894.3  539.41  4981.4  543.20  5002.0  541.67  5028.3  534.84
  5028.6  534.34  5032.3  534.84  5044.5  535.65  5051.4  538.79  5072.8  542.89
  5129.4  548.62  5136.3  551.87  5178.8  561.60  5270.9  568.51  5340.9  571.05
#Mann=3,-1,0
  4634.4    0.12       0  5028.3    0.07       0  5032.3    0.12       0
Bank Sta=5028.3,5032.3
Exp/Cntr=0.3,0.1

Type RM Length L Ch R = 1,735,535,535,535
BEGIN DESCRIPTION:
Unnamed 5 Tr 1 2.0
END DESCRIPTION:
XS GIS Cut Line= 3
      2398602.02      7052898.61      2398177.94      7053026.00
      2398062.01      7053428.85
#Sta/Elev= 30
  4557.2  569.03  4577.7  569.38  4582.9  571.28  4610.8  569.64  4616.0  570.83
  4649.0  565.76  4654.3  563.38  4675.2  558.59  4696.1  551.97  4715.1  548.90
  4720.3  546.92  4758.7  541.01  4791.6  539.09  4907.3  537.70  4962.1  538.55
  4988.5  535.31  4996.3  532.56  4996.5  532.06  5000.3  532.56  5012.7  532.88
  5045.5  536.19  5089.6  534.89  5129.0  536.19  5139.4  539.59  5157.0  548.56
  5170.7  551.92  5234.7  560.14  5307.3  564.96  5327.1  565.21  5419.2  569.61
#Mann=6,-1,0
  4557.2    0.12       0  4907.3     0.1       0  4996.3    0.07       0
  5000.3     0.1       0  5012.7    0.12       0  5327.1    0.05       0
Bank Sta=4996.3,5000.3
Exp/Cntr=0.3,0.1

Type RM Length L Ch R = 1,200,0,0,0
BEGIN DESCRIPTION:
Unnamed 5 Tr 1 1.0
END DESCRIPTION:
XS GIS Cut Line= 4
      2398015.46      7053396.65      2397816.22      7052773.42
      2397817.19      7052761.50      2398509.51      7052217.24
#Sta/Elev= 30
  4345.7  569.04  4465.3  567.41  4541.7  564.01  4566.7  560.46  4586.4  559.68
  4649.0  554.89  4715.9  554.40  4740.2  554.51  4868.3  540.82  4961.6  531.31
  4970.1  527.77  4970.3  527.27  4974.1  527.77  4975.9  530.33  5027.9  527.77
  5085.7  531.08  5242.9  532.80  5278.2  539.32  5292.6  543.62  5299.0  548.02
  5311.0  548.89  5363.2  554.68  5456.2  548.60  5562.0  555.90  5669.5  550.43
  5726.6  552.62  5762.6  555.42  5812.3  563.34  5868.7  577.90  5892.6  583.38
#Mann=10,-1,0
  4345.7    0.05       0  4465.3    0.12       0  4566.7    0.05       0
  4586.4    0.12       0  4715.9     0.1       0  4868.3    0.05       0
  4970.1   0.033       0  4974.1    0.05       0  5311.0    0.12       0
  5868.7    0.05       0
Bank Sta=4970.1,4974.1
Exp/Cntr=0.3,0.1

Chan Stop Cuts=-1