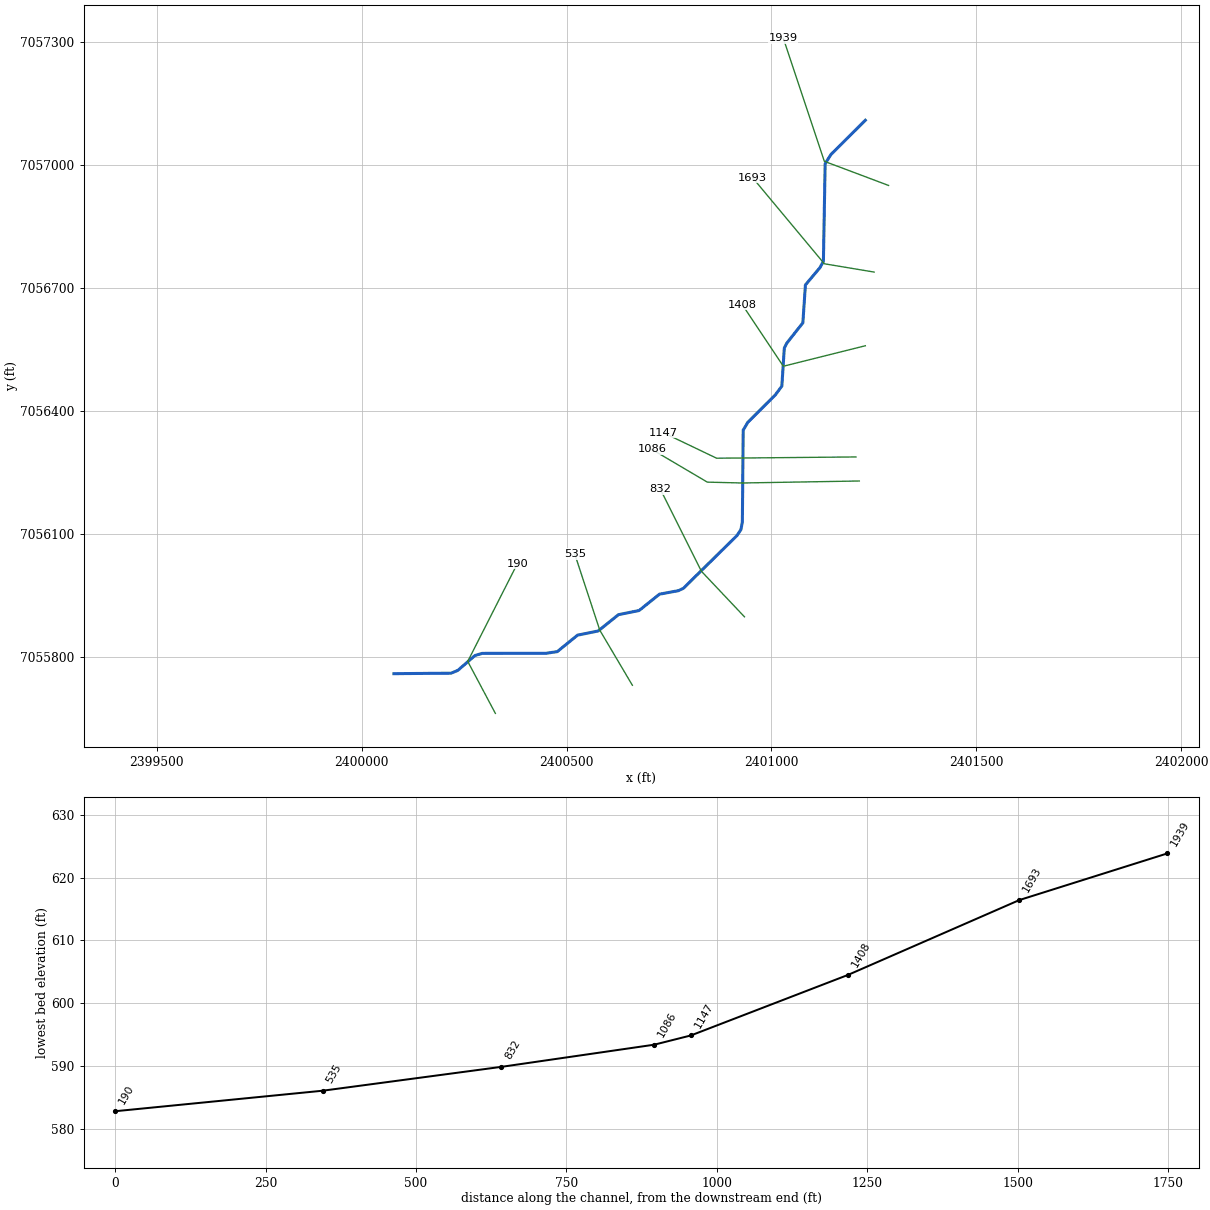
--- Unnamed 5 Tr 1_2.prj (project) ---

Proj Title=Unnamed 5 Tr 1_2 Base Level Engineering
Current Plan=p01
Default Exp/Contr=0.3,0.1
English Units
Geom File=g01
Flow File=f01
Plan File=p01
Y Axis Title=Elevation
X Axis Title(PF)=Main Channel Distance
X Axis Title(XS)=Station
BEGIN DESCRIPTION:
Unnamed 5 Tr 1_2
END DESCRIPTION:
DSS Export Rating Curves= 0
DSS Export Rating Curve Sorted= 0
DSS Export Volume Flow Curves= 0
DXF OffsetX= 0
DXF OffsetY= 0
DXF ScaleX= 1
DXF ScaleY= 10

--- Unnamed 5 Tr 1_2.p01 (plan) ---

Plan Title=Multiple Run
Short Identifier=Multiple
Geom File=g01
Flow File=f01
Subcritical Flow
K Sum by GR= 0
Std Step Tol= 0.01
Critical Tol= 0.01
Num of Std Step Trials= 20
Max Error Tol= 0.3
Flow Tol Ratio= 0.001
Split Flow NTrial= 30
Split Flow Tol= 0.02
Split Flow Ratio= 0.02
Log Output Level= 0
Friction Slope Method= 1
Unsteady Friction Slope Method= 2
Unsteady Bridges Friction Slope Method= 1
Parabolic Critical Depth
Global Vel Dist=  1 , 1 , 1
Global Log Level= 0
CheckData=True
Encroach Param= -1, 0, 0, 0
BEGIN DESCRIPTION:
Multiple Run
END DESCRIPTION:

--- Unnamed 5 Tr 1_2.f01 (steady flow) ---

Flow Title=Multiple
Program Version=4.10
Number of Profiles= 7
Profile Names=10-year,25-year,50-year,1pct_min,100-year,1pct_plu,500-year
River Rch & RM=Unnamed 5 Tr 1_2,Reach-1         ,1939
     123     152     173      99     198     395     257
Boundary for River Rch & Prof#=Unnamed 5 Tr 1_2,Reach-1         , 1
Up Type= 0
Dn Type= 3
Dn Slope=0.0105
Boundary for River Rch & Prof#=Unnamed 5 Tr 1_2,Reach-1         , 2
Up Type= 0
Dn Type= 3
Dn Slope=0.0105
Boundary for River Rch & Prof#=Unnamed 5 Tr 1_2,Reach-1         , 3
Up Type= 0
Dn Type= 3
Dn Slope=0.0105
Boundary for River Rch & Prof#=Unnamed 5 Tr 1_2,Reach-1         , 4
Up Type= 0
Dn Type= 3
Dn Slope=0.0105
Boundary for River Rch & Prof#=Unnamed 5 Tr 1_2,Reach-1         , 5
Up Type= 0
Dn Type= 3
Dn Slope=0.0105
Boundary for River Rch & Prof#=Unnamed 5 Tr 1_2,Reach-1         , 6
Up Type= 0
Dn Type= 3
Dn Slope=0.0105
Boundary for River Rch & Prof#=Unnamed 5 Tr 1_2,Reach-1         , 7
Up Type= 0
Dn Type= 3
Dn Slope=0.0105
DSS Import GetInterval= 0
DSS Import GetPeak= 0
DSS Import FillOption= 0

--- Unnamed 5 Tr 1_2.g01 (geometry) ---

Geom Title=Existing Conditions
Program Version=4.10

River Reach=Unnamed 5 Tr 1_2,Reach-1
Reach XY= 30
        2401229.        7057110.      2401145.33      7057026.81
      2401131.02      7057004.16      2401126.74      7056765.94
      2401118.15      7056750.35      2401082.86       7056708.4
      2401076.65      7056615.97      2401037.19      7056566.04
      2401031.36      7056554.02      2401025.38       7056461.5
      2401009.33      7056439.86       2400942.4      7056373.31
      2400931.07      7056354.14      2400929.04      7056129.98
      2400925.46      7056111.46      2400915.63      7056096.68
      2400785.06      7055968.14      2400772.97       7055962.5
      2400726.81       7055953.9      2400677.28      7055914.16
       2400626.8      7055903.92      2400577.28      7055864.16
      2400526.82      7055853.88      2400477.45      7055813.75
      2400449.15      7055809.64      2400294.22      7055809.48
      2400276.66      7055804.26      2400235.06      7055768.13
      2400218.52      7055761.17        2400079.        7055760.

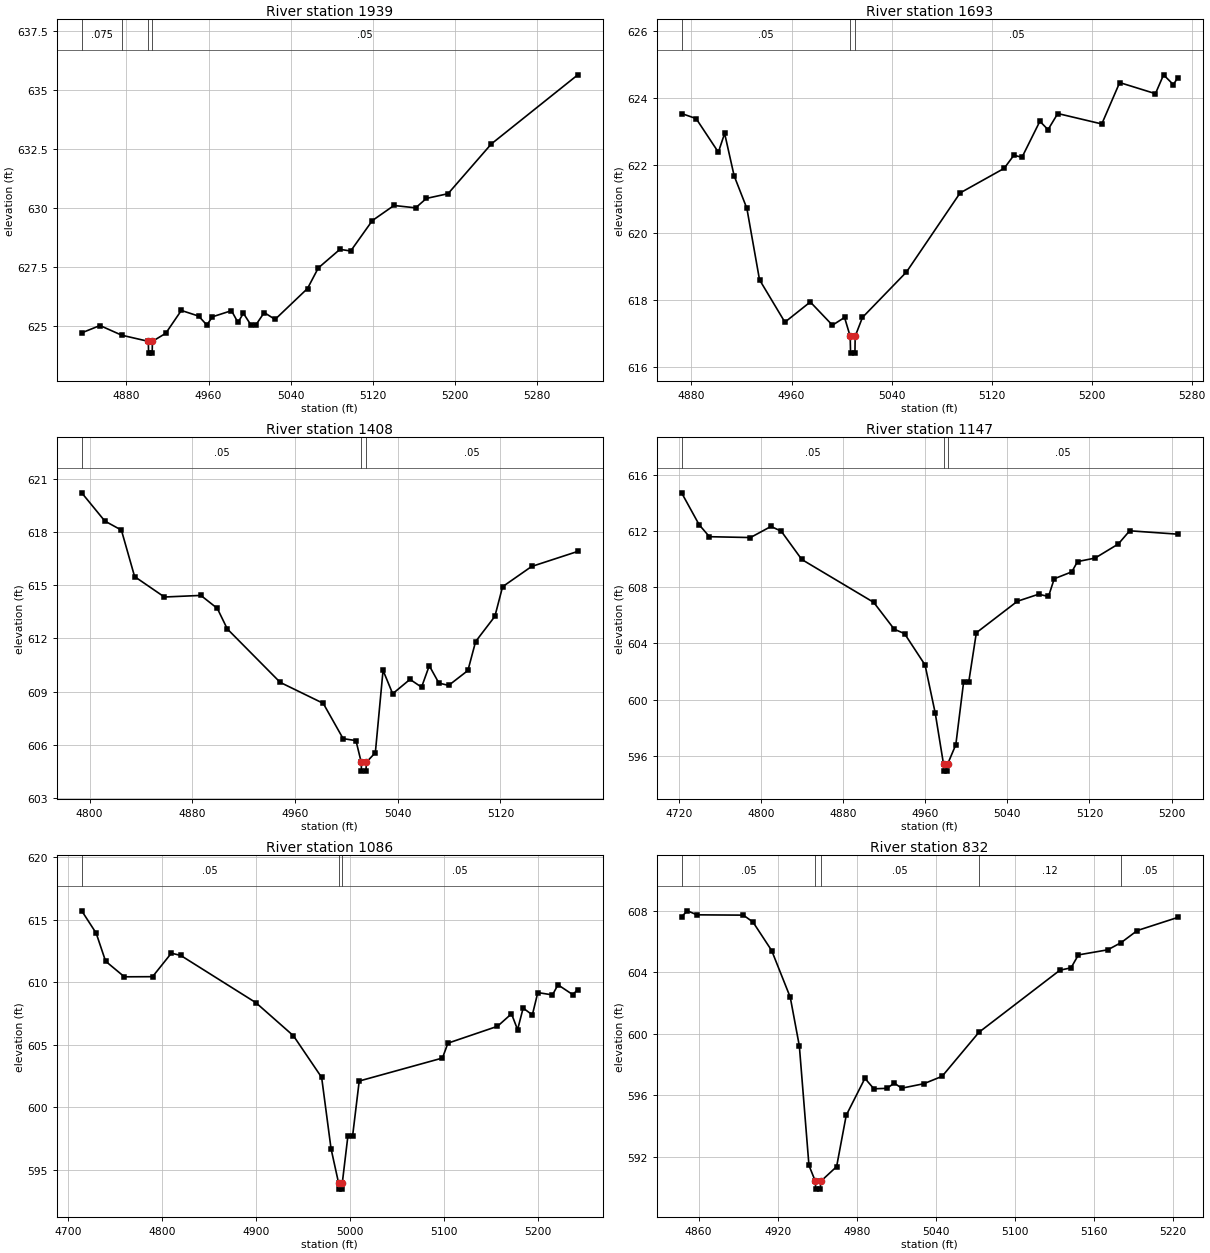
Type RM Length L Ch R = 1 ,1939    ,246,246,246
BEGIN DESCRIPTION:
Unnamed 5 Tr 1_2 7.0
END DESCRIPTION:
XS GIS Cut Line= 3
      2401285.67      7056951.09        2401129.        7057010.
        2401029.      7057309.99
#Sta/Elev= 30
  4836.4  624.69  4854.2     625  4875.4  624.59  4901.3  624.33  4901.6  623.83
  4905.1  623.83  4905.3  624.33  4918.3  624.67  4933.5  625.64  4950.4   625.4
  4958.4  625.02  4963.8  625.37  4982.4  625.63  4988.7  625.13    4994  625.52
  5001.1  625.04  5006.4  625.04  5014.3  625.55  5024.9  625.26  5056.5  626.57
    5067  627.44  5088.1  628.23  5098.6  628.16  5119.7  629.45  5140.8  630.09
  5161.9  629.99  5172.4  630.39  5193.5  630.59  5235.7   632.7    5320  635.63
#Mann= 4 ,-1 , 0
  4836.4    .075       0  4875.4     .05       0  4901.3     .05       0
  4905.3     .05       0
Bank Sta=4901.3,4905.3
XS Rating Curve= 0 ,0
Exp/Cntr=0.3,0.1

Type RM Length L Ch R = 1 ,1693    ,285,285,285
BEGIN DESCRIPTION:
Unnamed 5 Tr 1_2 6.0
END DESCRIPTION:
XS GIS Cut Line= 3
      2401250.46      7056739.76        2401129.        7056760.
      2400953.87      7056970.16
#Sta/Elev= 30
  4872.1  623.54  4883.7  623.39  4901.5  622.39  4906.5  622.95  4914.1  621.69
  4924.3  620.72  4934.4   618.6  4954.7  617.34    4975  617.94  4992.7  617.25
  5002.4  617.48  5006.9  616.92  5007.2  616.42  5010.7  616.42  5010.9  616.92
  5016.7  617.48  5051.9  618.83  5094.8  621.18    5130  621.91  5137.8   622.3
  5144.3  622.24  5158.6  623.31  5165.1  623.06  5172.9  623.54  5208.1  623.23
  5222.4  624.46    5251  624.13  5257.5  624.69  5265.3   624.4  5268.8   624.6
#Mann= 3 ,-1 , 0
  4872.1     .05       0  5006.9     .05       0  5010.9     .05       0
Bank Sta=5006.9,5010.9
XS Rating Curve= 0 ,0
Exp/Cntr=0.3,0.1

Type RM Length L Ch R = 1 ,1408    ,261,261,261
BEGIN DESCRIPTION:
Unnamed 5 Tr 1_2 5.0
END DESCRIPTION:
XS GIS Cut Line= 3
      2401228.98        7056560.        2401029.        7056510.
      2400929.01      7056659.99
#Sta/Elev= 30
  4793.9   620.2  4811.9  618.61  4824.8   618.1  4835.1  615.48  4858.3  614.33
  4886.7  614.42  4899.5  613.69  4907.3  612.53  4948.5  609.52    4982  608.34
  4997.5  606.35  5007.5  606.24  5011.6  605.02  5011.8  604.52  5015.3  604.52
  5015.6  605.02  5022.6  605.56  5028.6   610.2  5036.1  608.88  5049.6  609.69
  5058.6  609.25  5064.6  610.46  5072.1  609.48  5079.7  609.35  5094.7  610.19
  5100.7  611.82  5115.7  613.24  5121.7  614.91  5144.3  616.05  5180.3   616.9
#Mann= 3 ,-1 , 0
  4793.9     .05       0  5011.6    .033       0  5015.6     .05       0
Bank Sta=5011.6,5015.6
XS Rating Curve= 0 ,0
Exp/Cntr=0.3,0.1

Type RM Length L Ch R = 1 ,1147    ,61,61,61
BEGIN DESCRIPTION:
Unnamed 5 Tr 1_2 4.0
END DESCRIPTION:
XS GIS Cut Line= 4
      2401206.14      7056288.73      2400928.76      7056286.12
      2400866.08      7056285.69      2400736.81      7056347.59
#Sta/Elev= 30
  4722.6   614.7  4739.7  612.43  4749.7  611.58  4789.7  611.52  4809.7  612.31
  4819.7  611.97  4839.7  609.96  4909.8  606.91  4929.8     605  4939.8  604.69
  4959.8  602.46  4969.8  599.01  4977.8  595.41    4978  594.91  4981.5  594.91
  4981.8  595.41  4989.8  596.79  4997.4  601.25  5002.4  601.25  5009.8  604.75
  5049.8  606.99  5070.5  607.49  5080.1  607.33  5085.7  608.59  5102.8  609.08
  5108.4  609.81  5125.5  610.06  5148.1  611.06  5159.2     612    5206  611.76
#Mann= 3 ,-1 , 0
  4722.6     .05       0  4977.8     .05       0  4981.8     .05       0
Bank Sta=4977.8,4981.8
XS Rating Curve= 0 ,0
Exp/Cntr=0.3,0.1

Type RM Length L Ch R = 1 ,1086    ,254,254,254
BEGIN DESCRIPTION:
Mapping XS 5aa9ffb1
END DESCRIPTION:
XS GIS Cut Line= 4
       2401214.4      7056230.05      2400928.32      7056225.19
       2400843.6      7056227.27      2400708.16      7056307.15
#Sta/Elev= 30
  4714.6  615.71    4730  613.92    4740  611.68    4760  610.43    4790  610.44
    4810  612.32    4820  612.14    4900  608.36    4940  605.71    4970  602.38
    4980  596.68    4988  593.94  4988.3  593.44  4991.8  593.44    4992  593.94
  4997.9  597.66  5002.9  597.66    5010  602.09  5098.6  603.93  5104.4  605.12
  5157.2  606.47  5172.1  607.47  5178.6   606.2  5184.5  607.93  5194.3  607.38
  5200.1  609.17  5215.7  608.98  5221.6  609.79  5237.2  609.01  5242.7   609.4
#Mann= 3 ,-1 , 0
  4714.6     .05       0    4988     .05       0    4992     .05       0
Bank Sta=4988,4992
XS Rating Curve= 0 ,0
Exp/Cntr=0.3,0.1

Type RM Length L Ch R = 1 ,832     ,297,297,297
BEGIN DESCRIPTION:
Unnamed 5 Tr 1_2 3.0
END DESCRIPTION:
XS GIS Cut Line= 3
      2400934.15       7055898.7        2400829.        7056010.
      2400729.01      7056209.98
#Sta/Elev= 30
  4847.1   607.6  4851.5  607.98  4858.8  607.72    4894   607.7  4901.3  607.25
  4915.5   605.4  4929.6  602.37  4936.5  599.21  4943.8  591.46  4948.7  590.42
  4948.9  589.92  4952.4  589.92  4952.7  590.42  4964.8  591.38  4972.1  594.71
  4986.3  597.11  4993.1  596.43    5003  596.46  5008.6   596.8  5014.2  596.47
    5031  596.76  5044.9  597.24  5072.9   600.1  5134.4  604.13  5142.8  604.28
  5148.4  605.12  5170.7  605.45  5180.9  605.92  5193.1   606.7  5223.8  607.55
#Mann= 5 ,-1 , 0
  4847.1     .05       0  4948.7    .033       0  4952.7     .05       0
  5072.9     .12       0  5180.9     .05       0
Bank Sta=4948.7,4952.7
XS Rating Curve= 0 ,0
Exp/Cntr=0.3,0.1

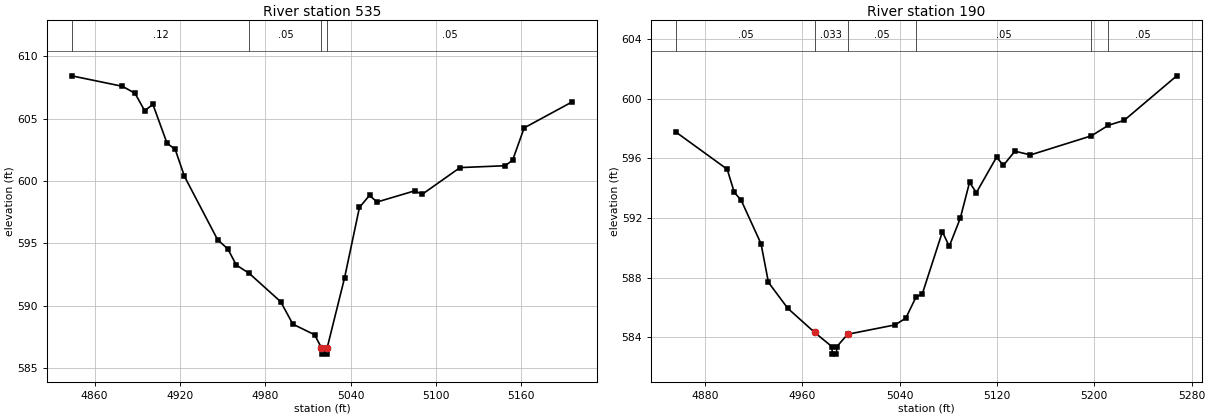
Type RM Length L Ch R = 1 ,535     ,345,345,345
BEGIN DESCRIPTION:
Unnamed 5 Tr 1_2 2.0
END DESCRIPTION:
XS GIS Cut Line= 3
      2400660.68      7055731.73       2400581.2      7055866.08
      2400520.08      7056051.99
#Sta/Elev= 30
  4843.9  608.42  4879.6  607.58  4888.4  607.02  4895.2  605.63    4901  606.13
  4910.9  603.03  4916.7  602.52  4923.2  600.36  4946.5  595.29  4953.7  594.55
  4959.6  593.27  4968.8  592.59  4990.8  590.33  4999.4  588.53  5014.7  587.68
  5019.5  586.63  5019.7  586.13  5023.2  586.13  5023.5  586.63  5035.7  592.22
  5046.2  597.88  5053.3  598.85  5058.5  598.31  5085.1  599.21  5090.3  598.93
  5116.9  601.07  5148.7  601.22  5153.9  601.67    5162  604.25  5195.7  606.33
#Mann= 4 ,-1 , 0
  4843.9     .12       0  4968.8     .05       0  5019.5    .033       0
  5023.5     .05       0
Bank Sta=5019.5,5023.5
XS Rating Curve= 0 ,0
Exp/Cntr=0.3,0.1

Type RM Length L Ch R = 1 ,190     ,0,0,0
BEGIN DESCRIPTION:
Unnamed 5 Tr 1_2 1.0
END DESCRIPTION:
XS GIS Cut Line= 3
      2400326.44      7055663.12      2400259.04      7055789.91
      2400380.23      7056028.61
#Sta/Elev= 30
  4856.4  597.73  4898.2  595.26    4904  593.72  4909.7  593.18    4926  590.27
  4932.1  587.68    4948  585.94    4970  584.33  4984.3  583.37  4984.5  582.87
    4988  582.87  4988.3  583.37  4997.2   584.2  5036.2  584.83    5045  585.28
  5053.5  586.71  5058.5  586.89  5075.1  591.07  5080.7  590.09  5089.8  591.98
  5097.4  594.38    5103  593.69  5119.6  596.07  5125.2  595.52  5134.7  596.47
  5147.5  596.22  5197.6   597.5  5211.6  598.21  5224.4  598.53  5267.7  601.52
#Mann= 6 ,-1 , 0
  4856.4     .05       0    4970    .033       0  4997.2     .05       0
  5053.5     .05       0  5197.6     .12       0  5211.6     .05       0
Bank Sta=4970,4997.2
XS Rating Curve= 0 ,0
Exp/Cntr=0.3,0.1

Chan Stop Cuts=-1
Use User Specified Reach Order=0
Composite Channel Slope=5