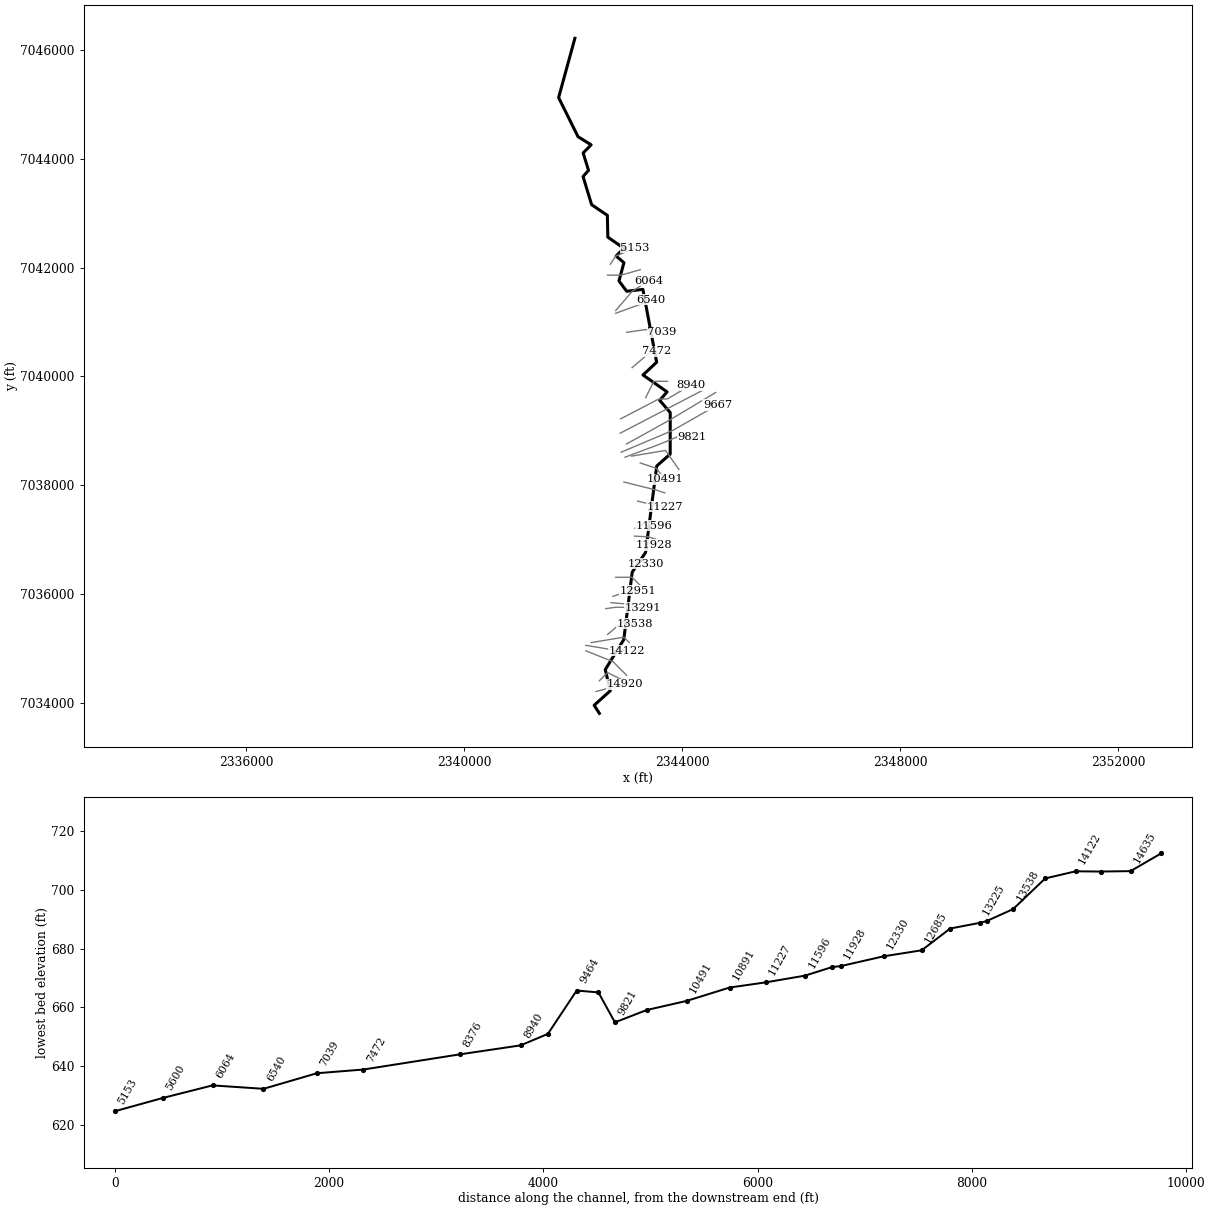
--- Unnamed Tr of Henrietta Cr.prj (project) ---

Proj Title=Unnamed Tr of Henrietta Cr Base Level Engineering
Current Plan=p01
Default Exp/Contr=0.3,0.1
English Units
Geom File=g01
Flow File=f01
Plan File=p01
BEGIN DESCRIPTION:
Unnamed Tr of Henrietta Cr
END DESCRIPTION:

--- Unnamed Tr of Henrietta Cr.p01 (plan) ---

Plan Title=Multiple Run
Short Identifier=Multiple
Geom File=g01
Flow File=f01
Subcritical Flow
K Sum by GR= 0
Std Step Tol= 0.01
Critical Tol= 0.01
Num of Std Step Trials= 20
Max Error Tol= 0.3
Flow Tol Ratio= 0.001
Split Flow NTrial= 30
Split Flow Tol= 0.02
Split Flow Ratio= 0.02
Log Output Level= 0
Friction Slope Method= 0
Unsteady Friction Slope Method= 2
Unsteady Bridges Friction Slope Method= 1
Parabolic Critical Depth
Global Vel Dist=  1 , 1 , 1
Global Log Level= 0
CheckData=True
Encroach Param= -1, 0, 0, 0
BEGIN DESCRIPTION:
Multiple Run
END DESCRIPTION:

--- Unnamed Tr of Henrietta Cr.f01 (steady flow) ---

Flow Title=Multiple
Number of Profiles=7
Profile Names=10-year,25-year,50-year,1pct_min,100-year,1pct_plu,500-year
River Rch & RM= Unnamed Tr of He,Reach-1,14920
     529     718     872     526    1050    2090    1520
River Rch & RM= Unnamed Tr of He,Reach-1,12330
     618     847    1030     627    1250    2500    1830
River Rch & RM= Unnamed Tr of He,Reach-1,9821
     788    1090    1350     826    1650    3290    2460
River Rch & RM= Unnamed Tr of He,Reach-1,9195
    1090    1540    1920    1190    2370    4730    3610
River Rch & RM= Unnamed Tr of He,Reach-1,7472
    1280    1820    2280    1410    2820    5620    4320
Boundary for River Rch & Prof#=Unnamed Tr of He,Reach-1,1
Up Type=0
Dn Type=3
Dn Slope=0.005
Boundary for River Rch & Prof#=Unnamed Tr of He,Reach-1,2
Up Type=0
Dn Type=3
Dn Slope=0.005
Boundary for River Rch & Prof#=Unnamed Tr of He,Reach-1,3
Up Type=0
Dn Type=3
Dn Slope=0.005
Boundary for River Rch & Prof#=Unnamed Tr of He,Reach-1,4
Up Type=0
Dn Type=3
Dn Slope=0.005
Boundary for River Rch & Prof#=Unnamed Tr of He,Reach-1,5
Up Type=0
Dn Type=3
Dn Slope=0.005
Boundary for River Rch & Prof#=Unnamed Tr of He,Reach-1,6
Up Type=0
Dn Type=3
Dn Slope=0.005
Boundary for River Rch & Prof#=Unnamed Tr of He,Reach-1,7
Up Type=0
Dn Type=3
Dn Slope=0.005

--- Unnamed Tr of Henrietta Cr.g01 (geometry) ---

Geom Title=Existing Conditions

River Reach=Unnamed Tr of He,Reach-1
Reach XY= 30
      2342479.00      7033810.00      2342382.53      7033958.53
      2342678.69      7034225.04      2342586.79      7034613.42
      2342926.74      7035165.94      2343081.24      7036404.07
      2343326.76      7036765.93      2343531.24      7038354.07
      2343778.13      7038572.51      2343779.49      7039335.21
      2343585.97      7039560.23      2343721.27      7039716.14
      2343279.12      7040025.77      2343529.96      7040260.30
      2343277.50      7041598.57      2342980.46      7041563.52
      2342838.41      7041753.38      2342929.31      7042089.66
      2342785.98      7042210.20      2342927.44      7042353.92
      2342634.09      7042557.69      2342625.46      7042958.54
      2342336.68      7043153.48      2342179.40      7043671.02
      2342279.53      7043784.88      2342180.97      7044104.32
      2342327.26      7044253.84      2342086.86      7044403.19
      2341730.64      7045121.83      2342029.00      7046210.00

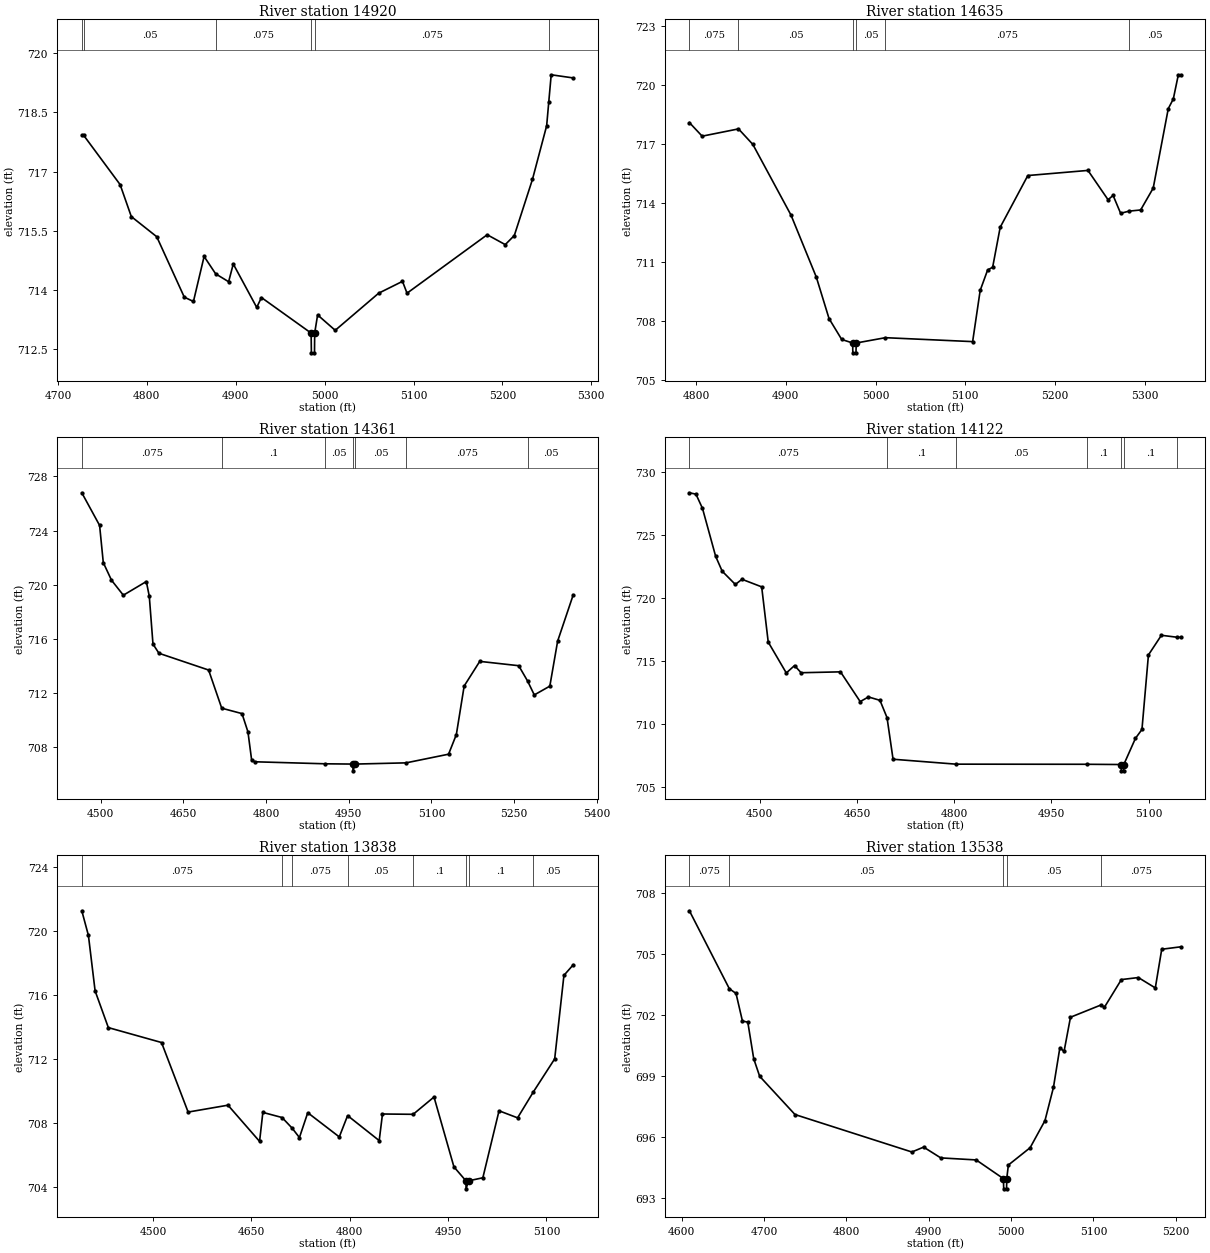
Type RM Length L Ch R = 1,14920,285,285,285
BEGIN DESCRIPTION:
Unnamed Tributary of Henrietta Creek 31.0
END DESCRIPTION:
XS GIS Cut Line= 5
      2342417.25      7034211.99      2342558.32      7034247.81
      2342687.73      7034290.95      2342802.54      7034311.36
      2342954.10      7034340.49
#Sta/Elev= 30
  4726.8  717.92  4728.8  717.92  4769.9  716.67  4782.5  715.86  4811.1  715.35
  4842.1  713.82  4852.4  713.71  4864.4  714.85  4877.4  714.41  4892.0  714.21
  4897.2  714.66  4923.6  713.56  4928.9  713.81  4984.8  712.91  4985.1  712.41
  4988.6  712.41  4988.8  712.91  4992.1  713.37  5011.9  712.98  5060.8  713.92
  5087.6  714.22  5092.7  713.92  5182.9  715.40  5203.2  715.15  5213.4  715.38
  5233.8  716.80  5249.8  718.16  5252.2  718.77  5254.9  719.45  5279.7  719.37
#Mann=6,-1,0
  4726.8   0.075       0  4728.8    0.05       0  4877.4   0.075       0
  4984.8    0.07       0  4988.8   0.075       0  5252.2    0.05       0
Bank Sta=4984.8,4988.8
Exp/Cntr=0.3,0.1

Type RM Length L Ch R = 1,14635,274,274,274
BEGIN DESCRIPTION:
Unnamed Tributary of Henrietta Creek 30.0
END DESCRIPTION:
XS GIS Cut Line= 3
      2342478.98      7034409.98      2342629.00      7034560.00
      2342929.03      7034409.98
#Sta/Elev= 30
  4792.6  718.08  4806.8  717.39  4847.3  717.76  4863.3  716.97  4905.8  713.38
  4934.0  710.23  4948.2  708.12  4962.3  707.06  4974.5  706.88  4974.7  706.38
  4978.2  706.38  4978.5  706.88  5011.0  707.15  5108.2  706.95  5116.6  709.55
  5124.9  710.59  5130.5  710.73  5138.9  712.76  5169.7  715.39  5236.7  715.65
  5259.1  714.16  5264.7  714.38  5273.1  713.47  5282.4  713.58  5295.4  713.64
  5309.4  714.75  5326.2  718.79  5331.8  719.28  5337.4  720.51  5340.2  720.51
#Mann=6,-1,0
  4792.6   0.075       0  4847.3    0.05       0  4974.5    0.05       0
  4978.5    0.05       0  5011.0   0.075       0  5282.4    0.05       0
Bank Sta=4974.5,4978.5
Exp/Cntr=0.3,0.1

Type RM Length L Ch R = 1,14361,239,239,239
BEGIN DESCRIPTION:
Unnamed Tributary of Henrietta Creek 29.0
END DESCRIPTION:
XS GIS Cut Line= 3
      2342229.00      7034960.00      2342729.00      7034760.00
      2342979.02      7034509.98
#Sta/Elev= 30
  4465.4  726.79  4497.7  724.38  4504.4  721.63  4519.3  720.33  4540.8  719.22
  4582.5  720.23  4587.9  719.15  4594.6  715.61  4605.4  714.93  4695.6  713.69
  4719.4  710.87  4756.2  710.47  4767.0  709.12  4773.7  707.04  4779.1  706.91
  4907.6  706.76  4957.5  706.74  4957.7  706.24  4961.5  706.74  5054.1  706.83
  5131.2  707.47  5145.3  708.92  5159.5  712.51  5187.8  714.33  5258.5  714.01
  5274.6  712.88  5286.8  711.85  5315.0  712.50  5329.2  715.83  5357.5  719.25
#Mann=7,-1,0
  4465.4   0.075       0  4719.4     0.1       0  4907.6    0.05       0
  4957.5   0.033       0  4961.5    0.05       0  5054.1   0.075       0
  5274.6    0.05       0
Bank Sta=4957.5,4961.5
Exp/Cntr=0.3,0.1

Type RM Length L Ch R = 1,14122,284,284,284
BEGIN DESCRIPTION:
Unnamed Tributary of Henrietta Creek 28.0
END DESCRIPTION:
XS GIS Cut Line= 3
      2342229.05      7035059.99      2342829.00      7034960.00
      2342978.97      7034960.00
#Sta/Elev= 30
  4391.4  728.37  4401.5  728.26  4411.6  727.13  4431.9  723.33  4442.0  722.15
  4462.3  721.10  4472.5  721.51  4502.9  720.91  4513.0  716.53  4540.9  714.08
  4553.6  714.67  4563.7  714.10  4624.5  714.17  4654.9  711.81  4667.6  712.18
  4685.4  711.91  4696.3  710.54  4705.6  707.24  4802.6  706.85  5004.2  706.84
  5057.6  706.82  5057.9  706.32  5061.4  706.32  5061.6  706.82  5079.6  708.90
  5089.6  709.60  5099.6  715.51  5119.6  717.07  5144.4  716.91  5149.6  716.91
#Mann=7,-1,0
  4391.4   0.075       0  4696.3     0.1       0  4802.6    0.05       0
  5004.2     0.1       0  5057.6   0.033       0  5061.6     0.1       0
  5144.4   0.075       0
Bank Sta=5057.6,5061.6
Exp/Cntr=0.3,0.1

Type RM Length L Ch R = 1,13838,300,300,300
BEGIN DESCRIPTION:
Unnamed Tributary of Henrietta Creek 27.0
END DESCRIPTION:
XS GIS Cut Line= 3
      2342329.02      7035110.00      2342929.00      7035210.00
      2343029.02      7035109.98
#Sta/Elev= 30
  4391.2  721.24  4401.3  719.70  4411.5  716.24  4431.7  713.95  4512.8  713.02
  4553.4  708.68  4614.2  709.11  4662.4  706.85  4667.4  708.66  4696.7  708.34
  4712.0  707.68  4723.2  707.09  4735.9  708.64  4784.0  707.13  4796.7  708.46
  4844.9  706.90  4849.9  708.56  4896.7  708.54  4928.5  709.62  4958.9  705.26
  4977.2  704.39  4977.4  703.89  4981.2  704.39  5003.0  704.58  5027.7  708.76
  5056.0  708.32  5080.1  709.94  5112.6  712.00  5126.7  717.21  5140.9  717.87
#Mann=8,-1,0
  4391.2   0.075       0  4696.7    0.05       0  4712.0   0.075       0
  4796.7    0.05       0  4896.7     0.1       0  4977.2    0.07       0
  4981.2     0.1       0  5080.1    0.05       0
Bank Sta=4977.2,4981.2
Exp/Cntr=0.3,0.1

Type RM Length L Ch R = 1,13538,247,247,247
BEGIN DESCRIPTION:
Unnamed Tributary of Henrietta Creek 26.0
END DESCRIPTION:
XS GIS Cut Line= 3
      2342629.00      7035260.00      2342929.00      7035510.00
      2343129.04      7035459.99
#Sta/Elev= 30
  4609.5  707.11  4658.0  703.28  4666.1  703.05  4673.9  701.69  4680.4  701.64
  4687.6  699.84  4694.8  698.98  4737.7  697.10  4879.6  695.26  4893.9  695.50
  4914.7  694.97  4957.7  694.87  4990.8  693.95  4991.1  693.45  4994.6  693.45
  4994.8  693.95  4996.8  694.62  5023.2  695.47  5041.2  696.80  5051.5  698.43
  5059.3  700.38  5064.4  700.20  5072.2  701.88  5109.1  702.48  5113.4  702.37
  5134.0  703.73  5154.6  703.83  5175.2  703.32  5183.0  705.22  5206.2  705.34
#Mann=5,-1,0
  4609.5   0.075       0  4658.0    0.05       0  4990.8    0.05       0
  4994.8    0.05       0  5109.1   0.075       0
Bank Sta=4990.8,4994.8
Exp/Cntr=0.3,0.1

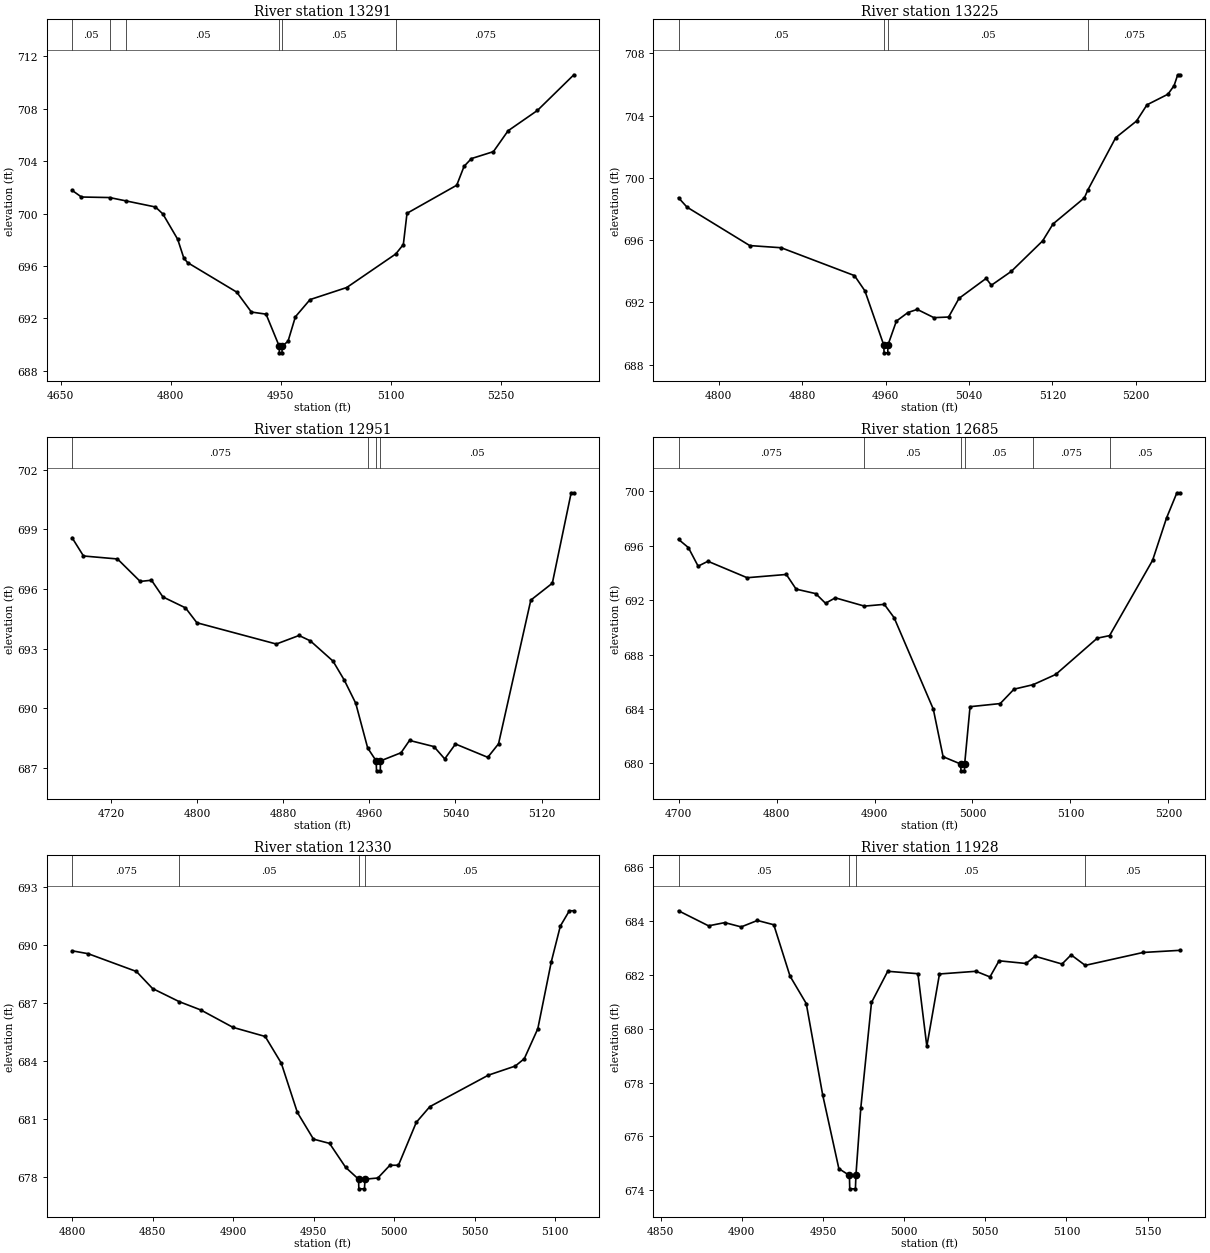
Type RM Length L Ch R = 1,13291,66,66,66
BEGIN DESCRIPTION:
Unnamed Tributary of Henrietta Creek 25.5
END DESCRIPTION:
XS GIS Cut Line= 3
      2342596.30      7035734.07      2342788.94      7035760.19
      2343278.64      7035750.40
#Sta/Elev= 30
  4665.6  701.77  4678.4  701.26  4716.7  701.22  4739.5  700.96  4779.3  700.50
  4789.4  699.97  4809.6  698.04  4818.0  696.60  4823.1  696.26  4890.1  694.01
  4910.1  692.49  4930.1  692.33  4948.1  689.88  4948.3  689.38  4951.8  689.38
  4952.1  689.88  4960.1  690.27  4970.1  692.13  4990.1  693.44  5040.1  694.36
  5107.0  696.92  5117.3  697.64  5122.3  700.02  5190.1  702.16  5200.1  703.60
  5210.1  704.19  5240.1  704.72  5260.1  706.31  5300.1  707.86  5349.8  710.58
#Mann=6,-1,0
  4665.6    0.05       0  4716.7   0.075       0  4739.5    0.05       0
  4948.1    0.05       0  4952.1    0.05       0  5107.0   0.075       0
Bank Sta=4948.1,4952.1
Exp/Cntr=0.3,0.1

Type RM Length L Ch R = 1,13225,274,274,274
BEGIN DESCRIPTION:
Unnamed Tributary of Henrietta Creek 25.0
END DESCRIPTION:
XS GIS Cut Line= 3
      2342690.95      7035845.08      2342935.87      7035822.22
      2343170.93      7035835.28
#Sta/Elev= 30
  4761.4  698.72  4769.5  698.12  4829.7  695.65  4859.9  695.51  4930.2  693.72
  4940.2  692.74  4958.3  689.26  4958.6  688.76  4962.1  688.76  4962.3  689.26
  4970.4  690.80  4981.5  691.35  4990.4  691.55  5006.4  691.02  5020.5  691.06
  5030.5  692.26  5056.5  693.54  5061.5  693.10  5080.6  693.99  5110.7  695.95
  5120.7  697.04  5150.7  698.71  5154.0  699.21  5180.8  702.58  5200.8  703.65
  5210.8  704.69  5230.9  705.37  5236.8  705.92  5240.3  706.62  5242.8  706.62
#Mann=4,-1,0
  4761.4    0.05       0  4958.3    0.05       0  4962.3    0.05       0
  5154.0   0.075       0
Bank Sta=4958.3,4962.3
Exp/Cntr=0.3,0.1

Type RM Length L Ch R = 1,12951,266,266,266
BEGIN DESCRIPTION:
Unnamed Tributary of Henrietta Creek 24.0
END DESCRIPTION:
XS GIS Cut Line= 3
      2342728.96      7035959.99      2343029.00      7036060.00
      2343179.03      7036060.00
#Sta/Elev= 30
  4683.7  698.58  4694.3  697.66  4725.9  697.51  4747.0  696.38  4757.5  696.44
  4768.1  695.60  4789.1  695.05  4799.7  694.30  4873.5  693.23  4894.6  693.66
  4905.1  693.39  4926.2  692.37  4936.7  691.41  4947.3  690.25  4958.4  688.00
  4966.3  687.35  4966.6  686.85  4970.1  686.85  4970.3  687.35  4989.4  687.76
  4997.3  688.38  5020.0  688.07  5030.0  687.45  5040.0  688.20  5070.0  687.53
  5080.0  688.21  5110.0  695.44  5130.0  696.29  5147.5  700.84  5150.0  700.84
#Mann=4,-1,0
  4683.7   0.075       0  4958.4    0.05       0  4966.3    0.05       0
  4970.3    0.05       0
Bank Sta=4966.3,4970.3
Exp/Cntr=0.3,0.1

Type RM Length L Ch R = 1,12685,355,355,355
BEGIN DESCRIPTION:
Unnamed Tributary of Henrietta Creek 23.0
END DESCRIPTION:
XS GIS Cut Line= 3
      2342779.00      7036310.00      2343079.00      7036310.00
      2343228.98      7036160.02
#Sta/Elev= 30
  4700.0  696.47  4710.0  695.87  4720.0  694.50  4730.0  694.86  4770.0  693.65
  4810.0  693.89  4820.0  692.81  4840.0  692.48  4850.0  691.77  4860.0  692.17
  4889.7  691.56  4910.0  691.69  4920.0  690.71  4960.0  683.98  4970.0  680.48
  4988.0  679.94  4988.2  679.44  4991.7  679.44  4992.0  679.94  4997.5  684.16
  5028.3  684.39  5042.4  685.45  5061.9  685.78  5084.9  686.53  5127.3  689.20
  5139.9  689.39  5183.8  694.93  5198.0  698.04  5208.6  699.90  5212.1  699.90
#Mann=6,-1,0
  4700.0   0.075       0  4889.7    0.05       0  4988.0    0.05       0
  4992.0    0.05       0  5061.9   0.075       0  5139.9    0.05       0
Bank Sta=4988,4992
Exp/Cntr=0.3,0.1

Type RM Length L Ch R = 1,12330,402,402,402
BEGIN DESCRIPTION:
Unnamed Tributary of Henrietta Creek 22.0
END DESCRIPTION:
XS GIS Cut Line= 3
      2343029.04      7036610.00      2343229.00      7036610.00
      2343329.03      7036559.98
#Sta/Elev= 30
  4799.8  689.71  4809.8  689.56  4839.8  688.64  4849.8  687.76  4866.4  687.08
  4879.8  686.65  4899.8  685.75  4919.8  685.28  4929.8  683.90  4939.8  681.35
  4949.8  679.97  4959.8  679.75  4969.8  678.51  4977.8  677.90  4978.0  677.40
  4981.5  677.40  4981.8  677.90  4989.8  677.96  4997.3  678.62  5002.6  678.62
  5013.7  680.84  5022.1  681.65  5058.5  683.28  5075.2  683.75  5080.8  684.13
  5089.2  685.68  5097.6  689.15  5103.2  690.99  5108.8  691.78  5111.6  691.78
#Mann=4,-1,0
  4799.8   0.075       0  4866.4    0.05       0  4977.8    0.05       0
  4981.8    0.05       0
Bank Sta=4977.8,4981.8
Exp/Cntr=0.3,0.1

Type RM Length L Ch R = 1,11928,78,78,78
BEGIN DESCRIPTION:
Unnamed Tributary of Henrietta Creek 21.0
END DESCRIPTION:
XS GIS Cut Line= 3
      2343190.58      7036964.97      2343334.19      7036978.03
      2343481.11      7036902.94
#Sta/Elev= 30
  4861.0  684.39  4879.5  683.83  4889.5  683.95  4899.6  683.79  4909.6  684.03
  4919.7  683.87  4929.7  681.96  4939.7  680.94  4949.8  677.55  4959.8  674.80
  4966.3  674.55  4966.5  674.05  4970.0  674.05  4970.3  674.55  4973.3  677.05
  4979.9  680.98  4989.9  682.14  5008.5  682.05  5014.0  679.35  5021.8  682.04
  5044.3  682.14  5052.9  681.93  5058.5  682.53  5075.1  682.43  5080.7  682.70
  5097.3  682.41  5102.9  682.75  5111.6  682.36  5147.3  682.84  5170.2  682.92
#Mann=4,-1,0
  4861.0    0.05       0  4966.3    0.07       0  4970.3    0.05       0
  5111.6    0.05       0
Bank Sta=4966.3,4970.3
Exp/Cntr=0.3,0.1

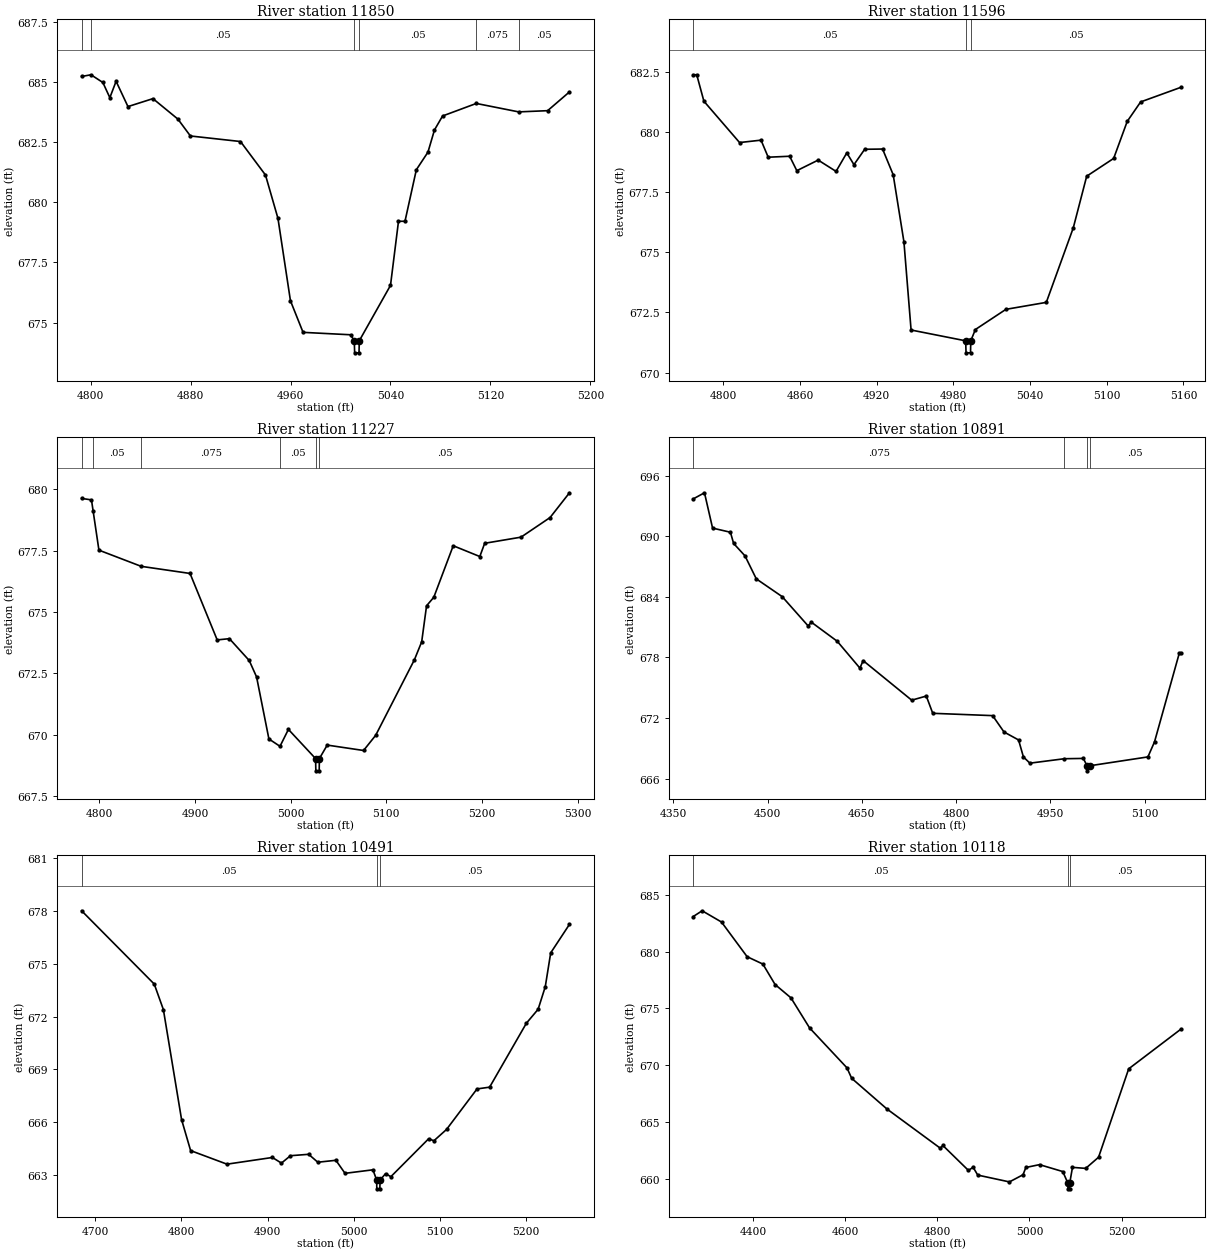
Type RM Length L Ch R = 1,11850,254,254,254
BEGIN DESCRIPTION:
Unnamed Tributary of Henrietta Creek 21.5
END DESCRIPTION:
XS GIS Cut Line= 3
      2343121.98      7037066.18      2343376.64      7037053.12
      2343505.60      7037011.21
#Sta/Elev= 30
  4792.7  685.22  4800.2  685.29  4809.7  684.97  4815.3  684.34  4820.3  685.02
  4829.8  683.97  4849.8  684.30  4869.8  683.45  4879.8  682.75  4919.9  682.52
  4939.9  681.13  4949.9  679.33  4959.9  675.91  4970.0  674.60  5008.0  674.50
  5011.0  674.25  5011.3  673.75  5014.8  673.75  5015.0  674.25  5040.0  676.55
  5046.4  679.21  5051.6  679.21  5060.7  681.35  5070.0  682.08  5075.2  683.00
  5081.7  683.58  5108.7  684.10  5142.6  683.75  5165.8  683.80  5183.3  684.58
#Mann=6,-1,0
  4792.7   0.075       0  4800.2    0.05       0  5011.0    0.05       0
  5015.0    0.05       0  5108.7   0.075       0  5142.6    0.05       0
Bank Sta=5011,5015
Exp/Cntr=0.3,0.1

Type RM Length L Ch R = 1,11596,369,369,369
BEGIN DESCRIPTION:
Unnamed Tributary of Henrietta Creek 20.0
END DESCRIPTION:
XS GIS Cut Line= 3
      2343128.99      7037210.00      2343329.00      7037310.00
      2343478.97      7037260.01
#Sta/Elev= 30
  4776.4  682.39  4779.2  682.39  4784.8  681.29  4812.7  679.57  4829.5  679.67
  4835.1  678.96  4851.9  679.00  4857.5  678.40  4874.2  678.84  4888.2  678.37
  4896.6  679.14  4902.2  678.65  4910.6  679.29  4924.6  679.30  4932.9  678.23
  4941.3  675.44  4946.9  671.77  4989.6  671.32  4989.9  670.82  4993.4  670.82
  4993.6  671.32  4997.2  671.79  5021.1  672.63  5052.7  672.92  5073.8  676.02
  5084.3  678.17  5105.4  678.91  5116.0  680.45  5126.5  681.26  5158.1  681.87
#Mann=3,-1,0
  4776.4    0.05       0  4989.6    0.05       0  4993.6    0.05       0
Bank Sta=4989.6,4993.6
Exp/Cntr=0.3,0.1

Type RM Length L Ch R = 1,11227,336,336,336
BEGIN DESCRIPTION:
Unnamed Tributary of Henrietta Creek 19.0
END DESCRIPTION:
XS GIS Cut Line= 3
      2343178.98      7037710.00      2343379.00      7037660.00
      2343678.99      7037610.00
#Sta/Elev= 30
  4781.3  679.63  4791.6  679.57  4793.4  679.10  4799.4  677.52  4843.6  676.86
  4894.7  676.57  4923.1  673.86  4935.9  673.91  4956.6  673.02  4964.3  672.35
  4977.2  669.82  4988.8  669.52  4997.6  670.21  5026.0  669.02  5026.3  668.52
  5029.8  668.52  5030.0  669.02  5038.2  669.57  5076.2  669.35  5088.9  669.97
  5129.4  673.05  5137.0  673.78  5142.1  675.25  5149.7  675.60  5170.0  677.70
  5197.8  677.26  5202.9  677.80  5240.9  678.05  5271.3  678.85  5291.6  679.86
#Mann=6,-1,0
  4781.3   0.075       0  4793.4    0.05       0  4843.6   0.075       0
  4988.8    0.05       0  5026.0    0.05       0  5030.0    0.05       0
Bank Sta=5026,5030
Exp/Cntr=0.3,0.1

Type RM Length L Ch R = 1,10891,400,400,400
BEGIN DESCRIPTION:
Unnamed Tributary of Henrietta Creek 18.0
END DESCRIPTION:
XS GIS Cut Line= 3
      2342929.00      7038060.00      2343529.00      7037910.00
      2343679.02      7037859.99
#Sta/Elev= 30
  4381.5  693.70  4399.5  694.31  4412.4  690.81  4440.8  690.40  4445.9  689.29
  4464.0  688.06  4482.0  685.78  4523.2  684.02  4564.5  681.12  4569.6  681.49
  4610.8  679.60  4646.9  676.94  4652.1  677.68  4729.4  673.76  4752.6  674.17
  4762.9  672.46  4858.2  672.23  4876.3  670.61  4899.5  669.82  4907.2  668.14
  4917.5  667.52  4972.4  667.96  5002.6  667.99  5008.5  667.26  5008.8  666.76
  5012.5  667.26  5105.4  668.14  5115.9  669.63  5155.4  678.43  5158.1  678.43
#Mann=4,-1,0
  4381.5   0.075       0  4972.4    0.05       0  5008.5    0.05       0
  5012.5    0.05       0
Bank Sta=5008.5,5012.5
Exp/Cntr=0.3,0.1

Type RM Length L Ch R = 1,10491,373,373,373
BEGIN DESCRIPTION:
Unnamed Tributary of Henrietta Creek 17.0
END DESCRIPTION:
XS GIS Cut Line= 3
      2343229.00      7038410.00      2343529.00      7038310.00
      2343678.98      7038110.02
#Sta/Elev= 30
  4684.2  678.00  4768.5  673.84  4779.1  672.39  4800.2  666.15  4810.7  664.39
  4852.9  663.62  4905.6  664.00  4916.1  663.68  4926.6  664.10  4947.7  664.18
  4958.3  663.73  4979.3  663.84  4989.9  663.10  5022.3  663.30  5026.6  662.72
  5026.8  662.22  5030.3  662.22  5030.6  662.72  5036.9  663.08  5043.1  662.91
  5086.9  665.06  5093.1  664.95  5107.7  665.59  5143.1  667.89  5157.7  667.99
  5200.4  671.62  5214.0  672.41  5222.3  673.69  5228.6  675.61  5250.4  677.23
#Mann=3,-1,0
  4684.2    0.05       0  5026.6   0.033       0  5030.6    0.05       0
Bank Sta=5026.6,5030.6
Exp/Cntr=0.3,0.1

Type RM Length L Ch R = 1,10118,297,297,297
BEGIN DESCRIPTION:
Unnamed Tributary of Henrietta Creek 16.0
END DESCRIPTION:
XS GIS Cut Line= 3
      2343069.75      7038535.43      2343693.34      7038639.91
      2343938.21      7038290.56
#Sta/Elev= 30
  4270.1  683.08  4289.6  683.59  4331.6  682.60  4387.2  679.55  4421.4  678.90
  4447.9  677.10  4482.3  675.93  4522.8  673.28  4603.9  669.77  4614.1  668.85
  4690.6  666.15  4806.7  662.69  4812.0  662.94  4867.6  660.74  4877.7  661.02
  4887.8  660.33  4956.5  659.73  4986.1  660.36  4992.2  661.00  5021.9  661.25
  5072.4  660.64  5083.4  659.62  5083.7  659.12  5087.2  659.12  5087.4  659.62
  5093.4  661.01  5122.1  660.92  5150.0  661.90  5215.4  669.68  5329.0  673.18
#Mann=3,-1,0
  4270.1    0.05       0  5083.4   0.033       0  5087.4    0.05       0
Bank Sta=5083.4,5087.4
Exp/Cntr=0.3,0.1

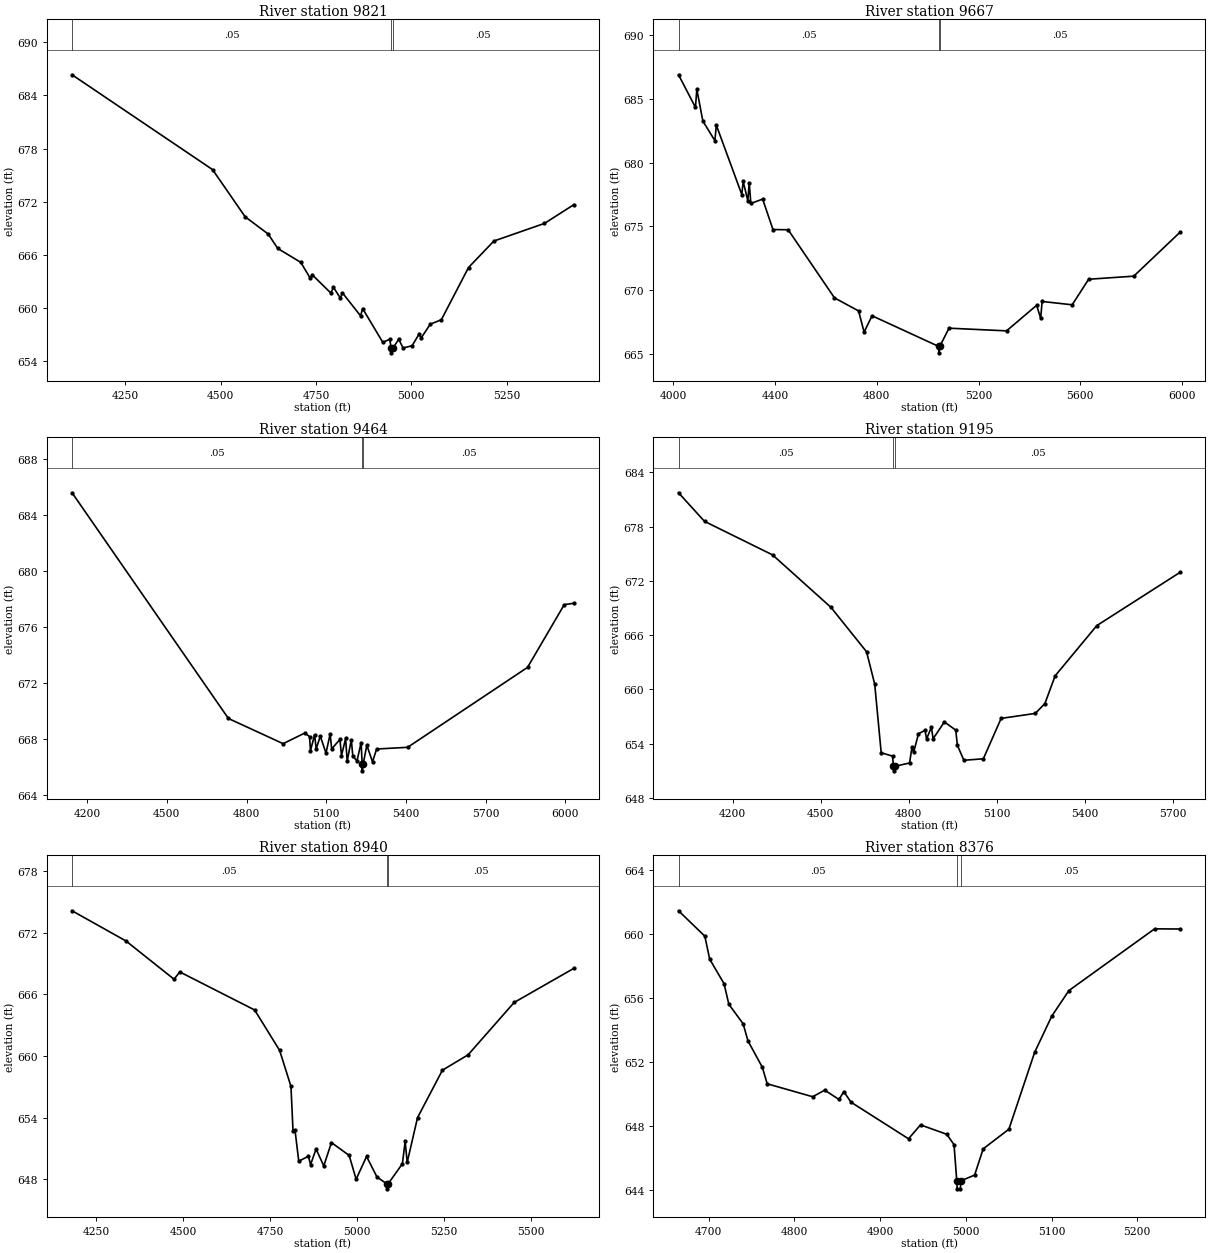
Type RM Length L Ch R = 1,9821,154,154,154
BEGIN DESCRIPTION:
Unnamed Tributary of Henrietta Creek 15.5
END DESCRIPTION:
XS GIS Cut Line= 4
      2342948.89      7038515.82      2343585.60      7038754.18
      2343990.46      7038923.96      2344185.19      7038891.50
#Sta/Elev= 30
  4110.4  686.33  4478.9  675.62  4564.4  670.29  4624.9  668.34  4649.9  666.71
  4710.4  665.14  4735.4  663.33  4740.7  663.72  4789.4  661.67  4795.9  662.33
  4814.2  661.11  4819.6  661.70  4867.2  659.10  4872.6  659.92  4925.6  656.10
  4943.9  656.46  4947.4  655.42  4947.6  654.92  4951.4  655.42  4967.4  656.45
  4978.6  655.47  5002.3  655.72  5020.7  657.04  5026.1  656.60  5049.9  658.15
  5079.1  658.66  5150.4  664.56  5216.9  667.55  5349.6  669.54  5426.7  671.66
#Mann=3,-1,0
  4110.4    0.05       0  4947.4    0.05       0  4951.4    0.05       0
Bank Sta=4947.4,4951.4
Exp/Cntr=0.3,0.1

Type RM Length L Ch R = 1,9667,203,203,203
BEGIN DESCRIPTION:
Unnamed Tributary of Henrietta Creek 15.0
END DESCRIPTION:
XS GIS Cut Line= 3
      2342877.11      7038607.26      2343827.21      7039008.85
      2344644.75      7039474.62
#Sta/Elev= 30
  4020.6  686.87  4087.1  684.32  4092.5  685.73  4116.2  683.25  4163.6  681.71
  4169.1  682.93  4269.3  677.50  4274.7  678.52  4293.0  677.01  4298.4  678.42
  4304.9  676.80  4351.2  677.14  4391.8  674.76  4451.5  674.74  4633.6  669.41
  4728.3  668.39  4750.0  666.73  4781.3  668.01  5043.4  665.61  5043.7  665.11
  5047.4  665.61  5083.8  667.04  5310.0  666.83  5428.2  668.83  5444.0  667.82
  5449.8  669.13  5567.9  668.87  5632.7  670.87  5810.0  671.11  5993.0  674.57
#Mann=3,-1,0
  4020.6    0.05       0  5043.4   0.033       0  5047.4    0.05       0
Bank Sta=5043.4,5047.4
Exp/Cntr=0.3,0.1

Type RM Length L Ch R = 1,9464,269,269,269
BEGIN DESCRIPTION:
Unnamed Tributary of Henrietta Creek 14.0
END DESCRIPTION:
XS GIS Cut Line= 3
      2342979.04      7038760.02      2343757.78      7039191.77
      2344614.01      7039704.26
#Sta/Elev= 30
  4143.3  685.61  4731.6  669.49  4937.6  667.69  5018.9  668.45  5036.9  668.20
  5040.5  667.19  5056.0  668.33  5061.9  667.31  5077.4  668.23  5098.8  667.02
  5114.4  668.38  5120.2  667.32  5151.3  667.99  5157.2  666.84  5172.7  668.06
  5178.6  666.44  5194.1  667.97  5199.9  666.79  5215.5  666.46  5231.1  667.77
  5234.9  666.25  5235.2  665.75  5238.9  666.25  5252.5  667.58  5273.9  666.39
  5289.4  667.31  5406.1  667.43  5857.3  673.14  5995.4  677.62  6031.6  677.72
#Mann=3,-1,0
  4143.3    0.05       0  5234.9   0.033       0  5238.9    0.05       0
Bank Sta=5234.9,5238.9
Exp/Cntr=0.3,0.1

Type RM Length L Ch R = 1,9195,255,255,255
BEGIN DESCRIPTION:
Unnamed Tributary of Henrietta Creek 13.8
END DESCRIPTION:
XS GIS Cut Line= 2
      2342860.75      7038956.60      2344377.36      7039745.89
#Sta/Elev= 30
  4015.7  681.74  4104.2  678.58  4336.1  674.87  4535.0  669.07  4656.3  664.16
  4684.1  660.58  4706.2  652.99  4744.8  652.62  4748.1  651.49  4748.6  650.99
  4752.8  651.49  4802.9  651.86  4811.1  653.62  4816.7  653.04  4833.2  655.09
  4855.3  655.47  4860.9  654.53  4877.4  655.81  4883.0  654.54  4921.6  656.40
  4960.2  655.49  4965.8  653.81  4987.9  652.16  5054.2  652.32  5114.9  656.79
  5231.2  657.34  5264.0  658.43  5298.9  661.50  5440.8  667.05  5725.4  672.96
#Mann=3,-1,0
  4015.7    0.05       0  4748.1   0.033       0  4752.8    0.05       0
Bank Sta=4748.1,4752.8
Exp/Cntr=0.3,0.1

Type RM Length L Ch R = 1,8940,564,564,564
BEGIN DESCRIPTION:
Unnamed Tributary of Henrietta Creek 13.5
END DESCRIPTION:
XS GIS Cut Line= 4
      2342870.56      7039221.07      2343566.01      7039583.49
      2343729.26      7039586.75      2344155.52      7039840.55
#Sta/Elev= 30
  4180.2  674.14  4335.4  671.20  4473.6  667.48  4490.1  668.19  4705.4  664.49
  4777.3  660.56  4809.9  657.06  4815.9  652.69  4821.5  652.81  4832.4  649.78
  4860.1  650.26  4866.3  649.45  4882.2  650.96  4904.3  649.32  4926.4  651.59
  4977.4  650.34  4997.4  648.02  5027.4  650.24  5057.4  648.24  5085.1  647.59
  5085.6  647.09  5089.8  647.59  5130.5  649.53  5138.5  651.71  5144.3  649.66
  5174.0  654.01  5245.6  658.63  5319.6  660.13  5452.0  665.22  5623.8  668.54
#Mann=3,-1,0
  4180.2    0.05       0  5085.1   0.033       0  5089.8    0.05       0
Bank Sta=5085.1,5089.8
Exp/Cntr=0.3,0.1

Type RM Length L Ch R = 1,8376,904,904,904
BEGIN DESCRIPTION:
Unnamed Tributary of Henrietta Creek 13.0
END DESCRIPTION:
XS GIS Cut Line= 3
      2343329.01      7039610.02      2343479.00      7039910.00
      2343729.02      7039910.00
#Sta/Elev= 30
  4664.8  661.44  4695.5  659.85  4701.1  658.42  4717.9  656.88  4723.5  655.59
  4740.2  654.37  4745.8  653.30  4762.6  651.65  4768.2  650.62  4821.3  649.81
  4835.3  650.22  4852.0  649.64  4857.6  650.13  4866.0  649.47  4933.1  647.18
  4947.1  648.05  4977.8  647.46  4986.2  646.81  4989.4  644.55  4989.9  644.05
  4993.6  644.05  4994.1  644.55  5010.2  644.91  5020.2  646.55  5050.2  647.78
  5080.2  652.58  5100.2  654.85  5120.2  656.45  5220.2  660.31  5250.2  660.30
#Mann=3,-1,0
  4664.8    0.05       0  4989.4    0.04       0  4994.1    0.05       0
Bank Sta=4989.4,4994.1
Exp/Cntr=0.3,0.1

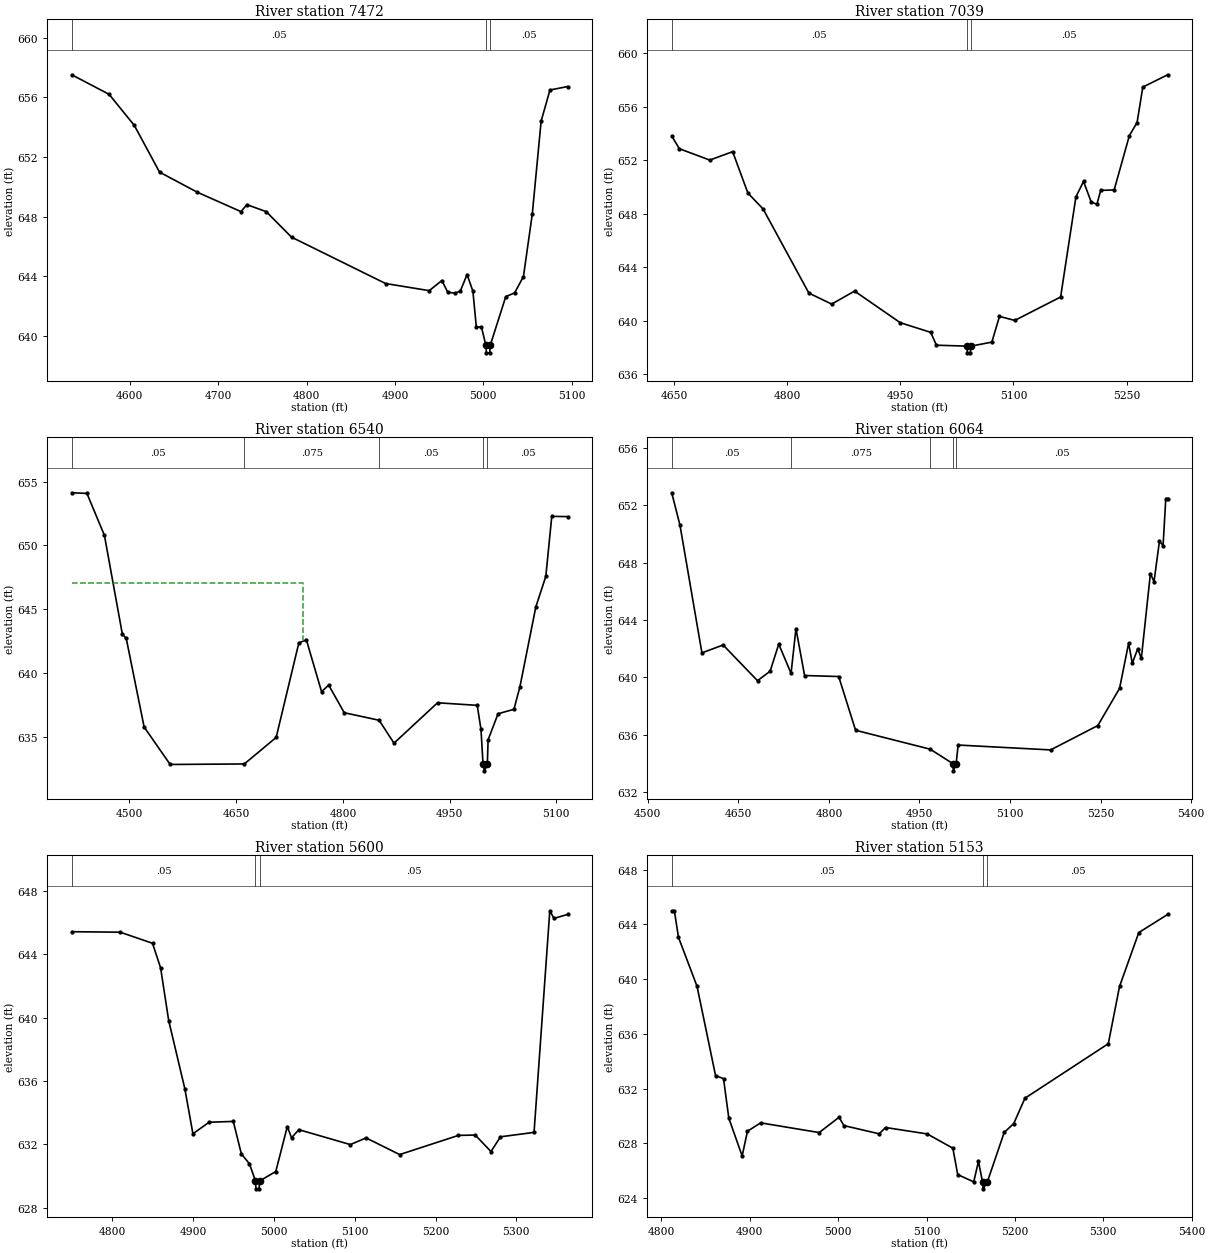
Type RM Length L Ch R = 1,7472,433,433,433
BEGIN DESCRIPTION:
Unnamed Tributary of Henrietta Creek 12.0
END DESCRIPTION:
XS GIS Cut Line= 3
      2343079.02      7040160.02      2343429.00      7040460.00
      2343529.05      7040460.00
#Sta/Elev= 30
  4534.4  657.52  4576.6  656.21  4605.2  654.12  4633.7  650.99  4676.5  649.64
  4725.9  648.34  4732.5  648.81  4754.4  648.34  4783.0  646.63  4889.4  643.52
  4938.8  643.04  4953.1  643.72  4959.7  642.94  4967.4  642.87  4973.9  643.00
  4981.6  644.12  4988.2  643.01  4992.1  640.60  4997.9  640.60  5002.9  639.37
  5003.5  638.87  5007.2  638.87  5007.8  639.37  5025.4  642.64  5035.4  642.89
  5045.4  643.99  5055.4  648.18  5065.4  654.41  5075.4  656.50  5095.4  656.73
#Mann=3,-1,0
  4534.4    0.05       0  5002.9   0.033       0  5007.8    0.05       0
Bank Sta=5002.9,5007.8
Exp/Cntr=0.3,0.1

Type RM Length L Ch R = 1,7039,499,499,499
BEGIN DESCRIPTION:
Unnamed Tributary of Henrietta Creek 11.0
END DESCRIPTION:
XS GIS Cut Line= 3
      2342978.97      7040810.00      2343329.00      7040860.00
      2343628.98      7040810.00
#Sta/Elev= 30
  4646.8  653.80  4656.9  652.85  4697.3  652.00  4727.6  652.63  4747.8  649.54
  4768.0  648.35  4828.7  642.07  4859.0  641.25  4889.3  642.22  4949.9  639.86
  4990.3  639.14  4997.9  638.18  5038.4  638.11  5039.0  637.61  5042.8  637.61
  5043.5  638.11  5071.4  638.41  5081.5  640.33  5101.8  640.03  5162.6  641.78
  5182.9  649.25  5193.0  650.41  5203.1  648.88  5210.7  648.70  5215.8  649.74
  5233.6  649.77  5253.8  653.83  5264.0  654.80  5271.6  657.45  5304.5  658.37
#Mann=3,-1,0
  4646.8    0.05       0  5038.4   0.033       0  5043.5    0.05       0
Bank Sta=5038.4,5043.5
Exp/Cntr=0.3,0.1

Type RM Length L Ch R = 1,6540,476,476,476
BEGIN DESCRIPTION:
Unnamed Tributary of Henrietta Creek 10.0
END DESCRIPTION:
XS GIS Cut Line= 3
      2342779.02      7041160.01      2343329.00      7041360.00
      2343428.99      7041409.99
#Sta/Elev= 30
  4418.9  654.13  4440.2  654.08  4464.8  650.79  4490.0  643.03  4495.4  642.72
  4520.6  635.75  4557.2  632.81  4661.4  632.85  4706.2  634.93  4738.1  642.36
  4748.7  642.58  4770.0  638.52  4780.0  639.04  4801.9  636.87  4850.9  636.28
  4871.8  634.48  4933.0  637.65  4988.8  637.45  4994.1  635.56  4997.0  632.81
  4999.0  632.31  5003.0  632.81  5004.1  634.75  5018.1  636.79  5040.4  637.14
  5048.8  638.90  5071.2  645.18  5085.2  647.57  5093.6  652.28  5115.9  652.26
#Mann=5,-1,0
  4418.9    0.05       0  4661.4   0.075       0  4850.9    0.05       0
  4997.0   0.033       0  5003.0    0.05       0
#XS Ineff=2,0
    0.00 4743.60  647.08               0
Permanent Ineff=
       F       F
Bank Sta=4997,5003
Exp/Cntr=0.3,0.1

Type RM Length L Ch R = 1,6064,464,464,464
BEGIN DESCRIPTION:
Unnamed Tributary of Henrietta Creek 9.0
END DESCRIPTION:
XS GIS Cut Line= 3
      2342778.99      7041209.99      2343079.00      7041560.00
      2343378.96      7041759.98
#Sta/Elev= 30
  4539.6  652.87  4553.3  650.60  4589.6  641.70  4624.7  642.25  4681.7  639.76
  4702.6  640.42  4716.9  642.31  4737.3  640.27  4745.4  643.40  4759.7  640.12
  4816.2  640.05  4844.2  636.30  4967.8  634.98  5005.5  633.97  5006.2  633.47
  5010.8  633.97  5014.1  635.27  5167.3  634.93  5245.5  636.63  5281.5  639.22
  5296.5  642.37  5302.6  640.98  5311.6  641.98  5317.6  641.32  5332.6  647.23
  5338.6  646.67  5347.6  649.50  5353.6  649.18  5358.1  652.47  5361.1  652.47
#Mann=5,-1,0
  4539.6    0.05       0  4737.3   0.075       0  4967.8    0.05       0
  5005.5   0.033       0  5010.8    0.05       0
Bank Sta=5005.5,5010.8
Exp/Cntr=0.3,0.1

Type RM Length L Ch R = 1,5600,447,447,447
BEGIN DESCRIPTION:
Unnamed Tributary of Henrietta Creek 8.0
END DESCRIPTION:
XS GIS Cut Line= 3
      2342628.98      7041860.00      2342879.00      7041860.00
      2343228.98      7041959.99
#Sta/Elev= 30
  4749.6  645.41  4809.6  645.38  4849.6  644.68  4859.6  643.13  4869.6  639.81
  4889.6  635.51  4899.6  632.67  4919.6  633.40  4949.6  633.45  4959.6  631.40
  4969.6  630.78  4977.0  629.70  4977.7  629.20  4981.5  629.20  4982.3  629.70
  5002.2  630.29  5016.5  633.13  5021.7  632.42  5030.8  632.93  5094.5  631.99
  5114.0  632.41  5155.6  631.36  5228.4  632.57  5249.2  632.59  5268.7  631.55
  5280.4  632.48  5322.0  632.76  5341.5  646.73  5346.7  646.25  5363.6  646.50
#Mann=3,-1,0
  4749.6    0.05       0  4977.0   0.033       0  4982.3    0.05       0
Bank Sta=4977,4982.3
Exp/Cntr=0.3,0.1

Type RM Length L Ch R = 1,5153,457,457,457
BEGIN DESCRIPTION:
Unnamed Tributary of Henrietta Creek 7.0
END DESCRIPTION:
XS GIS Cut Line= 3
      2342678.98      7042059.96      2342779.00      7042210.00
      2343128.99      7042360.00
#Sta/Elev= 30
  4811.6  644.99  4814.6  644.99  4819.2  643.06  4840.2  639.48  4861.2  632.95
  4870.2  632.73  4876.2  629.84  4891.3  627.08  4897.3  628.89  4912.3  629.50
  4978.4  628.79  5001.0  629.91  5006.4  629.30  5046.3  628.70  5053.6  629.16
  5100.7  628.69  5129.7  627.65  5135.2  625.72  5153.3  625.19  5158.7  626.68
  5163.3  625.18  5164.0  624.68  5168.7  625.18  5187.8  628.80  5198.6  629.45
  5211.3  631.30  5305.6  635.28  5318.3  639.46  5340.1  643.40  5372.7  644.72
#Mann=3,-1,0
  4811.6    0.05       0  5163.3   0.033       0  5168.7    0.05       0
Bank Sta=5163.3,5168.7
Exp/Cntr=0.3,0.1