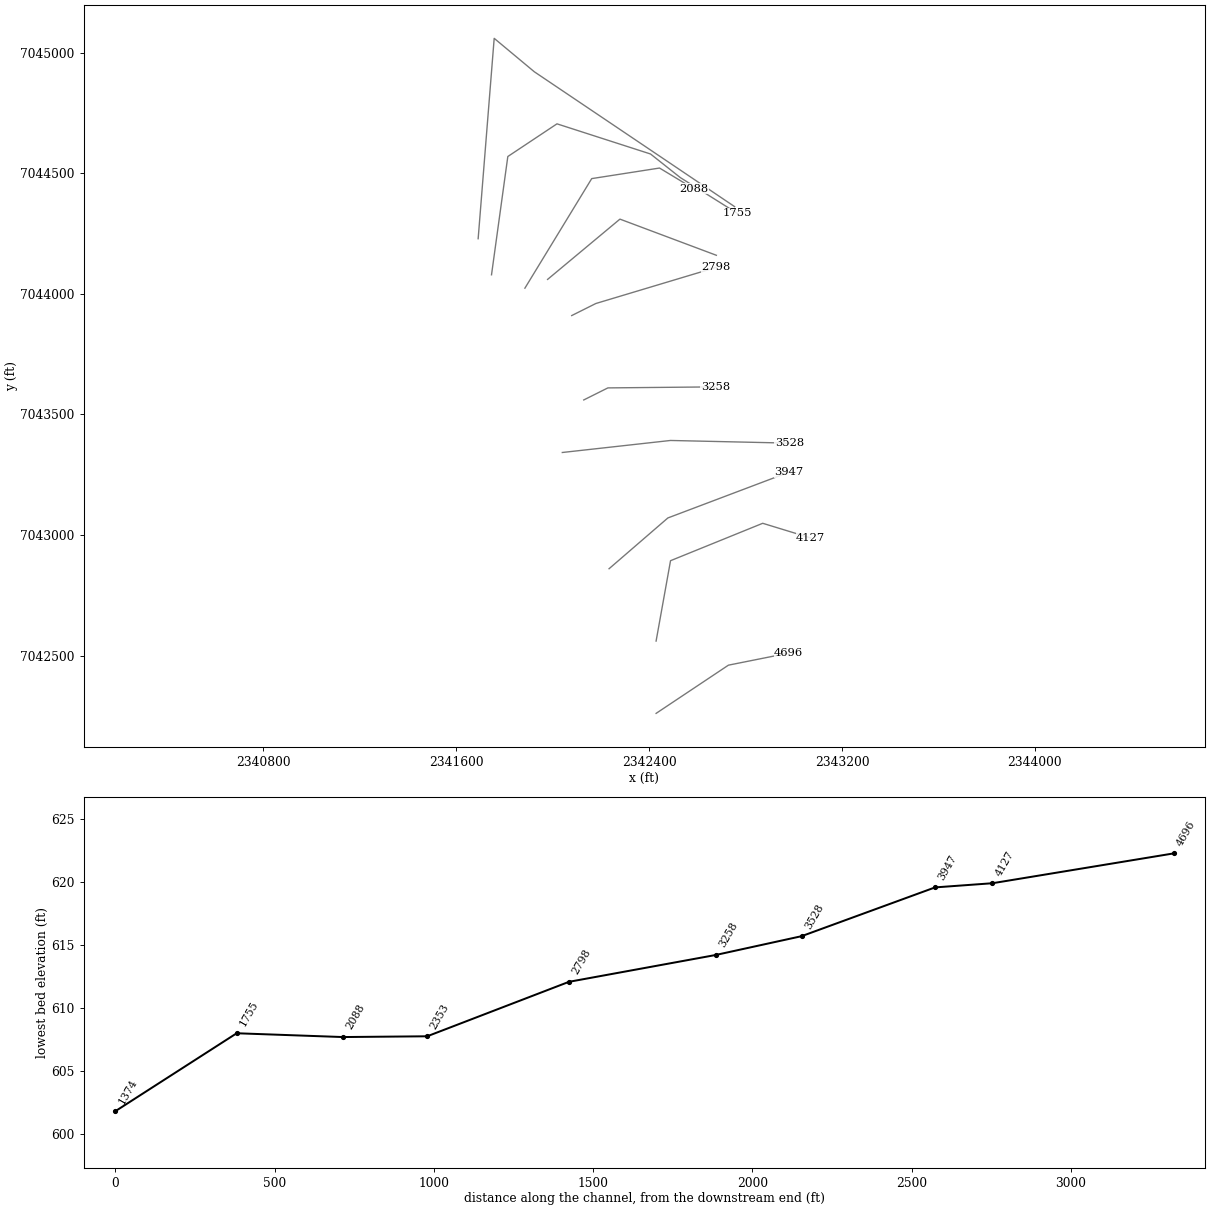
HEC-RAS study Unnamed Tr of Henrietta Cr.prj: Unnamed Tr of Henrietta Cr Base Level Engineering

--- Unnamed Tr of Henrietta Cr.g01 (geometry) --- (continued)

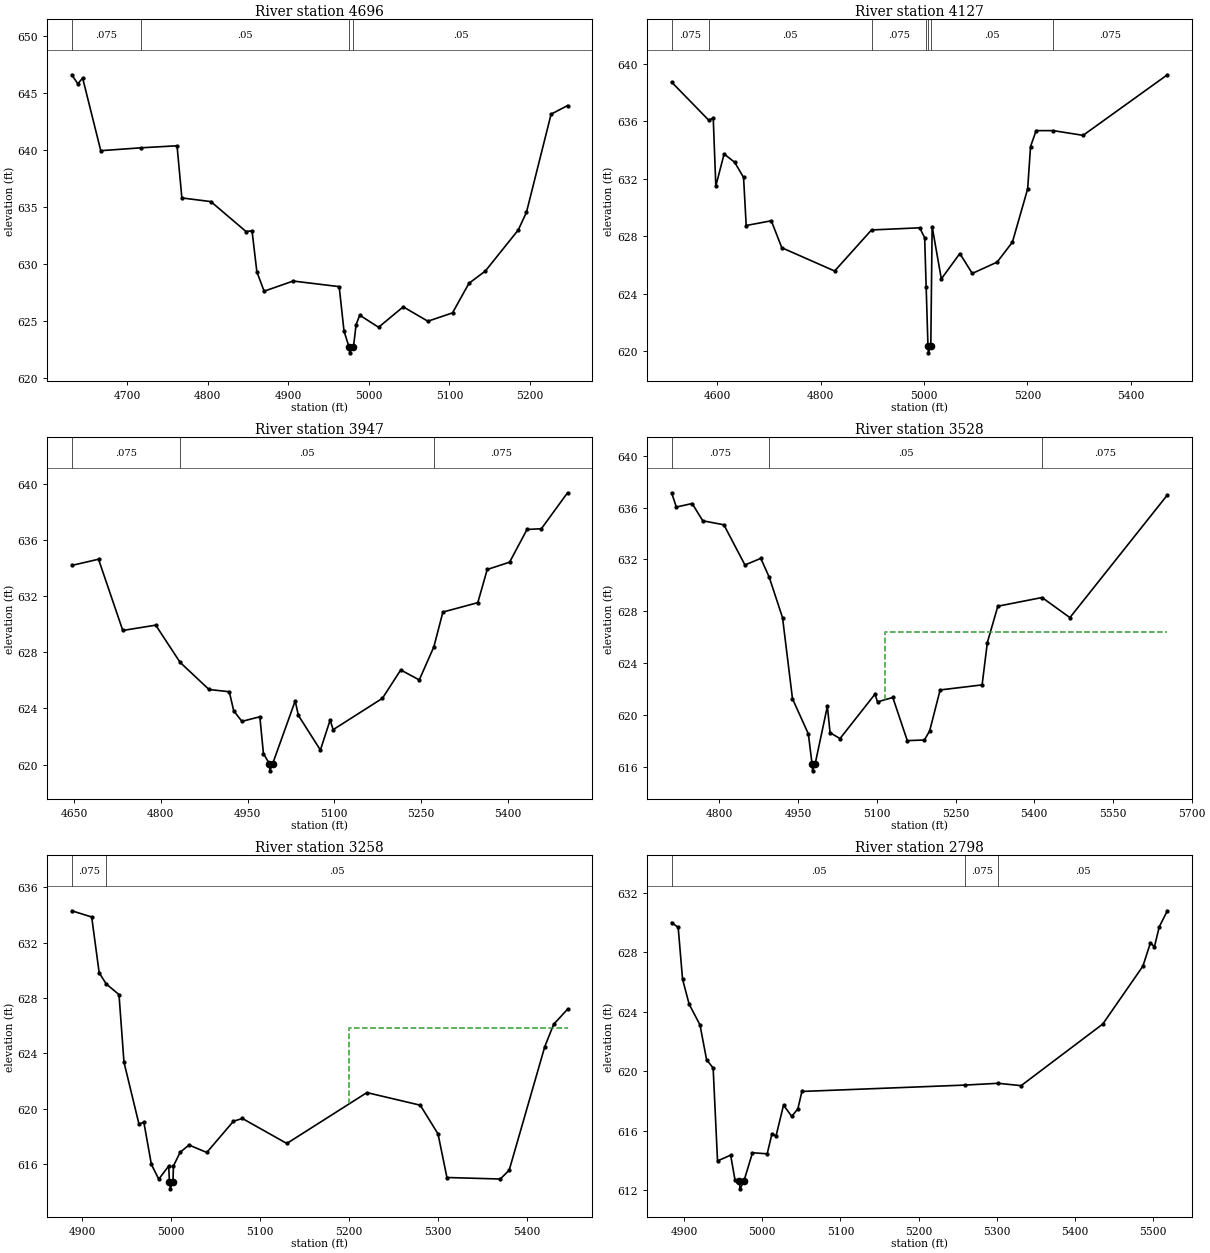
Type RM Length L Ch R = 1,4696,569,569,569
BEGIN DESCRIPTION:
Unnamed Tributary of Henrietta Creek 6.0
END DESCRIPTION:
XS GIS Cut Line= 3
      2342429.04      7042260.03      2342729.00      7042460.00
      2342979.04      7042510.01
#Sta/Elev= 30
  4631.1  646.60  4638.6  645.81  4644.6  646.31  4667.1  639.95  4716.6  640.20
  4761.8  640.38  4767.8  635.81  4803.8  635.49  4847.4  632.87  4854.9  632.93
  4860.9  629.34  4869.9  627.64  4906.0  628.53  4963.1  628.04  4969.1  624.14
  4975.4  622.74  4976.1  622.24  4980.8  622.74  4984.1  624.71  4988.6  625.54
  5012.0  624.48  5042.6  626.27  5073.2  625.01  5103.8  625.74  5124.2  628.33
  5144.6  629.41  5185.4  633.00  5195.6  634.55  5226.2  643.15  5246.6  643.90
#Mann=4,-1,0
  4631.1   0.075       0  4716.6    0.05       0  4975.4   0.033       0
  4980.8    0.05       0
Bank Sta=4975.4,4980.8
Exp/Cntr=0.3,0.1

Type RM Length L Ch R = 1,4127,180,180,180
BEGIN DESCRIPTION:
Unnamed Tributary of Henrietta Creek 5.0
END DESCRIPTION:
XS GIS Cut Line= 4
      2342428.99      7042559.97      2342488.86      7042893.26
      2342871.20      7043048.41      2343070.65      7042987.46
#Sta/Elev= 30
  4511.3  638.74  4583.1  636.09  4591.9  636.23  4596.9  631.50  4612.9  633.73
  4633.3  633.16  4650.6  632.10  4655.7  628.75  4704.3  629.08  4724.7  627.20
  4826.9  625.58  4898.3  628.44  4991.6  628.59  5001.2  627.90  5004.1  624.49
  5007.6  620.38  5008.4  619.88  5013.1  620.38  5015.7  628.67  5033.5  625.03
  5069.3  626.80  5093.4  625.41  5141.5  626.20  5171.1  627.59  5200.6  631.30
  5206.2  634.25  5217.0  635.36  5250.1  635.36  5307.9  635.03  5471.1  639.25
#Mann=7,-1,0
  4511.3   0.075       0  4583.1    0.05       0  4898.3   0.075       0
  5004.1    0.05       0  5007.6    0.07       0  5013.1    0.05       0
  5250.1   0.075       0
Bank Sta=5007.6,5013.1
Exp/Cntr=0.3,0.1

Type RM Length L Ch R = 1,3947,419,419,419
BEGIN DESCRIPTION:
Unnamed Tributary of Henrietta Creek 4.0
END DESCRIPTION:
XS GIS Cut Line= 3
      2342233.98      7042860.02      2342477.78      7043070.57
      2342979.04      7043260.01
#Sta/Elev= 30
  4645.8  634.17  4692.1  634.61  4734.1  629.54  4791.1  629.92  4833.3  627.27
  4883.3  625.34  4918.4  625.18  4926.1  623.82  4940.3  623.07  4971.3  623.40
  4977.5  620.78  4987.9  620.05  4988.7  619.55  4993.4  620.05  5032.5  624.53
  5037.9  623.50  5076.1  621.03  5092.9  623.16  5098.2  622.48  5183.4  624.71
  5215.1  626.73  5247.2  626.02  5272.4  628.37  5288.1  630.85  5348.5  631.52
  5364.8  633.88  5403.5  634.40  5433.7  636.73  5458.5  636.78  5503.8  639.34
#Mann=3,-1,0
  4645.8   0.075       0  4833.3    0.05       0  5272.4   0.075       0
Bank Sta=4987.9,4993.4
Exp/Cntr=0.3,0.1

Type RM Length L Ch R = 1,3528,270,270,270
BEGIN DESCRIPTION:
Unnamed Tributary of Henrietta Creek 3.5
END DESCRIPTION:
XS GIS Cut Line= 3
      2342040.01      7043342.09      2342488.86      7043391.96
      2342982.02      7043380.88
#Sta/Elev= 30
  4708.8  637.14  4717.8  636.04  4748.0  636.31  4768.2  634.98  4808.4  634.67
  4848.6  631.57  4878.8  632.08  4895.0  630.61  4920.2  627.51  4939.2  621.25
  4969.4  618.54  4976.6  616.19  4977.5  615.69  4982.2  616.19  5005.7  620.67
  5010.8  618.63  5029.8  618.18  5096.3  621.60  5101.3  621.01  5130.4  621.35
  5158.0  618.02  5190.6  618.07  5200.6  618.77  5220.6  621.93  5300.6  622.32
  5310.6  625.59  5330.6  628.39  5414.9  629.06  5467.9  627.51  5653.7  636.97
#Mann=3,-1,0
  4708.8   0.075       0  4895.0    0.05       0  5414.9   0.075       0
#XS Ineff=2,0
       0                 5114.70    0.00  626.42
Permanent Ineff=
       F       F
Bank Sta=4976.6,4982.2
Exp/Cntr=0.3,0.1

Type RM Length L Ch R = 1,3258,460,460,460
BEGIN DESCRIPTION:
Unnamed Tributary of Henrietta Creek 3.0
END DESCRIPTION:
XS GIS Cut Line= 3
      2342128.99      7043560.00      2342229.00      7043610.00
      2342674.57      7043614.22
#Sta/Elev= 30
  4888.2  634.31  4910.6  633.86  4919.0  629.83  4926.9  629.02  4941.3  628.25
  4946.9  623.36  4963.7  618.90  4969.3  619.00  4977.7  615.97  4986.0  614.90
  4997.2  615.85  4998.0  614.70  4999.0  614.20  5002.0  614.70  5002.5  615.85
  5010.0  616.84  5020.0  617.37  5040.0  616.83  5070.0  619.09  5080.0  619.29
  5130.0  617.48  5220.0  621.16  5280.0  620.25  5300.0  618.17  5310.0  615.02
  5370.0  614.91  5380.0  615.55  5420.0  624.48  5430.0  626.10  5445.6  627.19
#Mann=2,-1,0
  4888.2   0.075       0  4926.9    0.05       0
#XS Ineff=2,0
       0                 5200.20    0.00  625.81
Permanent Ineff=
       F       F
Bank Sta=4998,5002
Exp/Cntr=0.3,0.1

Type RM Length L Ch R = 1,2798,445,445,445
BEGIN DESCRIPTION:
Unnamed Tributary of Henrietta Creek 2.0
END DESCRIPTION:
XS GIS Cut Line= 3
      2342079.01      7043910.00      2342179.00      7043960.00
      2342678.99      7044110.00
#Sta/Elev= 30
  4884.1  630.02  4892.5  629.69  4898.1  626.20  4906.5  624.52  4920.4  623.12
  4928.8  620.78  4937.2  620.22  4942.8  613.96  4959.6  614.35  4965.1  612.69
  4970.6  612.58  4971.6  612.08  4976.4  612.58  4987.5  614.51  5006.3  614.44
  5012.4  615.79  5017.6  615.64  5027.2  617.72  5037.7  616.96  5045.5  617.47
  5050.7  618.64  5259.5  619.07  5301.6  619.19  5330.9  619.03  5435.3  623.18
  5486.6  627.08  5496.2  628.64  5501.4  628.39  5507.5  629.73  5517.9  630.81
#Mann=3,-1,0
  4884.1    0.05       0  5259.5   0.075       0  5301.6    0.05       0
Bank Sta=4970.6,4976.4
Exp/Cntr=0.3,0.1

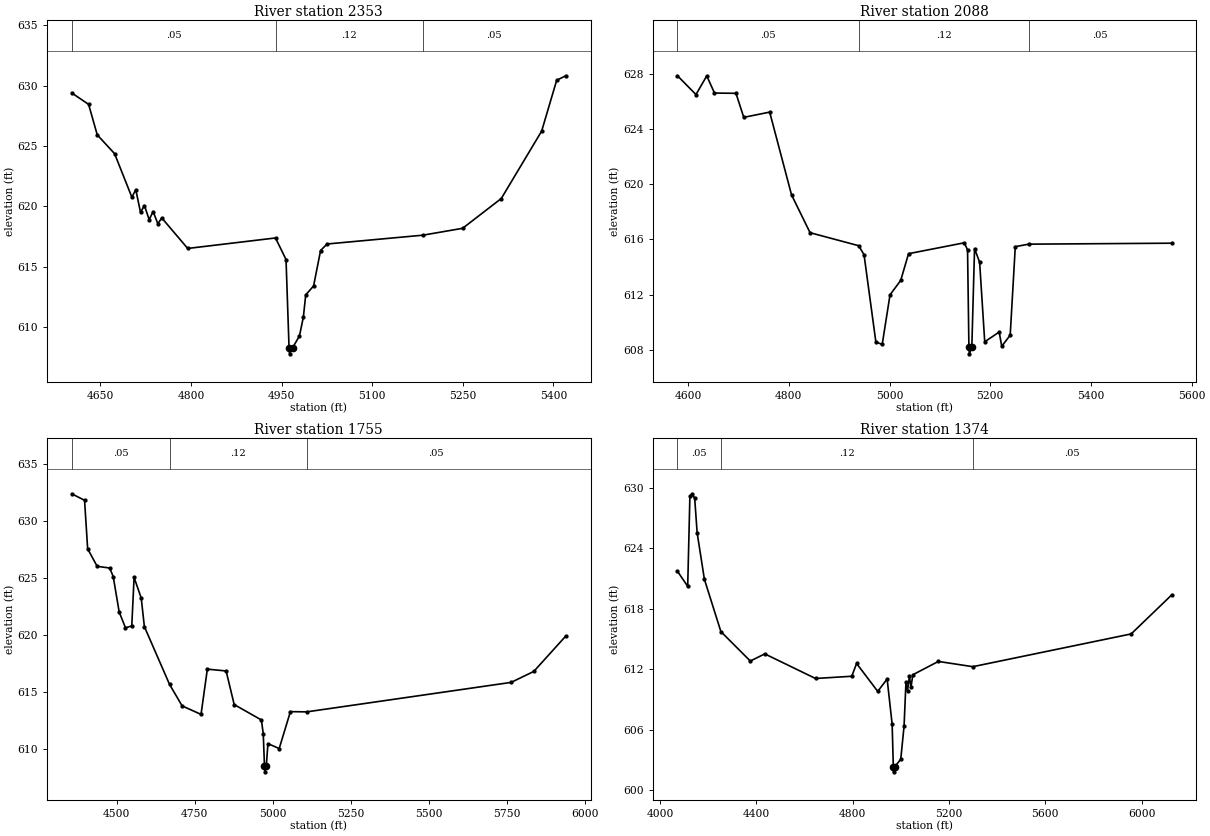
Type RM Length L Ch R = 1,2353,265,265,265
BEGIN DESCRIPTION:
Unnamed Tributary of Henrietta Creek 1.0
END DESCRIPTION:
XS GIS Cut Line= 3
      2341978.98      7044059.98      2342279.00      7044310.00
      2342678.96      7044160.02
#Sta/Elev= 30
  4602.7  629.41  4630.7  628.46  4645.0  625.93  4673.7  624.37  4702.3  620.76
  4708.8  621.38  4716.6  619.51  4723.1  620.07  4730.9  618.90  4737.5  619.57
  4745.3  618.56  4751.8  619.04  4794.7  616.51  4940.0  617.38  4957.4  615.59
  4962.4  608.27  4963.3  607.77  4968.2  608.27  4979.6  609.25  4986.1  610.82
  4990.0  612.66  5003.0  613.40  5014.6  616.34  5025.3  616.88  5183.9  617.61
  5249.6  618.18  5313.6  620.65  5380.4  626.24  5405.3  630.46  5420.4  630.83
#Mann=3,-1,0
  4602.7    0.05       0  4940.0    0.12       0  5183.9    0.05       0
Bank Sta=4962.4,4968.2
Exp/Cntr=0.3,0.1

Type RM Length L Ch R = 1,2088,333,333,333
BEGIN DESCRIPTION:
Unnamed Tributary of Henrietta Creek 0.4
END DESCRIPTION:
XS GIS Cut Line= 4
      2341884.87      7044023.64      2342161.93      7044478.02
      2342443.18      7044521.88      2342584.08      7044436.87
#Sta/Elev= 30
  4578.8  627.84  4615.5  626.48  4636.9  627.83  4652.3  626.59  4695.0  626.57
  4710.4  624.83  4761.9  625.21  4805.3  619.22  4842.1  616.48  4938.5  615.54
  4949.3  614.89  4972.8  608.57  4985.4  608.39  5000.9  611.98  5022.2  613.03
  5037.7  614.96  5148.5  615.75  5154.9  615.23  5157.6  608.21  5158.6  607.71
  5163.4  608.21  5168.8  615.33  5178.9  614.34  5189.0  608.58  5217.7  609.29
  5222.8  608.26  5239.6  609.06  5249.7  615.47  5276.5  615.65  5560.2  615.72
#Mann=3,-1,0
  4578.8    0.05       0  4938.5    0.12       0  5276.5    0.05       0
Bank Sta=5157.6,5163.4
Exp/Cntr=0.3,0.1

Type RM Length L Ch R = 1,1755,381,381,381
BEGIN DESCRIPTION:
Unnamed Tributary of Henrietta Creek 0.3
END DESCRIPTION:
XS GIS Cut Line= 6
      2341746.35      7044079.09      2341813.99      7044569.65
      2342017.86      7044705.21      2342405.89      7044580.14
      2342529.40      7044482.27      2342765.94      7044333.94
#Sta/Elev= 30
  4355.5  632.35  4396.8  631.78  4406.7  627.53  4437.2  626.00  4477.5  625.85
  4488.7  625.10  4507.8  622.00  4528.0  620.62  4548.2  620.78  4555.6  625.03
  4578.5  623.22  4588.6  620.72  4669.2  615.67  4709.7  613.78  4770.3  613.04
  4790.5  617.00  4850.7  616.84  4876.6  613.90  4963.8  612.55  4969.8  611.35
  4973.7  608.51  4974.7  608.01  4979.5  608.51  4984.8  610.48  5020.9  610.05
  5056.9  613.28  5109.2  613.26  5764.6  615.84  5837.4  616.80  5940.0  619.90
#Mann=3,-1,0
  4355.5    0.05       0  4669.2    0.12       0  5109.2    0.05       0
Bank Sta=4973.7,4979.5
Exp/Cntr=0.3,0.1

Type RM Length L Ch R = 1,1374,0,0,0
BEGIN DESCRIPTION:
Unnamed Tributary of Henrietta Creek 0.2
END DESCRIPTION:
XS GIS Cut Line= 4
      2341690.94      7044228.70      2341757.43      7045059.84
      2341923.67      7044921.31      2342754.41      7044361.94
#Sta/Elev= 30
  4072.6  621.73  4115.0  620.24  4124.1  629.17  4134.1  629.42  4144.1  628.96
  4154.2  625.55  4184.3  620.94  4252.8  615.75  4374.9  612.83  4435.0  613.54
  4645.7  611.10  4796.2  611.32  4816.3  612.59  4904.0  609.82  4943.1  611.05
  4963.9  606.56  4968.8  602.34  4969.8  601.84  4974.6  602.34  4999.6  603.09
  5013.4  606.38  5021.2  610.73  5027.7  609.86  5035.5  611.34  5042.0  610.22
  5049.8  611.47  5155.7  612.79  5299.0  612.27  5956.4  615.52  6124.3  619.38
#Mann=3,-1,0
  4072.6    0.05       0  4252.8    0.12       0  5299.0    0.05       0
Bank Sta=4968.8,4974.6
Exp/Cntr=0.3,0.1

Chan Stop Cuts=-1