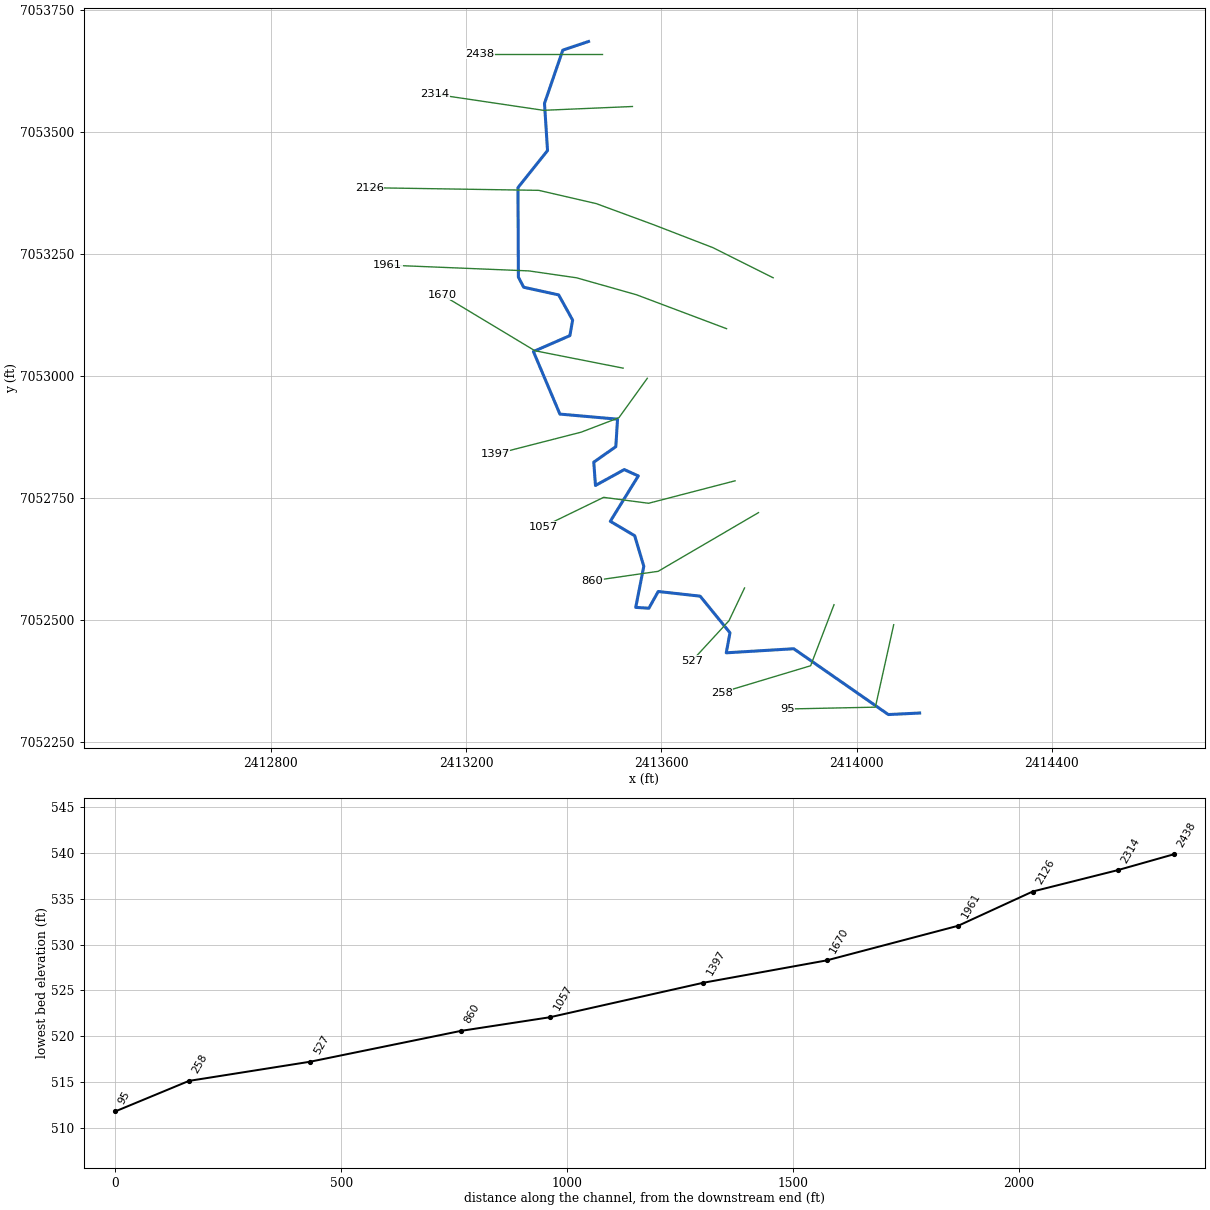
--- Unnamed Tr to Bakers Br.prj (project) ---

Proj Title=Unnamed Tr to Bakers Br Base Level Engineering
Current Plan=p01
Default Exp/Contr=0.3,0.1
English Units
Geom File=g01
Flow File=f01
Plan File=p01
Y Axis Title=Elevation
X Axis Title(PF)=Main Channel Distance
X Axis Title(XS)=Station
BEGIN DESCRIPTION:
Unnamed Tr to Bakers Br
END DESCRIPTION:
DSS Export Rating Curves= 0
DSS Export Rating Curve Sorted= 0
DSS Export Volume Flow Curves= 0
DXF OffsetX= 0
DXF OffsetY= 0
DXF ScaleX= 1
DXF ScaleY= 10

--- Unnamed Tr to Bakers Br.p01 (plan) ---

Plan Title=Multiple Run
Short Identifier=Multiple
Geom File=g01
Flow File=f01
Subcritical Flow
K Sum by GR= 0
Std Step Tol= 0.01
Critical Tol= 0.01
Num of Std Step Trials= 20
Max Error Tol= 0.3
Flow Tol Ratio= 0.001
Split Flow NTrial= 30
Split Flow Tol= 0.02
Split Flow Ratio= 0.02
Log Output Level= 0
Friction Slope Method= 1
Unsteady Friction Slope Method= 2
Unsteady Bridges Friction Slope Method= 1
Parabolic Critical Depth
Global Vel Dist=  1 , 1 , 1
Global Log Level= 0
CheckData=True
Encroach Param= -1, 0, 0, 0
BEGIN DESCRIPTION:
Multiple Run
END DESCRIPTION:

--- Unnamed Tr to Bakers Br.f01 (steady flow) ---

Flow Title=Multiple
Program Version=4.10
Number of Profiles= 7
Profile Names=10-year,25-year,50-year,1pct_min,100-year,1pct_plu,500-year
River Rch & RM=Unnamed Tr to Ba,Reach-1         ,2438
     221     286     336     198     394     787     541
River Rch & RM=Unnamed Tr to Ba,Reach-1         ,95
     750    1043    1288     790    1577    3146    2367
Boundary for River Rch & Prof#=Unnamed Tr to Ba,Reach-1         , 1
Up Type= 0
Dn Type= 3
Dn Slope=0.012
Boundary for River Rch & Prof#=Unnamed Tr to Ba,Reach-1         , 2
Up Type= 0
Dn Type= 3
Dn Slope=0.012
Boundary for River Rch & Prof#=Unnamed Tr to Ba,Reach-1         , 3
Up Type= 0
Dn Type= 3
Dn Slope=0.012
Boundary for River Rch & Prof#=Unnamed Tr to Ba,Reach-1         , 4
Up Type= 0
Dn Type= 3
Dn Slope=0.012
Boundary for River Rch & Prof#=Unnamed Tr to Ba,Reach-1         , 5
Up Type= 0
Dn Type= 3
Dn Slope=0.012
Boundary for River Rch & Prof#=Unnamed Tr to Ba,Reach-1         , 6
Up Type= 0
Dn Type= 3
Dn Slope=0.012
Boundary for River Rch & Prof#=Unnamed Tr to Ba,Reach-1         , 7
Up Type= 0
Dn Type= 3
Dn Slope=0.012
DSS Import GetInterval= 0
DSS Import GetPeak= 0
DSS Import FillOption= 0

--- Unnamed Tr to Bakers Br.g01 (geometry) ---

Geom Title=Existing Conditions
Program Version=4.10

River Reach=Unnamed Tr to Ba,Reach-1
Reach XY= 30
      2413451.04      7053684.72      2413398.26      7053667.01
      2413360.76      7053557.99      2413367.01      7053461.46
      2413306.43      7053385.57       2413307.3      7053202.41
      2413318.15      7053181.58      2413389.77      7053165.95
      2413418.41       7053114.3      2413412.72      7053082.54
      2413338.06      7053049.99      2413392.32      7052921.95
      2413510.37      7052911.54      2413506.83      7052855.25
      2413461.69      7052823.57      2413465.16      7052775.82
      2413524.19      7052808.37      2413552.84      7052795.35
      2413495.54      7052702.47      2413545.46      7052672.96
      2413564.12      7052610.46      2413547.63      7052526.26
      2413574.54      7052524.52      2413593.63      7052558.81
      2413679.51      7052549.24      2413740.62      7052474.24
      2413732.99      7052433.27      2413871.18       7052441.6
      2414064.93      7052306.88        2414129.        7052310.

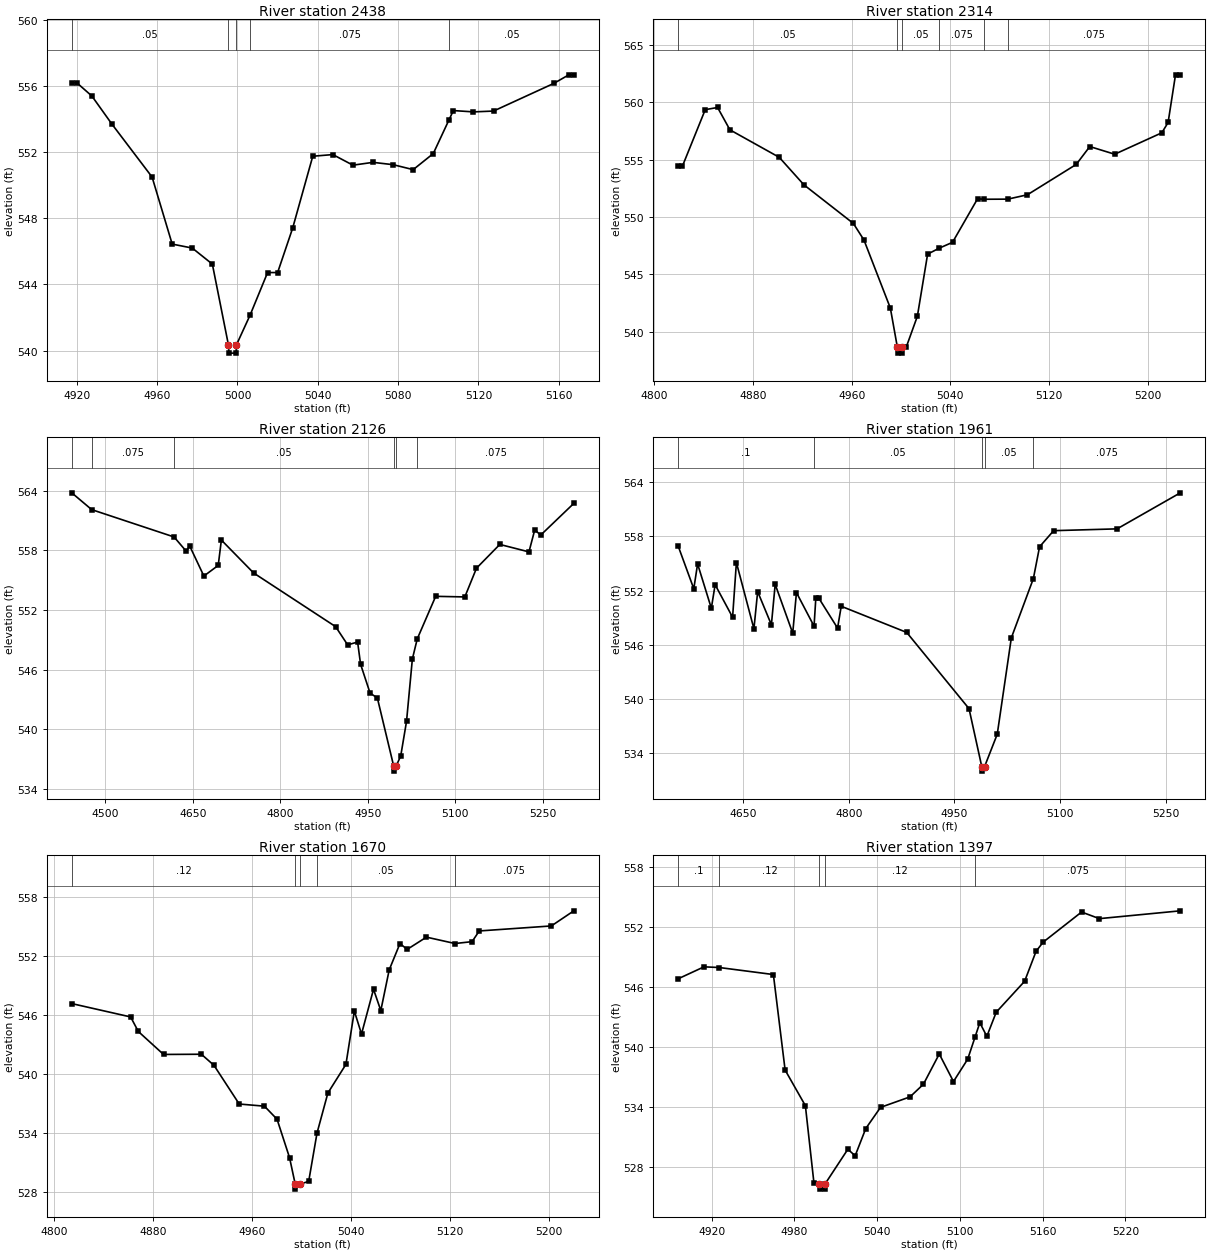
Type RM Length L Ch R = 1 ,2438    ,124,124,124
BEGIN DESCRIPTION:
Unnamed Tr to Bakers Br 7.0
END DESCRIPTION:
XS GIS Cut Line= 3
      2413479.02        7053660.        2413379.        7053660.
      2413229.02        7053660.
#Sta/Elev= 30
  4917.5  556.19    4920  556.19  4927.5  555.39  4937.5  553.69  4957.5  550.49
  4967.5  546.44  4977.5   546.2  4987.5  545.23  4995.5  540.35  4995.8  539.85
  4999.3  539.85  4999.5  540.35  5006.3  542.15    5015  544.72    5020  544.72
  5027.5  547.41  5037.5  551.75  5047.5  551.85  5057.5  551.21  5067.5  551.38
  5077.5  551.24  5087.5  550.94  5097.5  551.91  5105.3  553.94  5107.5  554.51
  5117.5  554.43  5127.5  554.48  5157.5  556.15    5165  556.67  5167.5  556.67
#Mann= 5 ,-1 , 0
  4917.5     .05       0  4995.5     .05       0  4999.5     .05       0
  5006.3    .075       0  5105.3     .05       0
Bank Sta=4995.5,4999.5
XS Rating Curve= 0 ,0
Exp/Cntr=0.3,0.1

Type RM Length L Ch R = 1 ,2314    ,188,188,188
BEGIN DESCRIPTION:
Mapping XS a9b28514
END DESCRIPTION:
XS GIS Cut Line= 3
      2413540.85       7053551.6      2413358.58      7053543.79
      2413136.35      7053576.78
#Sta/Elev= 30
  4819.4  554.44  4822.8  554.44  4841.3  559.37  4851.3  559.56  4861.3  557.61
  4901.3  555.21  4921.3  552.81  4961.4  549.44    4970  547.99  4991.4  542.05
  4997.1  538.62  4997.4  538.12  5000.9  538.12  5001.1  538.62  5004.2  538.62
  5013.3  541.34  5021.6  546.76    5031  547.28  5041.8  547.79  5062.1  551.59
  5067.3  551.55  5086.6  551.56  5102.5  551.94  5142.1  554.59  5153.1  556.15
  5173.3  555.48  5211.5  557.35  5216.6  558.25  5222.6  562.41  5226.5  562.41
#Mann= 6 ,-1 , 0
  4819.4     .05       0  4997.1     .05       0  5001.1     .05       0
    5031    .075       0  5067.3     .05       0  5086.6    .075       0
Bank Sta=4997.1,5001.1
XS Rating Curve= 0 ,0
Exp/Cntr=0.3,0.1

Type RM Length L Ch R = 1 ,2126    ,165,165,165
BEGIN DESCRIPTION:
Unnamed Tr to Bakers Br 6.0
END DESCRIPTION:
XS GIS Cut Line= 6
      2413829.09      7053200.95      2413705.42      7053262.78
      2413581.72      7053310.53       2413466.7      7053352.84
       2413349.1      7053379.96      2413002.05      7053385.37
#Sta/Elev= 30
  4442.4  563.78  4476.6  562.09  4617.9  559.34  4639.1  557.88  4644.4  558.47
    4669  555.41  4693.6  556.48    4699  559.03  4754.3  555.72    4895  550.32
  4915.6  548.49  4932.7  548.77  4937.8  546.54    4954  543.65  4966.6  543.14
  4994.6  536.29  4994.9  535.79  4998.6  536.29  5006.6   537.3  5016.6  540.79
  5026.6  547.06    5035  549.09  5066.6  553.37  5116.6  553.31  5136.6   556.2
  5176.6  558.59  5226.6  557.84  5236.6  560.07  5246.6  559.52  5303.6  562.72
#Mann= 6 ,-1 , 0
  4442.4     .05       0  4476.6    .075       0  4617.9     .05       0
  4994.6     .05       0  4998.6     .05       0    5035    .075       0
Bank Sta=4994.6,4998.6
XS Rating Curve= 0 ,0
Exp/Cntr=0.3,0.1

Type RM Length L Ch R = 1 ,1961    ,291,291,291
BEGIN DESCRIPTION:
Unnamed Tr to Bakers Br 5.0
END DESCRIPTION:
XS GIS Cut Line= 5
      2413733.61      7053096.78      2413549.17      7053166.21
      2413426.56      7053200.93      2413328.96      7053215.04
      2413039.23      7053226.97
#Sta/Elev= 30
  4557.8  556.89  4579.9  552.19  4585.3  554.94  4604.8  550.04  4610.2  552.64
    4635  549.05  4640.4  555.09  4665.3  547.77  4670.6  551.88  4690.1  548.22
  4695.5  552.68  4720.4  547.29  4725.7  551.77  4750.7  548.06  4753.2  551.14
  4757.6  551.14  4784.1  547.85  4789.3  550.26  4882.3  547.37  4970.8  538.95
  4988.9  532.55  4989.1  532.05  4992.9  532.55  5010.9  536.13  5030.9  546.77
  5062.2  553.32    5071  556.83    5091  558.61  5181.1  558.81  5270.9  562.79
#Mann= 5 ,-1 , 0
  4557.8      .1       0  4750.7     .05       0  4988.9     .05       0
  4992.9     .05       0  5062.2    .075       0
Bank Sta=4988.9,4992.9
XS Rating Curve= 0 ,0
Exp/Cntr=0.3,0.1

Type RM Length L Ch R = 1 ,1670    ,273,273,273
BEGIN DESCRIPTION:
Mapping XS d6dd4f24
END DESCRIPTION:
XS GIS Cut Line= 3
      2413521.82        7053016.      2413341.22       7053051.6
      2413151.07      7053166.03
#Sta/Elev= 30
    4814  547.17  4861.6  545.81  4867.8  544.33  4888.2  541.99  4918.8  542.01
    4929  540.88  4949.4  536.94  4969.8  536.72    4980  535.39  4990.1  531.48
  4994.7  528.77  4994.9  528.27  4998.7  528.77  5005.6  529.07  5012.3  533.97
  5021.1  538.06  5035.7  540.98  5042.5  546.41  5048.3  544.07    5058  548.63
  5063.9  546.46  5070.7  550.61  5079.4  553.29  5085.2  552.69  5100.8  553.94
  5123.9  553.29  5137.7  553.48  5143.5  554.57  5201.8  555.08    5220  556.62
#Mann= 5 ,-1 , 0
    4814     .12       0  4994.7     .07       0  4998.7     .12       0
  5012.3     .05       0  5123.9    .075       0
Bank Sta=4994.7,4998.7
XS Rating Curve= 0 ,0
Exp/Cntr=0.3,0.1

Type RM Length L Ch R = 1 ,1397    ,340,340,340
BEGIN DESCRIPTION:
Mapping XS 53f71106
END DESCRIPTION:
XS GIS Cut Line= 4
      2413571.27       7052995.2      2413513.09      7052914.45
      2413435.84      7052884.94      2413259.65       7052839.8
#Sta/Elev= 30
  4895.7  546.83  4914.4  548.02  4925.5  547.95  4964.7  547.25  4973.2  537.72
  4987.9  534.16  4994.1  526.46  4998.1  526.33  4998.3  525.83  5001.8  525.83
  5002.1  526.33  5018.7  529.81    5024  529.16  5031.7  531.88  5042.4  533.99
  5063.8  535.04  5073.5   536.3    5085  539.32  5095.3  536.57  5105.6   538.8
    5111  541.03  5114.4  542.44  5119.5  541.08  5126.3  543.49  5146.9  546.58
  5155.2  549.57  5160.3  550.48  5188.2  553.49  5201.1  552.83  5259.8  553.61
#Mann= 5 ,-1 , 0
  4895.7      .1       0  4925.5     .12       0  4998.1     .07       0
  5002.1     .12       0    5111    .075       0
Bank Sta=4998.1,5002.1
XS Rating Curve= 0 ,0
Exp/Cntr=0.3,0.1

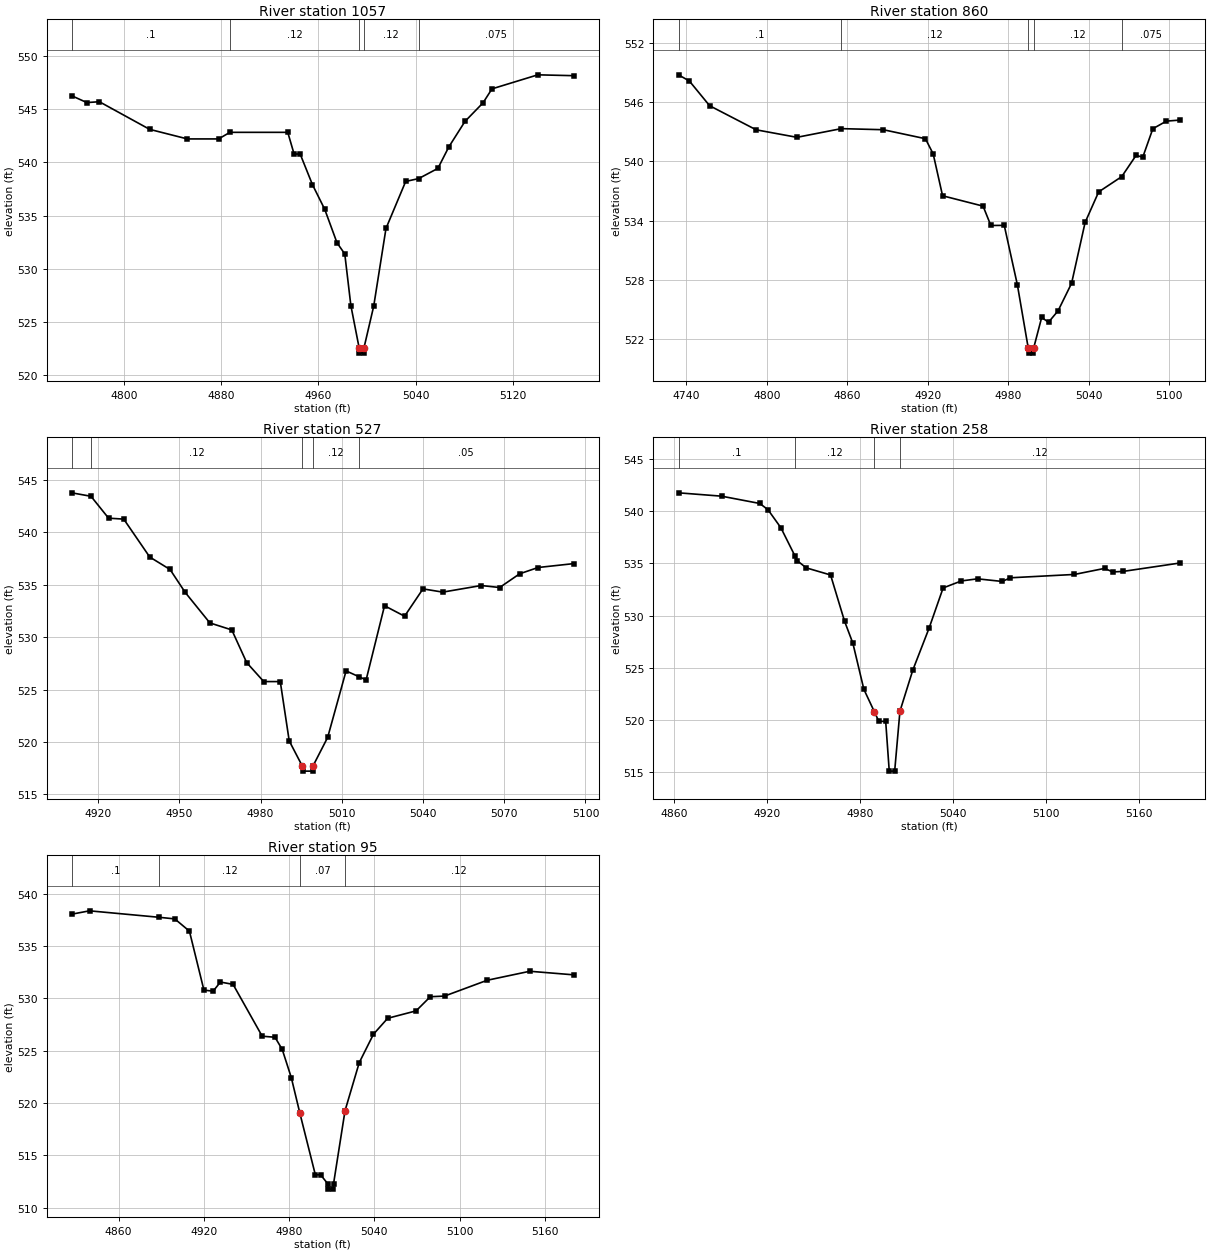
Type RM Length L Ch R = 1 ,1057    ,197,197,197
BEGIN DESCRIPTION:
Mapping XS 8375de09
END DESCRIPTION:
XS GIS Cut Line= 4
        2413751.      7052785.36      2413573.94      7052739.36
      2413481.93      7052751.52      2413358.66      7052691.62
#Sta/Elev= 30
  4757.2  546.27  4769.6  545.63  4779.9  545.71  4821.3  543.11  4852.3  542.21
    4878  542.21  4887.3  542.83  4934.9  542.83  4940.1  540.79  4945.1  540.79
  4955.2  537.91  4965.3  535.59  4975.4  532.44  4981.8  531.39  4986.8  526.54
  4993.6  522.56  4993.8  522.06  4997.3  522.06  4997.6  522.56  5005.6  526.48
  5015.7  533.79  5031.9  538.21  5042.6  538.48  5058.4  539.44  5067.4  541.46
  5080.7  543.86  5095.5   545.6  5102.9  546.92  5140.6  548.24    5170  548.16
#Mann= 5 ,-1 , 0
  4757.2      .1       0  4887.3     .12       0  4993.6     .07       0
  4997.6     .12       0  5042.6    .075       0
Bank Sta=4993.6,4997.6
XS Rating Curve= 0 ,0
Exp/Cntr=0.3,0.1

Type RM Length L Ch R = 1 ,860     ,333,333,333
BEGIN DESCRIPTION:
Mapping XS 00e32371
END DESCRIPTION:
XS GIS Cut Line= 3
      2413799.03      7052720.23      2413593.47      7052600.09
      2413458.75      7052580.65
#Sta/Elev= 30
  4734.2  548.76  4742.3  548.13  4757.4  545.63  4792.1  543.19  4822.5  542.43
  4855.6  543.31  4886.9   543.2  4918.3  542.29  4924.1  540.75  4931.1  536.51
  4961.3  535.46  4967.1   533.5  4977.1  533.51  4986.9  527.48    4995  521.07
  4995.3  520.57  4998.8  520.57    4999  521.07    5005  524.18  5010.1   523.7
  5017.2  524.85  5027.3  527.64  5037.4  533.81  5047.5   536.9  5064.7  538.45
  5075.4   540.6  5080.4  540.42  5087.9   543.3    5098  544.07  5108.4  544.18
#Mann= 5 ,-1 , 0
  4734.2      .1       0  4855.6     .12       0    4995     .07       0
    4999     .12       0  5064.7    .075       0
Bank Sta=4995,4999
XS Rating Curve= 0 ,0
Exp/Cntr=0.3,0.1

Type RM Length L Ch R = 1 ,527     ,269,269,269
BEGIN DESCRIPTION:
Unnamed Tr to Bakers Br 2.0
END DESCRIPTION:
XS GIS Cut Line= 3
      2413770.47      7052566.01      2413738.55      7052498.92
      2413663.35      7052417.28
#Sta/Elev= 30
  4910.3  543.78  4917.4  543.45  4923.9  541.36  4929.5  541.27  4939.1  537.65
  4946.6  536.46  4952.2  534.27  4961.3  531.36  4969.4  530.69  4974.9  527.57
  4981.2  525.76  4987.3  525.76  4990.6   520.1  4995.4  517.71  4995.7  517.21
  4999.2  517.21  4999.4  517.71  5004.8  520.43  5011.6  526.78  5016.3  526.23
    5019  525.92  5025.8     533  5033.2     532    5040  534.61  5047.3   534.3
  5061.5  534.93  5068.3  534.74  5075.7  536.05  5082.5  536.65  5095.6  537.02
#Mann= 5 ,-1 , 0
  4910.3      .1       0  4917.4     .12       0  4995.4     .07       0
  4999.4     .12       0  5016.3     .05       0
Bank Sta=4995.4,4999.4
XS Rating Curve= 0 ,0
Exp/Cntr=0.3,0.1

Type RM Length L Ch R = 1 ,258     ,163,163,163
BEGIN DESCRIPTION:
Mapping XS 74b9de40
END DESCRIPTION:
XS GIS Cut Line= 3
      2413953.66      7052531.73      2413905.76      7052406.76
      2413723.54      7052352.02
#Sta/Elev= 30
  4862.7  541.74  4890.5  541.42  4915.2  540.72  4920.5  540.12  4928.8   538.4
    4938  535.67  4939.5  535.23  4945.2  534.56  4960.9  533.88  4969.9  529.47
  4975.3  527.35  4982.4  522.94 4989.19 520.791  4992.1  519.87  4996.5  519.87
  4998.8  515.11  5002.3  515.11  5005.7  520.84    5014  524.77  5024.5  528.78
  5033.6  532.64  5045.4  533.31  5055.8  533.51  5071.8  533.26    5077  533.61
  5118.4  533.93  5137.9  534.51  5143.1  534.17  5149.8  534.22  5186.8  535.03
#Mann= 4 ,-1 , 0
  4862.7      .1       0    4938     .12       0 4989.19     .07       0
  5005.7     .12       0
Bank Sta=4989.19,5005.7
XS Rating Curve= 0 ,0
Exp/Cntr=0.3,0.1

Type RM Length L Ch R = 1 ,95      ,0,0,0
BEGIN DESCRIPTION:
Unnamed Tr to Bakers Br 1.0
END DESCRIPTION:
XS GIS Cut Line= 3
       2414075.9      7052490.79      2414038.35      7052322.02
      2413858.19      7052318.26
#Sta/Elev= 30
  4827.1  538.03  4839.6  538.35  4888.8  537.73  4899.6  537.58  4909.9  536.41
  4920.1  530.78  4926.6  530.68  4931.7  531.55  4940.6  531.33  4961.1  526.38
  4970.1  526.28  4975.2  525.12  4981.6  522.42 4987.65  519.01  4998.5  513.15
  5002.2  513.15  5007.3  512.28  5007.6  511.78  5011.1  511.78  5011.3  512.28
  5019.4  519.27  5029.4  523.86  5039.4  526.57  5049.4  528.09  5069.4   528.8
  5079.4  530.15  5089.4  530.21  5119.4  531.72  5149.4  532.58  5180.2  532.24
#Mann= 4 ,-1 , 0
  4827.1      .1       0  4888.8     .12       0 4987.65     .07       0
  5019.4     .12       0
Bank Sta=4987.65,5019.4
XS Rating Curve= 0 ,0
Exp/Cntr=0.3,0.1

Chan Stop Cuts=-1
Use User Specified Reach Order=0
Composite Channel Slope=5