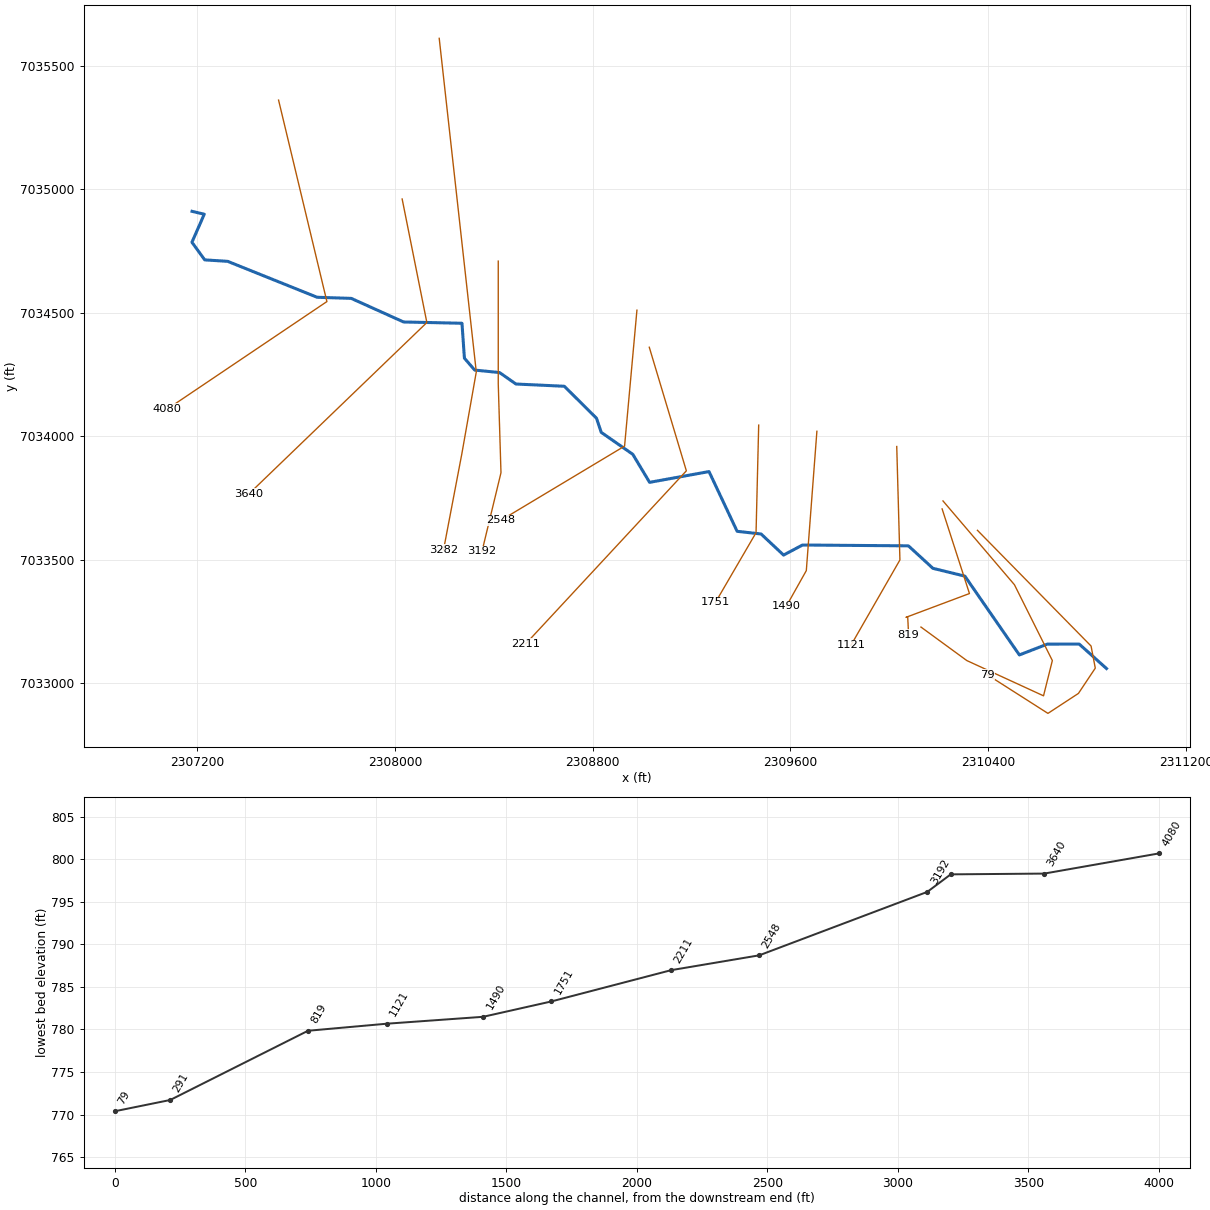
--- Unnamed Tr to Stream HEN-2.prj (project) ---

Proj Title=Unnamed Tr to Stream HEN-2 Base Level Engineering
Current Plan=p01
Default Exp/Contr=0.3,0.1
English Units
Geom File=g01
Flow File=f01
Plan File=p01
BEGIN DESCRIPTION:
Unnamed Tr to Stream HEN-2
END DESCRIPTION:

--- Unnamed Tr to Stream HEN-2.p01 (plan) ---

Plan Title=Multiple Run
Short Identifier=Multiple
Geom File=g01
Flow File=f01
Subcritical Flow
K Sum by GR= 0
Std Step Tol= 0.01
Critical Tol= 0.01
Num of Std Step Trials= 20
Max Error Tol= 0.3
Flow Tol Ratio= 0.001
Split Flow NTrial= 30
Split Flow Tol= 0.02
Split Flow Ratio= 0.02
Log Output Level= 0
Friction Slope Method= 1
Unsteady Friction Slope Method= 2
Unsteady Bridges Friction Slope Method= 1
Parabolic Critical Depth
Global Vel Dist=  1 , 1 , 1
Global Log Level= 0
CheckData=True
Encroach Param= -1, 0, 0, 0
BEGIN DESCRIPTION:
Multiple Run
END DESCRIPTION:

--- Unnamed Tr to Stream HEN-2.f01 (steady flow) ---

Flow Title=Multiple
Number of Profiles=7
Profile Names=10-year,25-year,50-year,1pct_min,100-year,1pct_plu,500-year
River Rch & RM= Unnamed Tr to St,Reach-1,4080
     375     494     587     346     691    1380     957
River Rch & RM= Unnamed Tr to St,Reach-1,3640
     486     652     784     468     933    1860    1320
Boundary for River Rch & Prof#=Unnamed Tr to St,Reach-1,1
Up Type=0
Dn Type=3
Dn Slope=0.005
Boundary for River Rch & Prof#=Unnamed Tr to St,Reach-1,2
Up Type=0
Dn Type=3
Dn Slope=0.005
Boundary for River Rch & Prof#=Unnamed Tr to St,Reach-1,3
Up Type=0
Dn Type=3
Dn Slope=0.005
Boundary for River Rch & Prof#=Unnamed Tr to St,Reach-1,4
Up Type=0
Dn Type=3
Dn Slope=0.005
Boundary for River Rch & Prof#=Unnamed Tr to St,Reach-1,5
Up Type=0
Dn Type=3
Dn Slope=0.005
Boundary for River Rch & Prof#=Unnamed Tr to St,Reach-1,6
Up Type=0
Dn Type=3
Dn Slope=0.005
Boundary for River Rch & Prof#=Unnamed Tr to St,Reach-1,7
Up Type=0
Dn Type=3
Dn Slope=0.005

--- Unnamed Tr to Stream HEN-2.g01 (geometry) ---

Geom Title=Existing Conditions

River Reach=Unnamed Tr to St,Reach-1
Reach XY= 30
      2307179.00      7034910.00      2307228.29      7034898.27
      2307178.46      7034784.88      2307230.22      7034713.52
      2307323.02      7034707.64      2307684.94      7034562.27
      2307823.06      7034557.73      2308034.94      7034462.26
      2308271.09      7034457.09      2308280.99      7034315.66
      2308322.50      7034267.72      2308423.02      7034257.64
      2308489.50      7034211.22      2308685.19      7034202.19
      2308815.28      7034072.98      2308834.62      7034015.62
      2308962.35      7033926.69      2309030.28      7033813.37
      2309270.68      7033857.03      2309384.44      7033615.25
      2309481.37      7033604.42      2309572.27      7033519.15
      2309648.98      7033559.81      2310077.53      7033556.45
      2310176.58      7033465.54      2310305.93      7033433.85
      2310526.45      7033114.99      2310639.50      7033158.77
      2310768.57      7033158.99      2310879.00      7033060.00

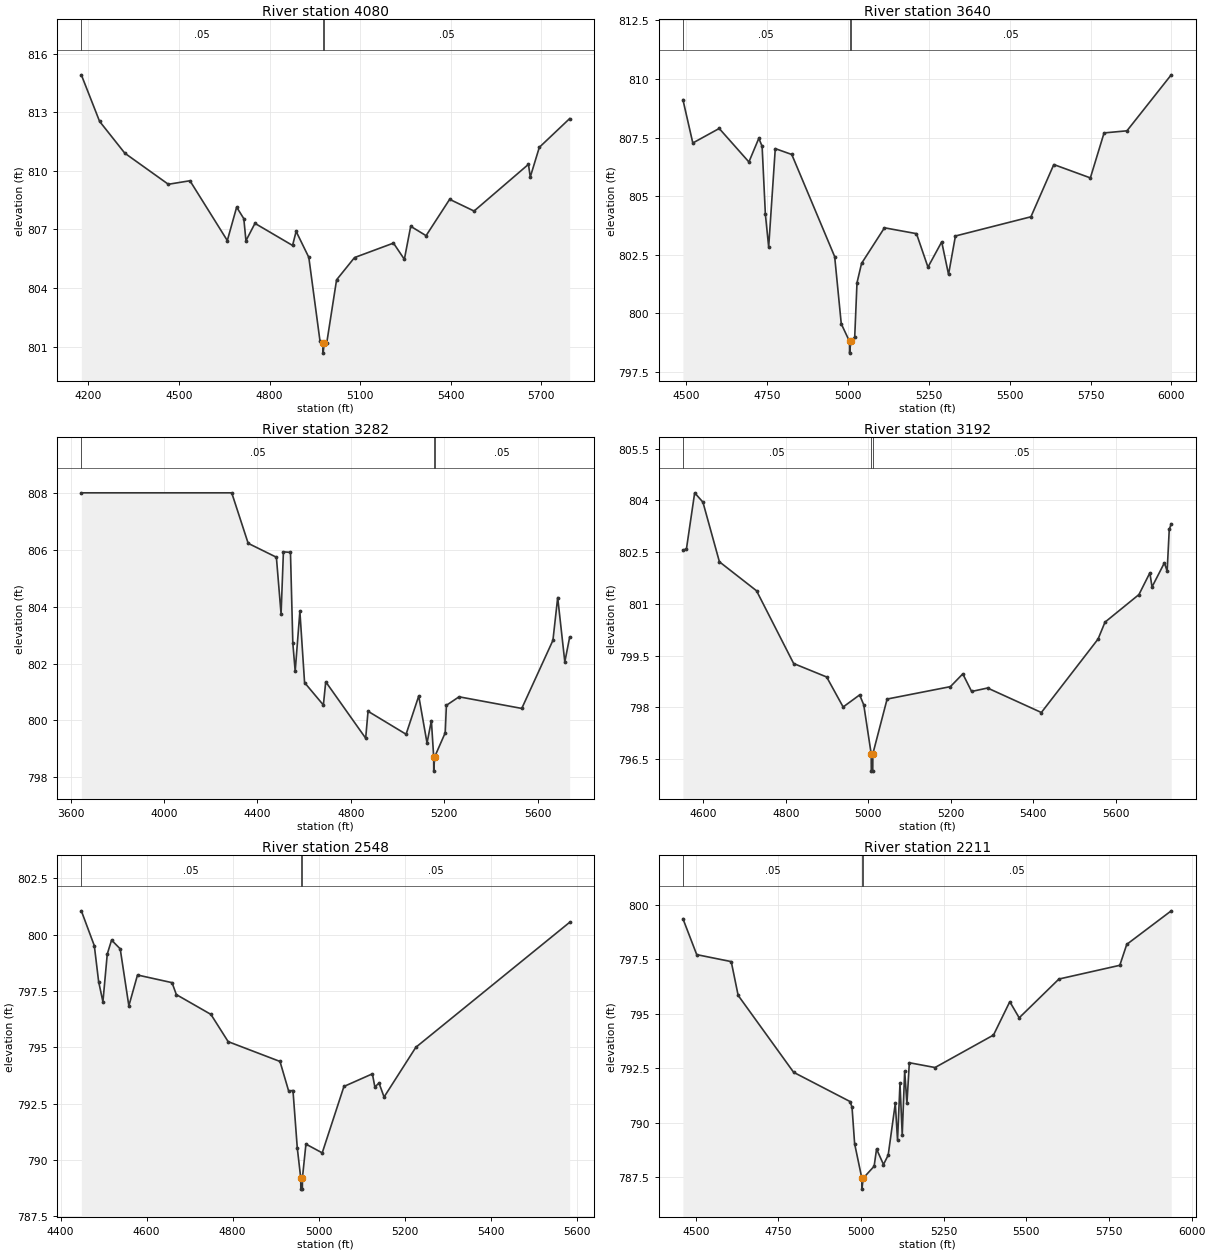
Type RM Length L Ch R = 1,4080,440,440,440
BEGIN DESCRIPTION:
Unnamed Tributary to Stream HEN-2 6.0
END DESCRIPTION:
XS GIS Cut Line= 3
      2307529.00      7035360.01      2307724.52      7034544.82
      2307079.02      7034110.02
#Sta/Elev= 30
  4176.9  814.91  4237.3  812.53  4320.9  810.90  4464.9  809.31  4536.5  809.49
  4660.2  806.43  4691.1  808.14  4714.8  807.55  4721.9  806.42  4751.7  807.31
  4876.2  806.18  4888.0  806.90  4930.0  805.57  4966.9  801.30  4977.0  801.17
  4977.3  800.67  4981.0  801.17  4989.3  801.19  5021.9  804.42  5081.3  805.56
  5210.3  806.30  5246.3  805.47  5267.3  807.16  5318.2  806.68  5396.2  808.54
  5477.1  807.94  5657.1  810.33  5663.1  809.68  5693.1  811.20  5793.5  812.67
#Mann=3,-1,0
  4176.9    0.05       0  4977.0   0.033       0  4981.0    0.05       0
Bank Sta=4977,4981
Exp/Cntr=0.3,0.1

Type RM Length L Ch R = 1,3640,358,358,358
BEGIN DESCRIPTION:
Unnamed Tributary to Stream HEN-2 5.0
END DESCRIPTION:
XS GIS Cut Line= 3
      2308029.00      7034960.00      2308129.00      7034460.00
      2307408.95      7033766.66
#Sta/Elev= 30
  4490.0  809.12  4520.6  807.27  4602.2  807.89  4694.0  806.46  4724.6  807.47
  4734.8  807.13  4744.9  804.23  4755.1  802.83  4775.5  807.03  4826.5  806.78
  4959.1  802.42  4979.5  799.55  5005.0  798.80  5005.2  798.30  5009.0  798.80
  5021.1  798.99  5028.1  801.30  5042.2  802.13  5113.0  803.65  5212.0  803.40
  5247.5  801.97  5290.0  803.05  5311.1  801.66  5332.4  803.30  5565.8  804.12
  5636.5  806.35  5749.5  805.78  5791.9  807.70  5862.6  807.79  5999.5  810.18
#Mann=3,-1,0
  4490.0    0.05       0  5005.0   0.033       0  5009.0    0.05       0
Bank Sta=5005,5009
Exp/Cntr=0.3,0.1

Type RM Length L Ch R = 1,3282,90,90,90
BEGIN DESCRIPTION:
Unnamed Tributary to Stream HEN-2 4.0
END DESCRIPTION:
XS GIS Cut Line= 4
      2308179.00      7035609.96      2308329.00      7034260.00
      2308270.66      7033929.49      2308196.37      7033539.69
#Sta/Elev= 30
  3646.1  808.02  4290.0  808.02  4360.4  806.24  4481.2  805.75  4501.3  803.75
  4511.3  805.94  4541.5  805.92  4551.6  802.72  4561.7  801.73  4581.8  803.84
  4601.9  801.33  4682.4  800.54  4692.5  801.36  4863.5  799.37  4873.6  800.32
  5036.5  799.51  5090.7  800.86  5126.2  799.20  5144.8  799.99  5154.7  798.71
  5154.9  798.21  5158.7  798.71  5204.0  799.56  5209.1  800.53  5263.3  800.83
  5531.8  800.42  5665.2  802.82  5685.6  804.33  5716.1  802.06  5736.8  802.93
#Mann=3,-1,0
  3646.1    0.05       0  5154.7    0.05       0  5158.7    0.05       0
Bank Sta=5154.7,5158.7
Exp/Cntr=0.3,0.1

Type RM Length L Ch R = 1,3192,644,644,644
BEGIN DESCRIPTION:
Unnamed Tributary to Stream HEN-2 3.0
END DESCRIPTION:
XS GIS Cut Line= 4
      2308417.88      7034708.54      2308417.88      7034211.87
      2308428.91      7033852.23      2308352.04      7033533.86
#Sta/Elev= 30
  4550.2  802.56  4558.7  802.59  4578.7  804.22  4598.7  803.95  4638.7  802.22
  4728.7  801.38  4818.7  799.27  4898.7  798.88  4938.7  798.01  4978.7  798.36
  4988.7  798.07  5006.7  796.65  5007.0  796.15  5010.5  796.15  5010.7  796.65
  5045.3  798.24  5198.8  798.60  5228.8  798.97  5250.2  798.46  5288.9  798.56
  5419.3  797.85  5556.8  799.98  5573.6  800.47  5655.9  801.27  5682.4  801.90
  5687.6  801.49  5717.6  802.19  5724.3  801.95  5729.4  803.16  5734.2  803.32
#Mann=3,-1,0
  4550.2    0.05       0  5006.7   0.033       0  5010.7    0.05       0
Bank Sta=5006.7,5010.7
Exp/Cntr=0.3,0.1

Type RM Length L Ch R = 1,2548,337,337,337
BEGIN DESCRIPTION:
Unnamed Tributary to Stream HEN-2 2.0
END DESCRIPTION:
XS GIS Cut Line= 3
      2308979.00      7034510.03      2308929.00      7033960.00
      2308429.00      7033660.00
#Sta/Elev= 30
  4448.2  801.06  4478.4  799.51  4488.4  797.92  4498.4  797.02  4508.5  799.14
  4518.5  799.76  4538.6  799.37  4558.7  796.84  4578.8  798.21  4659.1  797.87
  4669.1  797.34  4749.5  796.46  4789.6  795.25  4910.1  794.37  4930.2  793.06
  4940.3  793.08  4950.3  790.53  4958.3  789.20  4958.6  788.70  4962.1  788.70
  4962.3  789.20  4970.4  790.70  5008.3  790.31  5058.8  793.26  5124.9  793.82
  5130.7  793.24  5140.4  793.41  5152.1  792.79  5226.0  795.00  5583.6  800.55
#Mann=3,-1,0
  4448.2    0.05       0  4958.3    0.04       0  4962.3    0.05       0
Bank Sta=4958.3,4962.3
Exp/Cntr=0.3,0.1

Type RM Length L Ch R = 1,2211,460,460,460
BEGIN DESCRIPTION:
Unnamed Tributary to Stream HEN-2 1.0
END DESCRIPTION:
XS GIS Cut Line= 3
      2309028.99      7034360.05      2309179.00      7033860.00
      2308529.01      7033160.01
#Sta/Elev= 30
  4460.9  799.37  4502.7  797.72  4607.1  797.40  4628.0  795.85  4795.9  792.32
  4966.4  790.98  4972.5  790.72  4980.4  789.04  5002.2  787.46  5002.5  786.96
  5006.2  787.46  5039.4  788.01  5046.7  788.80  5067.7  788.09  5081.9  788.52
  5103.4  790.89  5110.2  789.21  5117.6  791.81  5124.4  789.45  5131.8  792.38
  5138.6  790.89  5145.9  792.76  5223.6  792.54  5400.5  794.03  5449.8  795.56
  5478.2  794.82  5598.4  796.60  5782.6  797.23  5803.6  798.19  5938.2  799.73
#Mann=3,-1,0
  4460.9    0.05       0  5002.2    0.04       0  5006.2    0.05       0
Bank Sta=5002.2,5006.2
Exp/Cntr=0.3,0.1

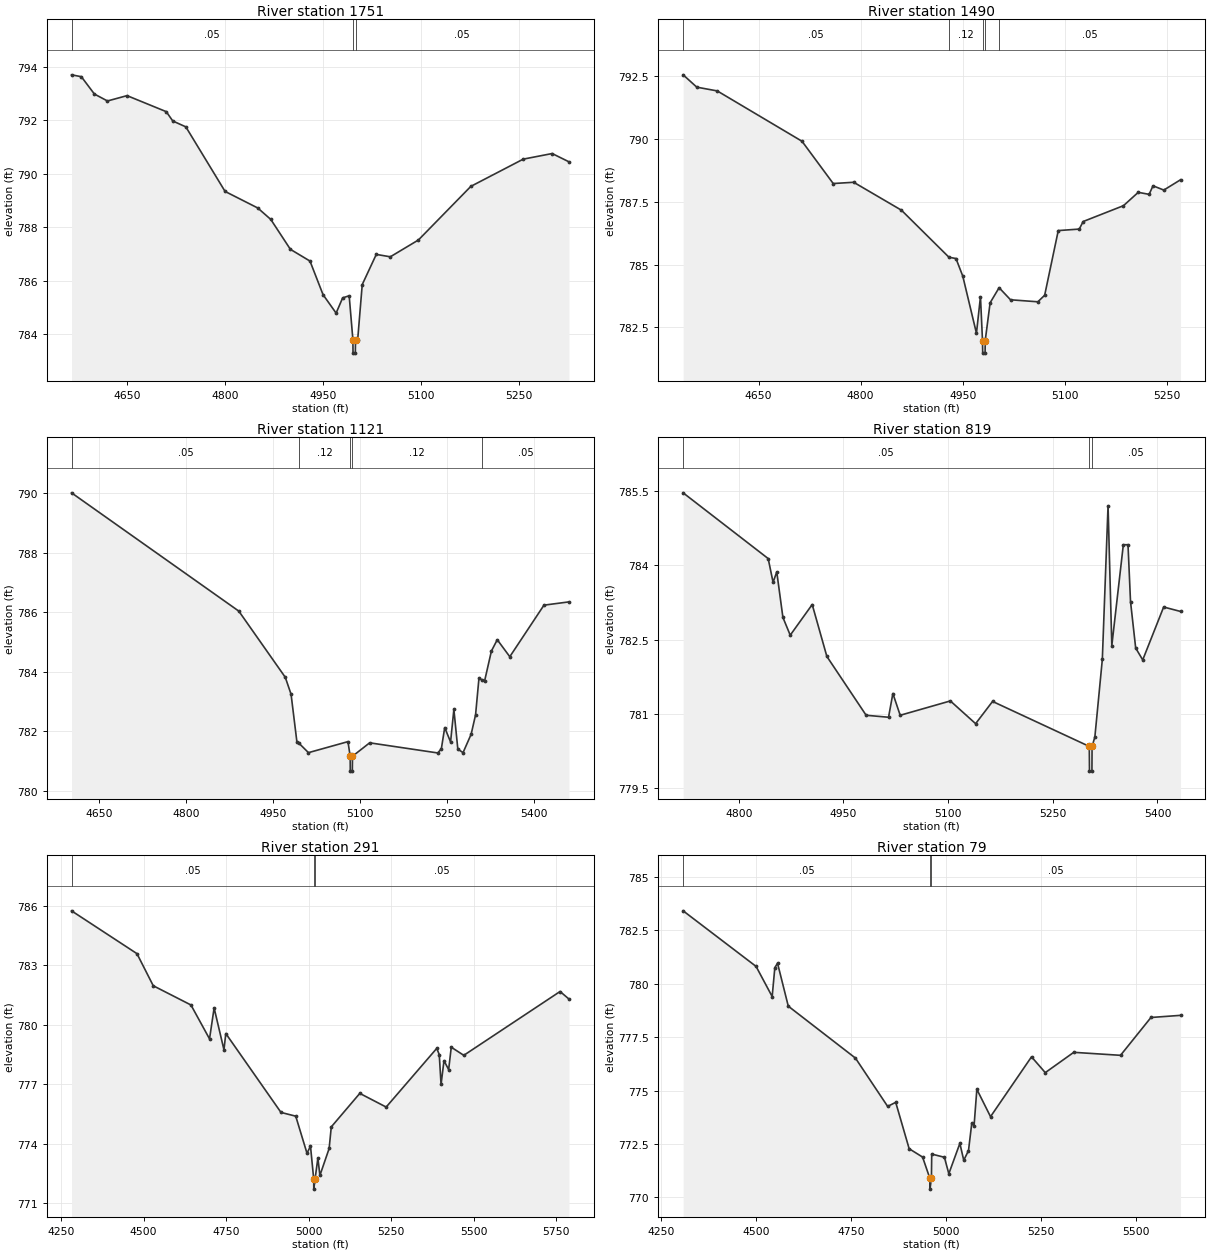
Type RM Length L Ch R = 1,1751,261,261,261
BEGIN DESCRIPTION:
UNT HEN-2 0.5
END DESCRIPTION:
XS GIS Cut Line= 3
      2309471.68      7034044.98      2309460.97      7033609.68
      2309296.85      7033327.82
#Sta/Elev= 30
  4564.5  793.71  4579.5  793.64  4599.5  792.99  4619.5  792.73  4649.5  792.93
  4709.5  792.33  4719.5  791.98  4739.5  791.76  4799.6  789.34  4849.6  788.72
  4869.6  788.29  4899.6  787.17  4929.6  786.73  4949.6  785.47  4969.6  784.78
  4979.6  785.35  4989.6  785.43  4995.3  783.78  4995.5  783.28  4999.0  783.28
  4999.3  783.78  5002.6  783.78  5009.6  785.85  5031.1  786.98  5052.6  786.89
  5095.6  787.52  5175.9  789.53  5256.1  790.55  5300.4  790.76  5326.1  790.45
#Mann=3,-1,0
  4564.5    0.05       0  4995.3    0.04       0  4999.3    0.05       0
Bank Sta=4995.3,4999.3
Exp/Cntr=0.3,0.1

Type RM Length L Ch R = 1,1490,369,369,369
BEGIN DESCRIPTION:
UNT HEN-2 0.4
END DESCRIPTION:
XS GIS Cut Line= 3
      2309707.18      7034020.06      2309664.36      7033456.25
      2309583.16      7033311.50
#Sta/Elev= 30
  4539.0  792.54  4559.1  792.05  4589.2  791.90  4713.8  789.90  4759.7  788.22
  4789.8  788.27  4860.0  787.16  4929.9  785.29  4940.2  785.24  4950.2  784.54
  4970.3  782.27  4976.2  783.72  4979.2  781.98  4979.5  781.48  4983.0  781.48
  4983.2  781.98  4990.4  783.48  5003.6  784.08  5020.4  783.60  5060.6  783.52
  5070.6  783.78  5090.6  786.35  5121.5  786.41  5127.2  786.71  5186.5  787.34
  5208.2  787.87  5224.2  787.79  5229.9  788.13  5245.8  787.96  5270.4  788.37
#Mann=5,-1,0
  4539.0    0.05       0  4929.9    0.12       0  4979.2    0.07       0
  4983.2    0.12       0  5003.6    0.05       0
Bank Sta=4979.2,4983.2
Exp/Cntr=0.3,0.1

Type RM Length L Ch R = 1,1121,302,302,302
BEGIN DESCRIPTION:
UNT TR HEN2 0.3
END DESCRIPTION:
XS GIS Cut Line= 3
      2310030.26      7033958.33      2310043.10      7033499.33
      2309844.74      7033153.80
#Sta/Elev= 30
  4602.0  790.01  4890.4  786.04  4970.5  783.82  4980.5  783.25  4990.5  781.66
  4994.4  781.60  5010.5  781.29  5078.6  781.66  5082.4  781.17  5082.6  780.67
  5086.1  780.67  5086.4  781.17  5116.0  781.62  5233.4  781.28  5239.6  781.42
  5245.4  782.13  5255.5  781.65  5261.2  782.74  5268.0  781.41  5277.0  781.29
  5291.0  781.91  5298.6  782.56  5304.4  783.78  5309.2  783.74  5314.1  783.69
  5325.9  784.70  5336.0  785.08  5357.6  784.51  5416.5  786.24  5459.6  786.35
#Mann=5,-1,0
  4602.0    0.05       0  4994.4    0.12       0  5082.4    0.07       0
  5086.4    0.12       0  5309.2    0.05       0
Bank Sta=5082.4,5086.4
Exp/Cntr=0.3,0.1

Type RM Length L Ch R = 1,819,528,528,528
BEGIN DESCRIPTION:
UNT HEN-2 0.2
END DESCRIPTION:
XS GIS Cut Line= 5
      2310213.84      7033706.05      2310324.46      7033363.48
      2310067.56      7033267.14      2310074.69      7033267.14
      2310078.26      7033195.82
#Sta/Elev= 30
  4720.2  785.47  4842.1  784.14  4849.1  783.66  4854.4  783.87  4863.2  782.95
  4873.7  782.59  4905.2  783.21  4926.2  782.16  4982.5  780.97  5014.6  780.93
  5020.8  781.41  5031.3  780.97  5103.2  781.26  5139.4  780.80  5163.7  781.25
  5302.3  780.34  5302.6  779.84  5306.1  779.84  5306.3  780.34  5310.3  780.53
  5321.0  782.10  5329.2  785.21  5334.6  782.38  5351.1  784.42  5357.8  784.42
  5361.4  783.27  5368.8  782.33  5378.9  782.09  5408.9  783.16  5433.1  783.07
#Mann=3,-1,0
  4720.2    0.05       0  5302.3   0.033       0  5306.3    0.05       0
Bank Sta=5302.3,5306.3
Exp/Cntr=0.3,0.1

Type RM Length L Ch R = 1,291,212,212,212
BEGIN DESCRIPTION:
UNT HEN-2 0.1
END DESCRIPTION:
XS GIS Cut Line= 6
      2310217.41      7033738.14      2310506.43      7033399.16
      2310659.86      7033092.30      2310624.18      7032949.58
      2310313.76      7033092.30      2310128.24      7033227.87
#Sta/Elev= 30
  4281.7  785.75  4479.9  783.59  4529.3  781.97  4643.5  781.00  4699.8  779.29
  4713.7  780.85  4743.5  778.74  4749.1  779.56  4916.3  775.58  4961.0  775.39
  4995.1  773.52  5005.7  773.88  5015.5  772.21  5015.7  771.71  5019.5  772.21
  5028.1  773.28  5034.2  772.40  5062.2  773.76  5068.7  774.85  5155.1  776.54
  5235.0  775.85  5388.2  778.81  5395.8  778.50  5401.3  776.99  5410.2  778.19
  5424.3  777.74  5432.2  778.87  5470.2  778.46  5761.9  781.68  5788.8  781.30
#Mann=3,-1,0
  4281.7    0.05       0  5015.5   0.033       0  5019.5    0.05       0
Bank Sta=5015.5,5019.5
Exp/Cntr=0.3,0.1

Type RM Length L Ch R = 1,79,0,0,0
BEGIN DESCRIPTION:
UNT Hen2 0.05
END DESCRIPTION:
XS GIS Cut Line= 6
      2310356.85      7033619.25      2310816.58      7033151.00
      2310833.61      7033061.61      2310765.51      7032959.45
      2310642.06      7032878.58      2310396.03      7033035.53
#Sta/Elev= 30
  4308.6  783.41  4500.6  780.81  4543.0  779.40  4550.0  780.75  4557.1  780.96
  4585.4  778.95  4762.2  776.52  4847.0  774.26  4868.2  774.45  4903.6  772.28
  4938.9  771.89  4958.2  770.89  4958.4  770.39  4962.2  770.89  4963.0  772.03
  4996.4  771.88  5008.0  771.11  5037.1  772.53  5047.3  771.74  5059.8  772.19
  5068.4  773.47  5074.5  773.36  5081.8  775.06  5117.8  773.78  5225.7  776.58
  5261.9  775.84  5336.9  776.79  5460.0  776.65  5540.1  778.42  5618.0  778.52
#Mann=3,-1,0
  4308.6    0.05       0  4958.2   0.033       0  4962.2    0.05       0
Bank Sta=4958.2,4962.2
Exp/Cntr=0.3,0.1

Chan Stop Cuts=-1