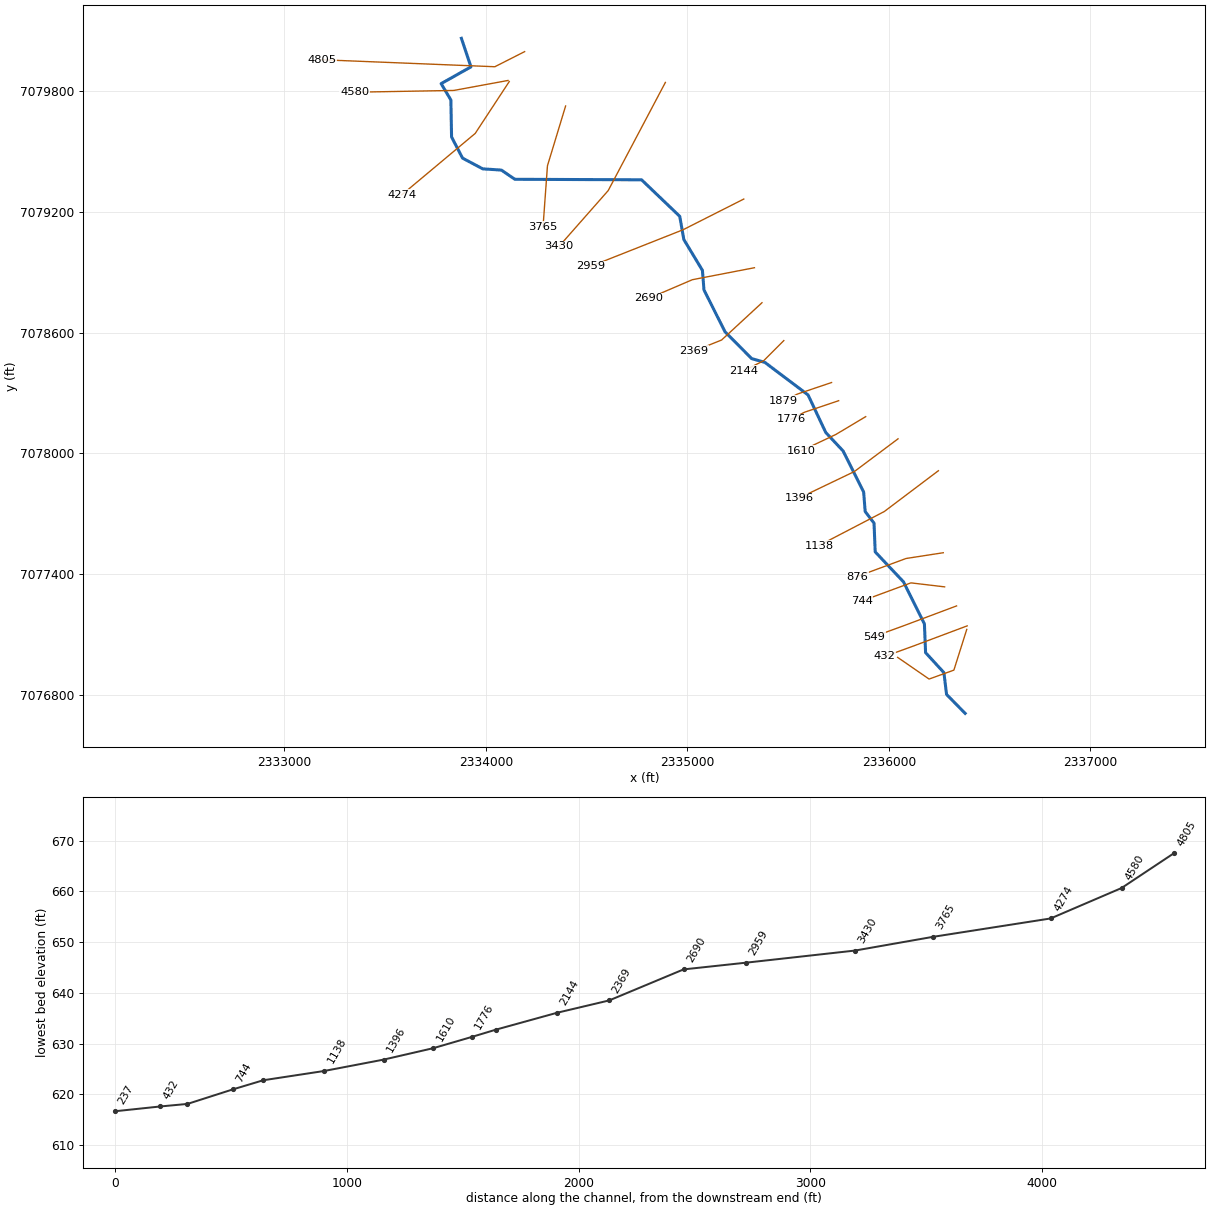
--- Unnamed Tr to Trail Creek.prj (project) ---

Proj Title=Unnamed Tr to Trail Creek Base Level Engineering
Current Plan=p01
Default Exp/Contr=0.3,0.1
English Units
Geom File=g01
Flow File=f01
Plan File=p01
Y Axis Title=Elevation
X Axis Title(PF)=Main Channel Distance
X Axis Title(XS)=Station
BEGIN DESCRIPTION:
Unnamed Tr to Trail Creek
END DESCRIPTION:
DSS Export Rating Curves= 0
DSS Export Rating Curve Sorted= 0
DSS Export Volume Flow Curves= 0
DXF OffsetX= 0
DXF OffsetY= 0
DXF ScaleX= 1
DXF ScaleY= 10

--- Unnamed Tr to Trail Creek.p01 (plan) ---

Plan Title=Multiple Run
Program Version=4.10
Short Identifier=Multiple
Geom File=g01
Flow File=f01
Subcritical Flow
K Sum by GR= 0
Std Step Tol= 0.01
Critical Tol= 0.01
Num of Std Step Trials= 20
Max Error Tol= 0.3
Flow Tol Ratio= 0.001
Split Flow NTrial= 30
Split Flow Tol= 0.02
Split Flow Ratio= 0.02
Log Output Level= 0
Friction Slope Method= 1
Unsteady Friction Slope Method= 2
Unsteady Bridges Friction Slope Method= 1
Parabolic Critical Depth
Global Vel Dist= 1 , 1 , 1
Global Log Level= 0
CheckData=True
Encroach Param=-1 ,0,0, 0
BEGIN DESCRIPTION:
Multiple Run
END DESCRIPTION:
Computation Interval=1HOUR
Output Interval=1HOUR
Run HTab= 0
Run UNet= 0
Run PostProcess= 0
Run WQNet= 0
UNET Theta= 1
UNET Theta Warmup= 1
UNET ZTol= 0.02
UNET ZSATol= 0.05
UNET MxIter= 20
UNET MaxInSteps= 0
UNET DtIC= 0
UNET DtMin= 0
UNET MaxCRTS= 20
UNET WFStab= 2
UNET SFStab= 1
UNET WFX= 1
UNET SFX= 1
UNET DSS MLevel= 4
UNET DZMax Abort= 100
UNET Convert EG Bridges= 0
UNET Use Existing IB Tables=-1
UNET Froude Reduction=False
UNET Froude Limit= 1
UNET Froude Power= 10
UNET Time Slicing=0,0, 5
UNET Junction Losses=0
Instantaneous Interval=1HOUR
Write IC File= 0
Write IC File at Sim End=0
Echo Input=False
Echo Parameters=False
Echo Output=False
Write Detailed= 0
WQ AD Non Conservative
WQ ULTIMATE=-1
WQ Max Comp Step=1HOUR
WQ Output Interval=15MIN
WQ Output Selected Increments= 0
WQ Output face flow=0
WQ Output face velocity=0
WQ Output face area=0
WQ Output face dispersion=0
WQ Output cell volume=0
WQ Output cell surface area=0
WQ Output cell continuity=0
WQ Output cumulative cell continuity=0
WQ Output face conc=0
WQ Output face dconc_dx=0
WQ Output face courant=0
WQ Output face peclet=0
WQ Output face adv mass=0
WQ Output face disp mass=0
WQ Output cell mass=0
WQ Output cell source sink temp=0
WQ Output cell source sink nsm=0
WQ Output MaxMinRange=-1
WQ Daily Max Min Mean=-1
WQ Daily Range=0
WQ Daily Time=0
WQ Create Restart=0
WQ Fixed Restart=0
WQ System Summary=0
WQ Use Fixed Temperature=0
Sorting and Armoring Iterations= 10
XS Update Threshold= 0.02
Hydraulics Update Threshold= 0.02
Energy Slope Method= 1
Volume Change Method= 0
XS Weighting Method= 0
Number of US Weighted Cross Sections= 1
Number of DS Weighted Cross Sections= 1
Upstream XS Weight=0.25
Main XS Weight=0.5
Downstream XS Weight=0.25
Number of DS XS's Weighted with US Boundary= 1
Upstream Boundary Weight= 1
Weight of XSs Associated with US Boundary= 0
Number of US XS's Weighted with DS Boundary= 1
Downstream Boundary Weight= 0.5
Weight of XSs Associated with DS Boundary= 0.5
Sediment Output Level= 4
Mass or Volume Output= 0
Output Increment Type= 1
Profile and TS Output Increment= 10
XS Output Flag= 0
XS Output Increment= 10
Disregard all LS=0
Disregard all Conn=0
Disregard all Breaches=0
Disregard all Pumps=0

--- Unnamed Tr to Trail Creek.f01 (steady flow) ---

Flow Title=Multiple
Number of Profiles=7
Profile Names=10-year,25-year,50-year,1pct_min,100-year,1pct_plu,500-year
River Rch & RM= Unnamed Tr to Tr,Reach-1,4805
     403     541     653     392     782    1561    1124
River Rch & RM= Unnamed Tr to Tr,Reach-1,744
     411     552     667     401     800    1595    1150
Boundary for River Rch & Prof#=Unnamed Tr to Tr,Reach-1,1
Up Type=0
Dn Type=3
Dn Slope=0.005
Boundary for River Rch & Prof#=Unnamed Tr to Tr,Reach-1,2
Up Type=0
Dn Type=3
Dn Slope=0.005
Boundary for River Rch & Prof#=Unnamed Tr to Tr,Reach-1,3
Up Type=0
Dn Type=3
Dn Slope=0.005
Boundary for River Rch & Prof#=Unnamed Tr to Tr,Reach-1,4
Up Type=0
Dn Type=3
Dn Slope=0.005
Boundary for River Rch & Prof#=Unnamed Tr to Tr,Reach-1,5
Up Type=0
Dn Type=3
Dn Slope=0.005
Boundary for River Rch & Prof#=Unnamed Tr to Tr,Reach-1,6
Up Type=0
Dn Type=3
Dn Slope=0.005
Boundary for River Rch & Prof#=Unnamed Tr to Tr,Reach-1,7
Up Type=0
Dn Type=3
Dn Slope=0.005

--- Unnamed Tr to Trail Creek.g01 (geometry) ---

Geom Title=Existing Conditions
Program Version=4.10

River Reach=Unnamed Tr to Tr,Reach-1
Reach XY= 30
        2333879.        7080060.      2333926.41      7079918.44
      2333778.46      7079835.13       2333826.7       7079754.1
      2333830.19      7079570.48      2333884.58      7079465.58
      2333984.94      7079412.32       2334077.4      7079406.14
      2334144.22      7079360.52      2334773.15      7079357.94
      2334962.54      7079176.75      2334982.83      7079061.59
      2335075.17      7078908.42      2335082.83      7078811.58
      2335187.14      7078603.94      2335319.32      7078470.78
      2335385.04      7078451.82      2335599.42      7078290.23
      2335687.16      7078103.95      2335773.15      7078012.29
      2335875.17      7077808.42      2335882.86       7077711.6
      2335926.73      7077654.06      2335932.54      7077511.47
      2336073.17       7077362.3      2336176.75      7077154.07
      2336182.56      7077011.47      2336273.46      7076912.42
      2336286.79       7076803.8        2336379.        7076710.

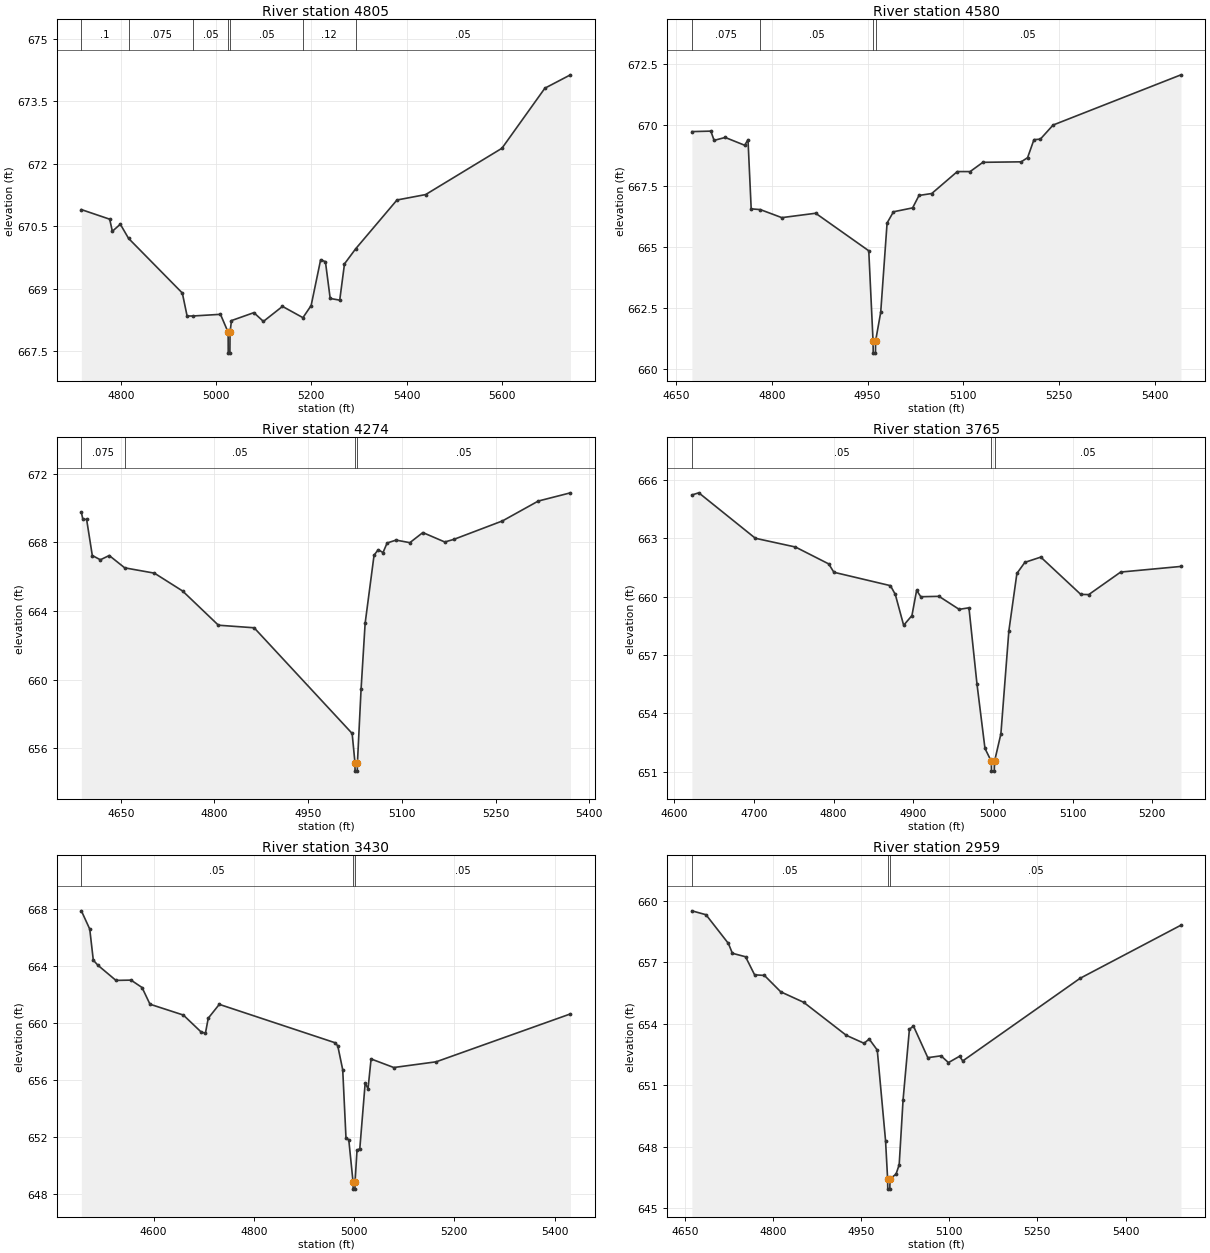
Type RM Length L Ch R = 1 ,4805    ,225,225,225
BEGIN DESCRIPTION:
Unnamed Tr to Trail Creek 15.0
END DESCRIPTION:
XS GIS Cut Line= 3
      2334192.79      7079994.01      2334045.06      7079919.07
      2333185.41      7079953.73
#Sta/Elev= 30
  4717.5   670.9  4776.9  670.67  4782.5  670.38  4799.2  670.55  4816.5  670.21
  4929.3   668.9  4939.3  668.35  4951.4  668.35  5009.3  668.39  5025.4  667.96
  5025.6  667.46  5029.1  667.46  5029.4  667.96  5032.4  668.24  5079.4  668.43
  5099.4  668.22  5139.4  668.58  5182.3  668.31  5199.5   668.6  5219.5   669.7
  5229.5  669.65  5239.5  668.77  5259.5  668.73  5269.5   669.6  5292.9  669.96
  5379.6  671.13  5439.7  671.26  5599.8  672.37  5689.9  673.81  5743.5  674.13
#Mann= 7 ,-1 , 0
  4717.5      .1       0  4816.5    .075       0  4951.4     .05       0
  5025.4    .033       0  5029.4     .05       0  5182.3     .12       0
  5292.9     .05       0
Bank Sta=5025.4,5029.4
XS Rating Curve= 0 ,0
Exp/Cntr=0.3,0.1

Type RM Length L Ch R = 1 ,4580    ,306,306,306
BEGIN DESCRIPTION:
Unnamed Tr to Trail Creek 14.0
END DESCRIPTION:
XS GIS Cut Line= 3
      2334110.31      7079850.92      2333841.46      7079801.44
       2333348.7      7079792.64
#Sta/Elev= 30
  4674.8  669.73  4704.5  669.75  4709.6  669.37    4727  669.49  4757.5  669.17
  4762.7   669.4  4767.7  666.56    4782  666.53  4815.7   666.2  4868.7  666.38
  4951.9  664.84  4958.6  661.14  4958.9  660.64  4962.4  660.64  4962.6  661.14
  4970.6  662.31  4980.6  665.98  4990.6  666.44  5020.6   666.6  5030.6  667.11
  5050.6  667.19  5090.6  668.09  5110.7  668.09  5130.7  668.47  5190.7  668.49
  5200.7  668.66  5210.7   669.4  5220.7  669.42  5240.7     670    5441  672.06
#Mann= 4 ,-1 , 0
  4674.8    .075       0    4782     .05       0  4958.6    .033       0
  4962.6     .05       0
Bank Sta=4958.6,4962.6
XS Rating Curve= 0 ,0
Exp/Cntr=0.3,0.1

Type RM Length L Ch R = 1 ,4274    ,509,509,509
BEGIN DESCRIPTION:
Unnamed Tr to Trail Creek 13.0
END DESCRIPTION:
XS GIS Cut Line= 3
      2334116.39      7079845.39      2333947.48      7079588.07
      2333582.97      7079283.21
#Sta/Elev= 30
  4586.9  669.76  4589.3  669.35  4595.3  669.35  4604.4  667.24  4617.3  666.99
  4631.5  667.24  4656.3  666.52  4703.8  666.21  4748.9  665.17  4806.3  663.17
  4863.5  663.02  5020.4  656.85  5024.9  655.15  5025.1  654.65  5028.6  654.65
  5028.9  655.15  5034.7  659.43  5041.2  663.28  5055.5  667.26  5062.2  667.58
  5069.8  667.41  5076.4  667.97  5090.7  668.14  5112.8  667.99  5133.6  668.58
  5168.7  668.03  5183.1  668.18  5261.1  669.26  5318.4  670.42  5369.9   670.9
#Mann= 4 ,-1 , 0
  4586.9    .075       0  4656.3     .05       0  5024.9    .033       0
  5028.9     .05       0
Bank Sta=5024.9,5028.9
XS Rating Curve= 0 ,0
Exp/Cntr=0.3,0.1

Type RM Length L Ch R = 1 ,3765    ,335,335,335
BEGIN DESCRIPTION:
Unnamed Tr to Trail Creek 12.0
END DESCRIPTION:
XS GIS Cut Line= 3
       2334396.2      7079724.42      2334306.03       7079427.5
      2334284.07       7079124.5
#Sta/Elev= 30
    4622  665.24  4630.7  665.35  4701.7  663.01    4752  662.56  4793.8  661.69
  4800.3  661.26  4871.3  660.57  4877.4  660.12  4887.9  658.53  4898.3  659.03
  4904.2  660.33  4909.4     660  4932.3  660.02  4957.6  659.35  4969.9  659.43
  4979.9  655.53    4990  652.19    4998  651.52  4998.2  651.02  5001.7  651.02
    5002  651.52    5010  652.94    5020  658.24  5030.1   661.2  5040.1  661.77
  5060.1  662.04  5110.3  660.12  5120.3  660.11  5160.4  661.27  5236.1  661.56
#Mann= 3 ,-1 , 0
    4622     .05       0    4998    .033       0    5002     .05       0
Bank Sta=4998,5002
XS Rating Curve= 0 ,0
Exp/Cntr=0.3,0.1

Type RM Length L Ch R = 1 ,3430    ,471,471,471
BEGIN DESCRIPTION:
Unnamed Tr to Trail Creek 11.0
END DESCRIPTION:
XS GIS Cut Line= 3
      2334891.14      7079841.04      2334607.38      7079304.32
       2334363.6       7079027.6
#Sta/Elev= 30
  4455.9  667.85  4472.6  666.57  4479.7  664.39    4489  664.03  4524.9  662.97
    4555  662.99    4577  662.47  4592.8   661.3  4659.4  660.54  4694.6  659.36
  4703.4  659.26  4709.1  660.32  4731.1  661.29  4961.9   658.6  4967.5  658.38
  4977.4   656.7  4983.9  651.93  4989.5  651.79    4998  648.83  4998.3  648.33
  5001.8  648.33    5002  648.83  5005.9  651.05  5011.5  651.17  5022.2  655.77
  5027.9  655.37    5034  657.46  5079.3  656.86  5163.8  657.26  5431.8  660.62
#Mann= 3 ,-1 , 0
  4455.9     .05       0    4998    .033       0    5002     .05       0
Bank Sta=4998,5002
XS Rating Curve= 0 ,0
Exp/Cntr=0.3,0.1

Type RM Length L Ch R = 1 ,2959    ,269,269,269
BEGIN DESCRIPTION:
Unnamed Tr to Trail Creek 10.0
END DESCRIPTION:
XS GIS Cut Line= 3
      2335280.45      7079262.52        2334979.        7079110.
       2334519.4      7078928.18
#Sta/Elev= 30
  4662.2  659.51  4686.2  659.32  4724.3  657.92  4731.1  657.44  4753.5  657.27
  4768.9  656.39  4785.6  656.36  4813.4  655.56  4852.4  655.05  4924.9  653.44
  4955.2  653.05  4963.8  653.26  4977.6  652.72  4991.7   648.3  4995.2  646.44
  4995.5  645.94    4999  645.94  4999.2  646.44  5009.5  646.67  5014.9  647.13
  5021.5  650.29  5032.3  653.74  5039.2  653.89  5063.6  652.35  5086.1  652.44
  5098.7  652.11  5117.7  652.42    5123  652.19  5322.7  656.22  5494.3  658.81
#Mann= 3 ,-1 , 0
  4662.2     .05       0  4995.2    .033       0  4999.2     .05       0
Bank Sta=4995.2,4999.2
XS Rating Curve= 0 ,0
Exp/Cntr=0.3,0.1

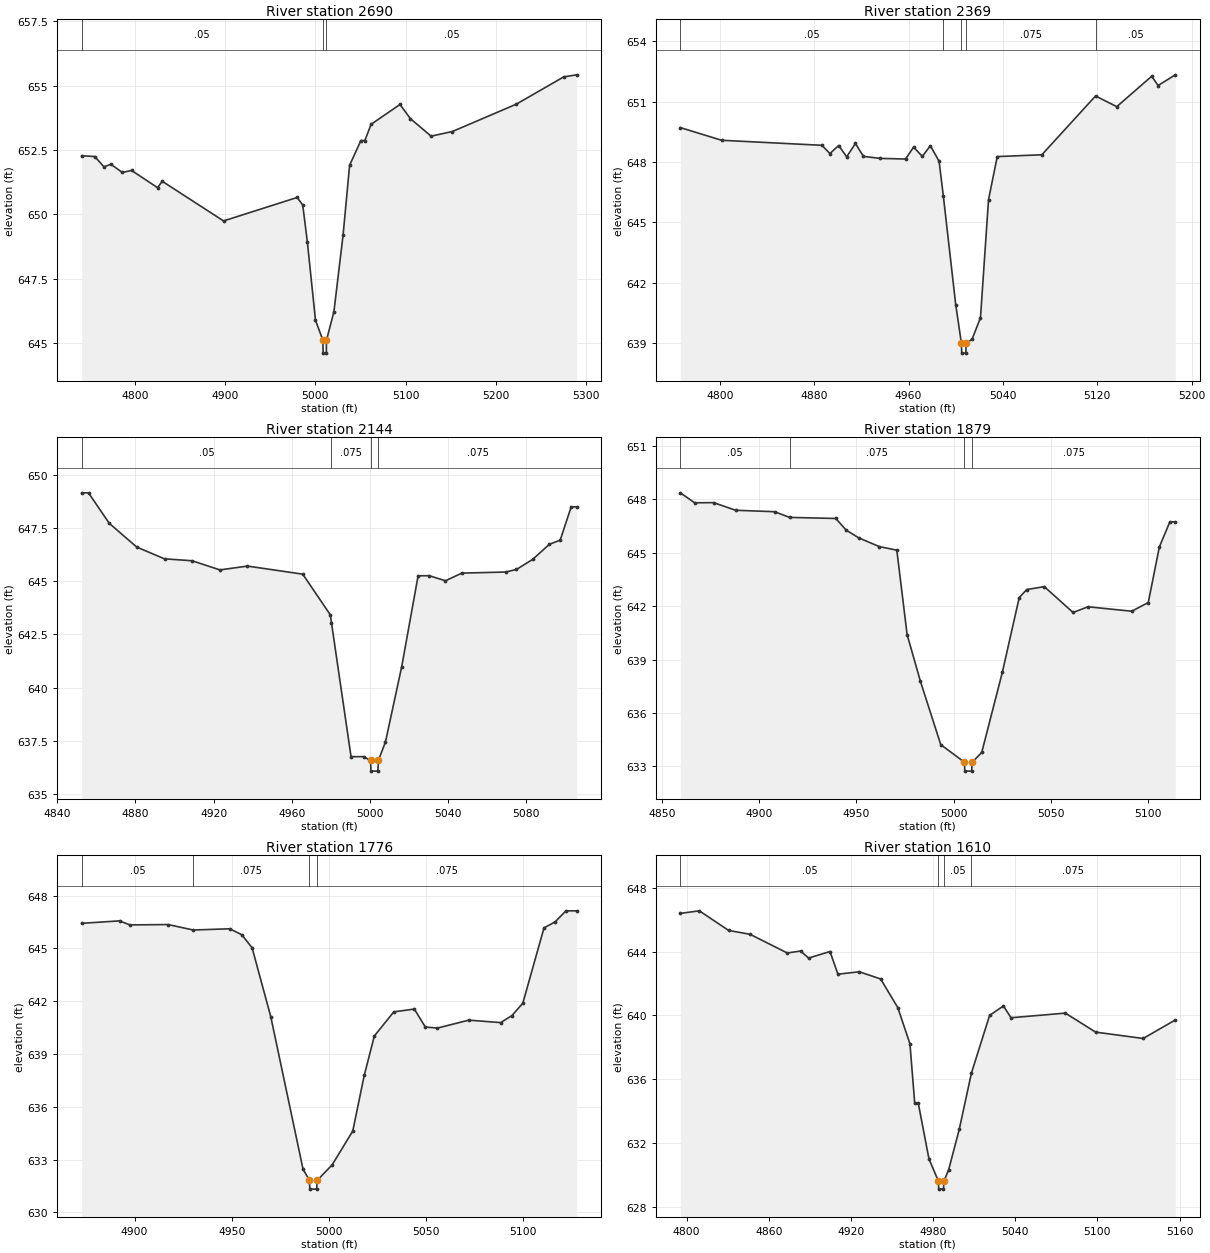
Type RM Length L Ch R = 1 ,2690    ,321,321,321
BEGIN DESCRIPTION:
Unnamed Tr to Trail Creek 9.0
END DESCRIPTION:
XS GIS Cut Line= 3
      2335333.25      7078921.58      2335025.31      7078862.19
      2334809.78      7078769.82
#Sta/Elev= 30
  4741.2  652.28  4755.7  652.25  4765.9  651.85  4773.5  651.95  4786.3  651.63
  4796.4  651.71  4825.3  651.04  4830.4  651.29  4898.3  649.75  4979.8  650.66
    4986  650.37  4991.1  648.94  5000.1   645.9  5008.3  645.12  5008.6  644.62
  5012.1  644.62  5012.3  645.12  5020.5  646.22  5030.7  649.21  5037.9  651.91
  5050.4  652.87  5054.8  652.87  5061.7   653.5  5093.7  654.27  5105.2  653.72
  5128.1  653.04  5151.7  653.22  5222.4  654.28    5275  655.34  5289.3  655.42
#Mann= 3 ,-1 , 0
  4741.2     .05       0  5008.3    .033       0  5012.3     .05       0
Bank Sta=5008.3,5012.3
XS Rating Curve= 0 ,0
Exp/Cntr=0.3,0.1

Type RM Length L Ch R = 1 ,2369    ,225,225,225
BEGIN DESCRIPTION:
Unnamed Tr to Trail Creek 8.0
END DESCRIPTION:
XS GIS Cut Line= 3
      2335370.67      7078747.83      2335170.48      7078563.04
      2335034.09      7078508.04
#Sta/Elev= 30
  4766.6  649.71  4801.6  649.08  4886.6  648.83  4893.4  648.42  4900.8  648.82
  4907.6  648.26    4915  648.92  4921.8  648.28    4936  648.18  4957.5  648.15
  4964.3  648.74  4971.7  648.28  4978.5  648.81  4985.9  648.04  4989.5  646.32
    5000  640.92  5004.8  639.01  5005.1  638.51  5008.6  638.51  5008.8  639.01
  5013.8  639.19    5021  640.27  5027.8  646.13  5035.2  648.27    5073  648.36
  5118.5  651.28  5136.5  650.75  5166.1  652.26  5171.5   651.8  5186.1  652.33
#Mann= 5 ,-1 , 0
  4766.6     .05       0  4989.5    .075       0  5004.8     .07       0
  5008.8    .075       0  5118.5     .05       0
Bank Sta=5004.8,5008.8
XS Rating Curve= 0 ,0
Exp/Cntr=0.3,0.1

Type RM Length L Ch R = 1 ,2144    ,265,265,265
BEGIN DESCRIPTION:
Unnamed Tr to Trail Creek 7.0
END DESCRIPTION:
XS GIS Cut Line= 3
      2335478.97      7078559.97        2335379.        7078460.
      2335278.99      7078409.99
#Sta/Elev= 30
  4852.5  649.15    4856  649.15  4866.6  647.72  4880.7   646.6  4894.9  646.05
    4909  645.96  4923.2  645.53  4937.3  645.71  4965.6  645.33  4979.7  643.42
  4980.3  643.04  4990.3  636.76  4996.7  636.76  5000.3  636.58  5000.5  636.08
    5004  636.08  5004.3  636.58  5007.9  637.45  5016.2  640.98  5024.6  645.25
  5030.2  645.26  5038.6  645.02    5047  645.38  5069.4  645.43  5074.9  645.55
  5083.3  646.03  5091.7  646.73  5097.3  646.93  5102.9  648.49  5105.7  648.49
#Mann= 4 ,-1 , 0
  4852.5     .05       0  4980.3    .075       0  5000.3     .07       0
  5004.3    .075       0
Bank Sta=5000.3,5004.3
XS Rating Curve= 0 ,0
Exp/Cntr=0.3,0.1

Type RM Length L Ch R = 1 ,1879    ,103,103,103
BEGIN DESCRIPTION:
Unnamed Tr to Trail Creek 6.0
END DESCRIPTION:
XS GIS Cut Line= 3
      2335715.97      7078351.87      2335546.62      7078294.69
      2335479.04      7078260.02
#Sta/Elev= 30
  4859.4  648.37  4866.8  647.81  4876.5  647.82  4887.9  647.39  4907.9  647.31
  4915.6  646.99  4939.4  646.93  4944.7  646.28  4951.2  645.84  4961.8  645.35
  4970.8  645.15  4976.1  640.41  4982.9   637.8  4993.4  634.23  5005.6  633.24
  5005.8  632.74  5009.3  632.74  5009.6  633.24  5014.5  633.79  5025.1  638.29
  5033.8  642.49  5037.7  642.94  5046.7   643.1  5061.5  641.65  5069.2  641.97
  5091.7  641.72  5100.2  642.21  5105.9  645.33  5111.3  646.74  5114.1  646.74
#Mann= 4 ,-1 , 0
  4859.4     .05       0  4915.6    .075       0  5005.6     .07       0
  5009.6    .075       0
Bank Sta=5005.6,5009.6
XS Rating Curve= 0 ,0
Exp/Cntr=0.3,0.1

Type RM Length L Ch R = 1 ,1776    ,166,166,166
BEGIN DESCRIPTION:
Unnamed Tr to Trail Creek 5.8
END DESCRIPTION:
XS GIS Cut Line= 3
      2335751.17      7078261.69      2335581.82       7078204.5
      2335514.24      7078169.84
#Sta/Elev= 30
  4872.8  646.42  4892.3  646.56  4897.6  646.33  4917.3  646.35  4930.2  646.04
    4949  646.11  4955.2  645.77  4960.5  645.03  4970.1  641.12  4986.7  632.46
    4990  631.82  4990.2  631.32  4993.7  631.32    4994  631.82  5001.7   632.7
  5012.3  634.62  5018.2  637.78  5023.4  640.02  5033.4  641.39    5044  641.55
  5049.6  640.53  5055.9  640.47    5072  640.92  5088.4  640.78  5094.2  641.18
  5099.8  641.88  5110.7  646.16  5116.4   646.5    5122  647.13  5127.5  647.13
#Mann= 4 ,-1 , 0
  4872.8     .05       0  4930.2    .075       0    4990     .07       0
    4994    .075       0
Bank Sta=4990,4994
XS Rating Curve= 0 ,0
Exp/Cntr=0.3,0.1

Type RM Length L Ch R = 1 ,1610    ,214,214,214
BEGIN DESCRIPTION:
Unnamed Tr to Trail Creek 5.0
END DESCRIPTION:
XS GIS Cut Line= 3
      2335885.36       7078182.5      2335737.99      7078094.52
      2335566.45      7078013.15
#Sta/Elev= 30
  4795.4  646.39  4809.3  646.55  4830.7  645.32  4846.3  645.08  4873.5  643.91
  4883.3  644.03  4889.1  643.59  4904.7     644  4910.5  642.58  4926.1  642.73
  4941.7  642.28  4954.2  640.49  4963.1  638.22  4966.6  634.49  4969.2  634.49
    4977     631  4983.9  629.61  4984.1  629.11  4987.6  629.11  4987.9  629.61
  4991.4  630.33  4999.1  632.85    5008  636.38  5021.3     640  5031.4  640.59
  5036.9  639.85  5076.6  640.14  5098.7  638.95  5133.4  638.55  5156.9  639.71
#Mann= 4 ,-1 , 0
  4795.4     .05       0  4983.9    .033       0  4987.9     .05       0
    5008    .075       0
Bank Sta=4983.9,4987.9
XS Rating Curve= 0 ,0
Exp/Cntr=0.3,0.1

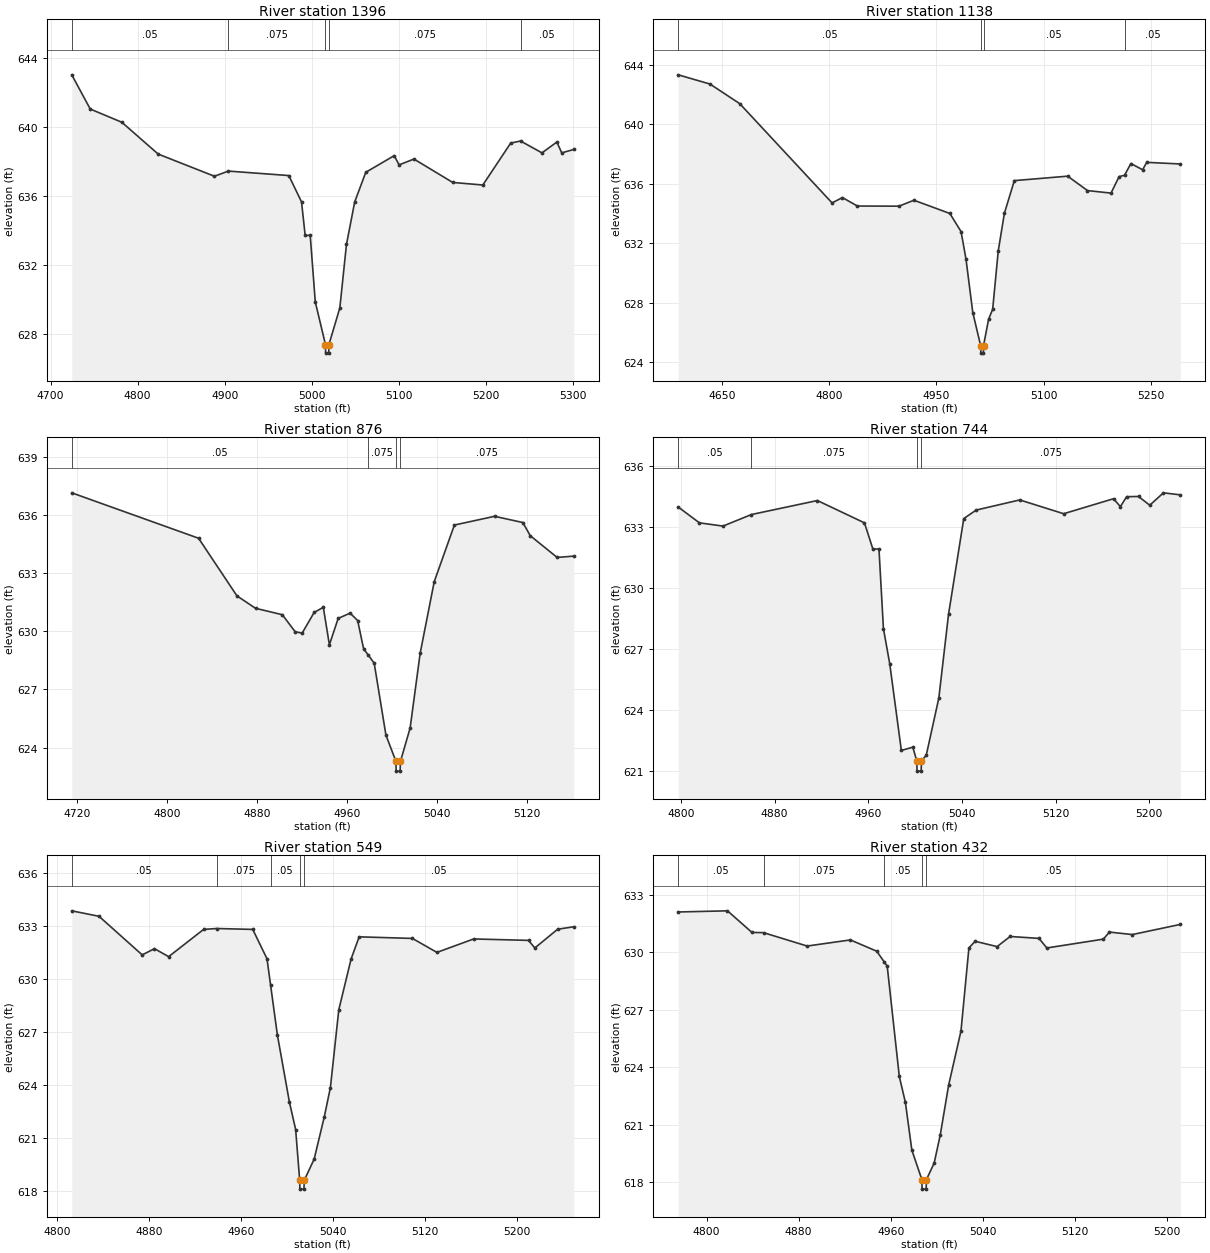
Type RM Length L Ch R = 1 ,1396    ,258,258,258
BEGIN DESCRIPTION:
Unnamed Tr to Trail Creek 4.0
END DESCRIPTION:
XS GIS Cut Line= 3
      2336045.95      7078072.53        2335829.        7077910.
       2335553.6      7077777.95
#Sta/Elev= 30
  4724.4  643.05  4745.6  641.06  4781.9  640.29  4823.6  638.44  4888.2  637.15
  4904.3  637.45  4973.6  637.19  4988.2  635.66  4992.4  633.71  4998.2  633.71
    5004  629.84  5015.7  627.36  5015.9  626.86  5019.4  626.86  5019.7  627.36
  5032.2  629.49  5039.8  633.18  5049.3  635.66    5062  637.38  5094.7  638.35
  5100.2  637.81  5117.3  638.15  5161.8  636.79  5196.4  636.64  5228.4  639.08
  5239.7   639.2  5264.3  638.51  5281.4  639.14    5287  638.51  5300.9  638.71
#Mann= 5 ,-1 , 0
  4724.4     .05       0  4904.3    .075       0  5015.7     .07       0
  5019.7    .075       0  5239.7     .05       0
Bank Sta=5015.7,5019.7
XS Rating Curve= 0 ,0
Exp/Cntr=0.3,0.1

Type RM Length L Ch R = 1 ,1138    ,262,262,262
BEGIN DESCRIPTION:
Unnamed Tr to Trail Creek 3.0
END DESCRIPTION:
XS GIS Cut Line= 3
      2336246.14      7077914.17      2335977.75      7077711.78
      2335653.11      7077542.88
#Sta/Elev= 30
  4589.1  643.34  4633.5  642.72  4675.1   641.4  4804.2  634.72  4818.7  635.08
  4839.6  634.51  4897.8   634.5  4918.7   634.9  4968.9  634.01  4984.6  632.79
  4991.5  630.94    5001  627.34    5012  625.11  5012.3  624.61  5015.8  624.61
    5016  625.11  5023.1  626.89  5028.8  627.56  5036.6  631.49  5045.2  634.02
  5059.1  636.22  5133.7  636.52  5161.4  635.55  5194.3  635.38  5205.6  636.49
  5213.2  636.58  5222.1  637.37  5238.5  636.95  5244.2  637.45  5291.2  637.34
#Mann= 4 ,-1 , 0
  4589.1     .05       0    5012    .033       0    5016     .05       0
  5213.2     .05       0
Bank Sta=5012,5016
XS Rating Curve= 0 ,0
Exp/Cntr=0.3,0.1

Type RM Length L Ch R = 1 ,876     ,132,132,132
BEGIN DESCRIPTION:
Unnamed Tr to Trail Creek 2.5
END DESCRIPTION:
XS GIS Cut Line= 3
      2336270.31      7077507.22      2336085.53      7077478.62
      2335842.65      7077388.91
#Sta/Elev= 30
  4715.5  637.13  4828.1  634.79  4862.2  631.82  4878.7  631.18  4902.5  630.85
  4913.9  629.97  4920.1   629.9  4930.8  630.97  4938.9  631.23  4944.3   629.3
  4952.1  630.66  4962.7  630.93  4969.4  630.55  4974.7  629.09  4978.7  628.78
  4984.1  628.35  4994.5  624.65  5003.4  623.29  5003.6  622.79  5007.1  622.79
  5007.4  623.29    5016  625.01  5024.9  628.86  5037.4  632.55  5055.3  635.47
    5091  635.92  5116.1   635.6  5122.7  634.92  5146.6   633.8  5161.4  633.87
#Mann= 4 ,-1 , 0
  4715.5     .05       0  4978.7    .075       0  5003.4     .07       0
  5007.4    .075       0
Bank Sta=5003.4,5007.4
XS Rating Curve= 0 ,0
Exp/Cntr=0.3,0.1

Type RM Length L Ch R = 1 ,744     ,195,195,195
BEGIN DESCRIPTION:
Unnamed Tr to Trail Creek 2.0
END DESCRIPTION:
XS GIS Cut Line= 3
      2336276.94      7077337.84      2336109.73      7077357.64
      2335865.53      7077267.44
#Sta/Elev= 30
  4797.8     634  4815.9  633.22    4836  633.06  4860.3  633.63  4916.6  634.32
  4956.8  633.22    4964  631.93  4969.2  631.93    4973  628.01  4978.4  626.27
  4988.3     622  4998.1  622.16  5001.5  621.48  5001.7  620.98  5005.2  620.98
  5005.5  621.48  5009.6  621.77  5020.3  624.58  5028.6  628.71  5041.6  633.43
  5052.2  633.85  5089.4  634.35  5126.9  633.67  5169.5  634.41  5175.3  634.02
  5180.7  634.51  5190.8  634.52  5200.4  634.09  5212.1   634.7  5226.5   634.6
#Mann= 4 ,-1 , 0
  4797.8     .05       0  4860.3    .075       0  5001.5     .07       0
  5005.5    .075       0
Bank Sta=5001.5,5005.5
XS Rating Curve= 0 ,0
Exp/Cntr=0.3,0.1

Type RM Length L Ch R = 1 ,549     ,117,117,117
BEGIN DESCRIPTION:
Unnamed Tr to Trail Creek 1.0
END DESCRIPTION:
XS GIS Cut Line= 3
      2336336.32      7077243.27      2336072.34      7077144.27
      2335927.18      7077091.49
#Sta/Elev= 30
    4813  633.86  4836.7  633.55  4874.2  631.37  4884.9  631.72  4897.2  631.27
  4927.6  632.81  4938.8  632.86  4970.3  632.81  4982.7  631.15  4985.8  629.67
  4991.7  626.85  5002.2  623.04  5007.6   621.5  5011.1  618.63  5011.3  618.13
  5014.8  618.13  5015.1  618.63  5023.7  619.83  5032.5  622.22  5037.8  623.87
  5045.1  628.27  5055.8  631.14  5062.8  632.39  5109.1   632.3  5130.4  631.51
  5162.3  632.27    5210  632.19  5215.5  631.76  5235.3  632.82  5249.4  632.96
#Mann= 5 ,-1 , 0
    4813     .05       0  4938.8    .075       0  4985.8     .05       0
  5011.1     .05       0  5015.1     .05       0
Bank Sta=5011.1,5015.1
XS Rating Curve= 0 ,0
Exp/Cntr=0.3,0.1

Type RM Length L Ch R = 1 ,432     ,195,195,195
BEGIN DESCRIPTION:
Unnamed Tr to Trail Creek 0.8
END DESCRIPTION:
XS GIS Cut Line= 3
      2336389.05      7077144.26      2336125.13      7077045.29
        2335980.      7076992.52
#Sta/Elev= 30
  4775.4  632.11  4818.2  632.17  4839.5  631.04  4849.5  631.03  4887.4  630.33
    4925  630.65  4947.9  630.06  4954.3  629.51    4957  629.28  4967.5  623.52
  4972.8  622.16  4978.4  619.67  4987.1  618.13  4987.3  617.63  4990.8  617.63
  4991.1  618.13  4997.8  618.99  5003.1  620.46  5010.4  623.07  5021.1  625.89
    5028  630.23  5033.4  630.58  5052.5   630.3  5063.8  630.83  5088.9  630.73
  5095.7  630.23  5144.8  630.69  5150.1  631.06    5170  630.93  5211.7  631.46
#Mann= 5 ,-1 , 0
  4775.4     .05       0  4849.5    .075       0  4954.3     .05       0
  4987.1     .05       0  4991.1     .05       0
Bank Sta=4987.1,4991.1
XS Rating Curve= 0 ,0
Exp/Cntr=0.3,0.1

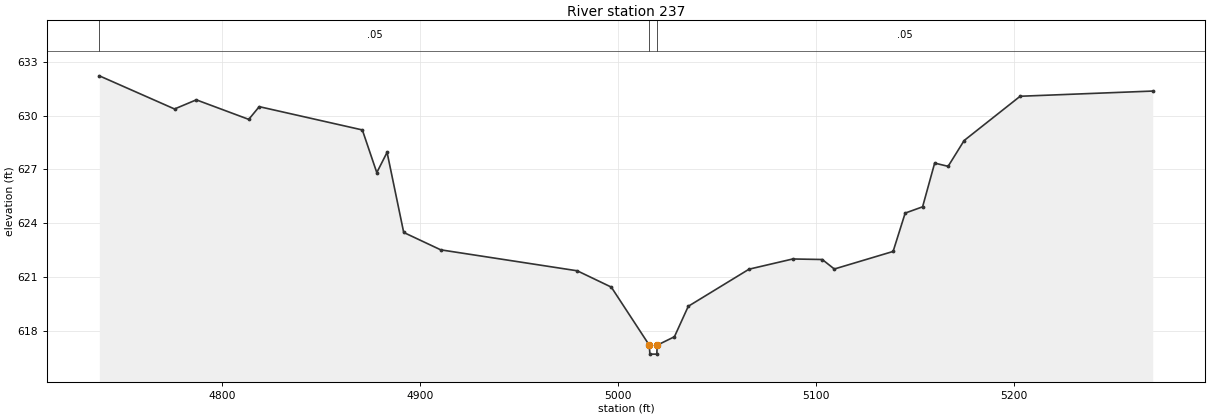
Type RM Length L Ch R = 1 ,237     ,0,0,0
BEGIN DESCRIPTION:
Unnamed Tr to Trail Creek 0.5
END DESCRIPTION:
XS GIS Cut Line= 4
      2336386.89      7077126.68      2336322.98      7076924.62
      2336199.91      7076880.32      2336043.89        7076988.
#Sta/Elev= 30
  4737.8  632.22  4775.8  630.37  4786.8  630.88  4813.3  629.79  4818.6   630.5
  4870.7   629.2    4878  626.82  4883.2  627.95  4891.6  623.48  4910.3  622.51
  4979.3  621.34  4996.5  620.43  5015.7  617.19    5016  616.69  5019.5  616.69
  5019.7  617.19  5028.4  617.66  5035.4  619.36  5066.1  621.43  5088.2     622
  5103.1  621.97  5109.2  621.44  5138.9  622.42    5145  624.56  5153.8  624.91
  5159.9  627.35  5166.7  627.17  5174.8  628.61  5203.1  631.08  5270.1  631.37
#Mann= 3 ,-1 , 0
  4737.8     .05       0  5015.7    .033       0  5019.7     .05       0
Bank Sta=5015.7,5019.7
XS Rating Curve= 0 ,0
Exp/Cntr=0.3,0.1

Chan Stop Cuts=-1
Use User Specified Reach Order=0
Composite Channel Slope=5