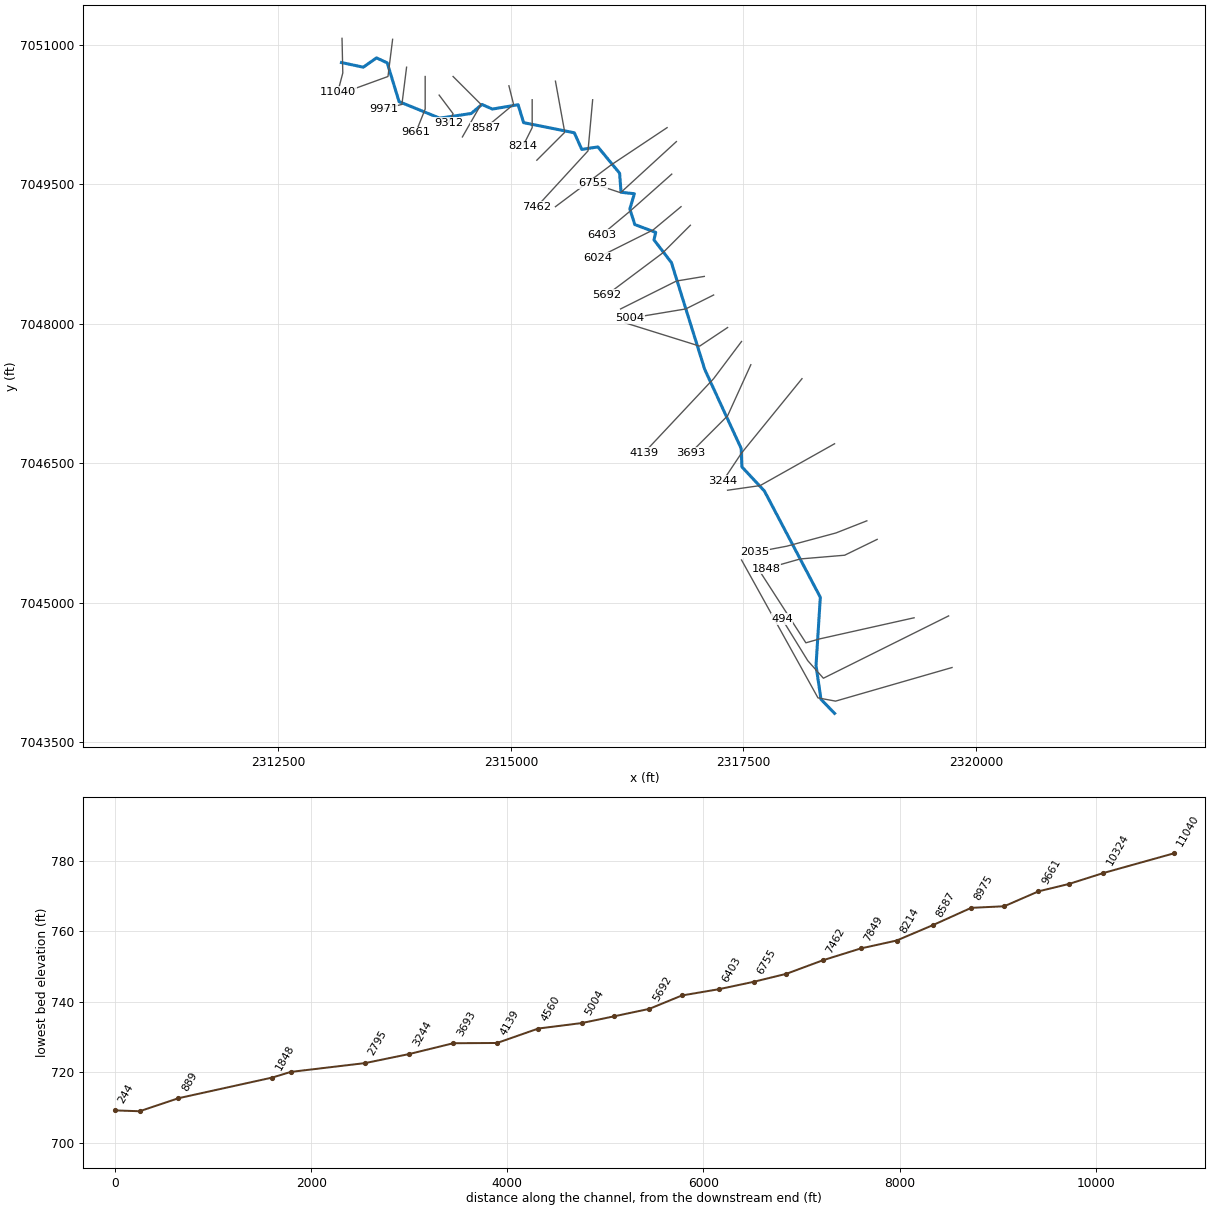
--- Unnamed Tr to Walnut Cr 2A.prj (project) ---

Proj Title=Unnamed Tr to Walnut Cr 2A Base Level Engineering
Current Plan=p01
Default Exp/Contr=0.3,0.1
English Units
Geom File=g01
Flow File=f01
Plan File=p01
BEGIN DESCRIPTION:
Unnamed Tr to Walnut Cr 2A
END DESCRIPTION:

--- Unnamed Tr to Walnut Cr 2A.p01 (plan) ---

Plan Title=Multiple Run
Short Identifier=Multiple
Geom File=g01
Flow File=f01
Subcritical Flow
K Sum by GR= 0
Std Step Tol= 0.01
Critical Tol= 0.01
Num of Std Step Trials= 20
Max Error Tol= 0.3
Flow Tol Ratio= 0.001
Split Flow NTrial= 30
Split Flow Tol= 0.02
Split Flow Ratio= 0.02
Log Output Level= 0
Friction Slope Method= 1
Unsteady Friction Slope Method= 2
Unsteady Bridges Friction Slope Method= 1
Parabolic Critical Depth
Global Vel Dist=  1 , 1 , 1
Global Log Level= 0
CheckData=True
Encroach Param= -1, 0, 0, 0
BEGIN DESCRIPTION:
Multiple Run
END DESCRIPTION:

--- Unnamed Tr to Walnut Cr 2A.f01 (steady flow) ---

Flow Title=Multiple
Number of Profiles=7
Profile Names=10-year,25-year,50-year,1pct_min,100-year,1pct_plu,500-year
River Rch & RM= Unnamed Tr to Wa,Reach-1,11040
     334     440     524     310     619    1230     865
River Rch & RM= Unnamed Tr to Wa,Reach-1,10324
     560     762     927     560    1120    2230    1630
River Rch & RM= Unnamed Tr to Wa,Reach-1,4139
     936    1300    1600     979    1950    3900    2900
Boundary for River Rch & Prof#=Unnamed Tr to Wa,Reach-1,1
Up Type=0
Dn Type=3
Dn Slope=0.005
Boundary for River Rch & Prof#=Unnamed Tr to Wa,Reach-1,2
Up Type=0
Dn Type=3
Dn Slope=0.005
Boundary for River Rch & Prof#=Unnamed Tr to Wa,Reach-1,3
Up Type=0
Dn Type=3
Dn Slope=0.005
Boundary for River Rch & Prof#=Unnamed Tr to Wa,Reach-1,4
Up Type=0
Dn Type=3
Dn Slope=0.005
Boundary for River Rch & Prof#=Unnamed Tr to Wa,Reach-1,5
Up Type=0
Dn Type=3
Dn Slope=0.005
Boundary for River Rch & Prof#=Unnamed Tr to Wa,Reach-1,6
Up Type=0
Dn Type=3
Dn Slope=0.005
Boundary for River Rch & Prof#=Unnamed Tr to Wa,Reach-1,7
Up Type=0
Dn Type=3
Dn Slope=0.005

--- Unnamed Tr to Walnut Cr 2A.g01 (geometry) ---

Geom Title=Existing Conditions

River Reach=Unnamed Tr to Wa,Reach-1
Reach XY= 30
      2313179.00      7050810.00      2313413.82      7050760.37
      2313556.18      7050860.48      2313670.91      7050806.66
      2313798.56      7050389.49      2314234.89      7050211.97
      2314573.14      7050262.07      2314688.78      7050359.24
      2314801.80      7050309.63      2315077.78      7050356.57
      2315136.80      7050163.51      2315681.71      7050054.60
      2315761.87      7049876.03      2315935.34      7049902.63
      2316168.52      7049619.80      2316184.01      7049415.01
      2316327.40      7049399.16      2316278.60      7049235.00
      2316332.16      7049067.66      2316556.50      7048983.39
      2316538.23      7048903.07      2316725.44      7048658.53
      2317082.75      7047511.53      2317475.45      7046658.53
      2317482.75      7046461.55      2317725.16      7046201.38
      2318325.86      7045058.36      2318279.68      7044323.92
      2318332.75      7043961.55      2318479.00      7043810.00

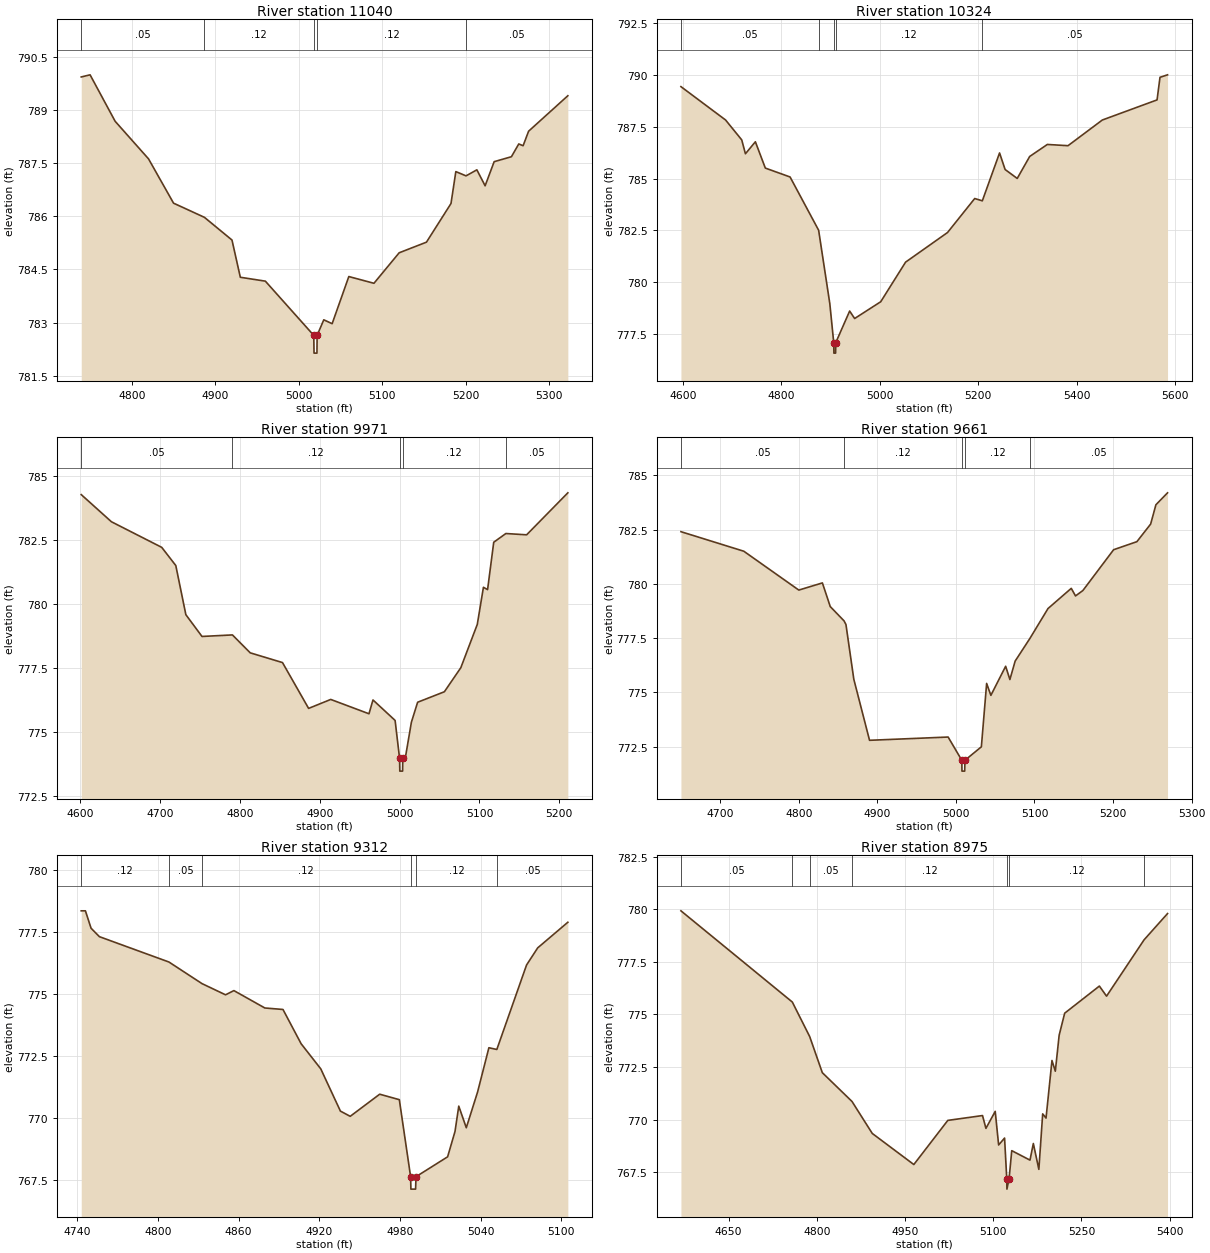
Type RM Length L Ch R = 1,11040,716,716,716
BEGIN DESCRIPTION:
Unnamed Trib to Walnut Creek 2A 26.0
END DESCRIPTION:
XS GIS Cut Line= 3
      2313185.24      7051070.57      2313193.49      7050697.76
      2313139.95      7050494.59
#Sta/Elev= 30
  4739.5  789.93  4750.1  789.99  4780.1  788.68  4820.1  787.62  4850.1  786.37
  4887.1  785.97  4920.1  785.33  4930.1  784.28  4960.1  784.17  5018.1  782.64
  5018.4  782.14  5021.9  782.14  5022.1  782.64  5030.1  783.08  5040.1  782.97
  5060.1  784.30  5090.2  784.11  5120.4  784.97  5153.1  785.27  5182.5  786.36
  5188.3  787.26  5200.5  787.14  5213.5  787.31  5223.4  786.86  5234.2  787.54
  5254.9  787.68  5263.7  788.04  5268.9  787.99  5275.5  788.40  5322.5  789.40
#Mann=5,-1,0
  4739.5    0.05       0  4887.1    0.12       0  5018.1    0.07       0
  5022.1    0.12       0  5200.5    0.05       0
Bank Sta=5018.1,5022.1
Exp/Cntr=0.3,0.1

Type RM Length L Ch R = 1,10324,353,353,353
BEGIN DESCRIPTION:
Unnamed Tributary to Walnut Creek 2A 25.0
END DESCRIPTION:
XS GIS Cut Line= 3
      2313729.00      7051060.03      2313679.00      7050660.00
      2313128.98      7050459.99
#Sta/Elev= 30
  4596.4  789.44  4687.1  787.83  4719.9  786.87  4727.4  786.20  4747.6  786.78
  4767.8  785.51  4818.1  785.08  4876.1  782.51  4898.8  778.97  4906.8  777.08
  4907.1  776.58  4910.6  776.58  4910.8  777.08  4939.1  778.61  4949.2  778.25
  5002.2  779.06  5052.7  780.97  5137.9  782.40  5193.1  784.04  5208.6  783.93
  5243.6  786.24  5254.9  785.44  5279.5  785.01  5304.8  786.07  5340.7  786.65
  5382.6  786.59  5452.4  787.83  5563.5  788.80  5569.5  789.89  5584.8  790.01
#Mann=5,-1,0
  4596.4    0.05       0  4876.1    0.12       0  4906.8    0.07       0
  4910.8    0.12       0  5208.6    0.05       0
Bank Sta=4906.8,4910.8
Exp/Cntr=0.3,0.1

Type RM Length L Ch R = 1,9971,310,310,310
BEGIN DESCRIPTION:
Unnamed Tributary to Walnut Creek 2A 24.0
END DESCRIPTION:
XS GIS Cut Line= 3
      2313879.00      7050760.01      2313829.00      7050360.00
      2313628.98      7050309.99
#Sta/Elev= 30
  4601.4  784.26  4639.2  783.20  4702.2  782.20  4719.8  781.49  4732.4  779.57
  4752.6  778.72  4790.7  778.78  4813.0  778.08  4853.4  777.70  4886.1  775.91
  4913.8  776.26  4961.7  775.70  4966.7  776.24  4994.4  775.44  5000.0  773.96
  5000.3  773.46  5003.8  773.46  5004.0  773.96  5007.1  773.96  5014.8  775.37
  5022.6  776.15  5056.1  776.56  5076.7  777.50  5097.3  779.19  5105.0  780.64
  5110.2  780.55  5117.9  782.40  5133.1  782.74  5159.1  782.69  5210.7  784.33
#Mann=5,-1,0
  4601.4    0.05       0  4790.7    0.12       0  5000.0    0.07       0
  5004.0    0.12       0  5133.1    0.05       0
Bank Sta=5000,5004
Exp/Cntr=0.3,0.1

Type RM Length L Ch R = 1,9661,349,349,349
BEGIN DESCRIPTION:
Unnamed Tributary to Walnut Creek 2A 23.0
END DESCRIPTION:
XS GIS Cut Line= 3
      2314079.00      7050659.95      2314079.00      7050310.00
      2313979.00      7050060.01
#Sta/Elev= 30
  4650.1  782.40  4730.1  781.50  4800.1  779.71  4830.1  780.04  4840.1  778.95
  4857.7  778.29  4860.1  778.12  4870.1  775.60  4890.1  772.79  4990.1  772.94
  5007.5  771.87  5007.7  771.37  5011.2  771.37  5011.5  771.87  5032.4  772.49
  5039.1  775.41  5044.5  774.86  5063.3  776.20  5068.7  775.59  5075.4  776.44
  5094.3  777.49  5117.2  778.86  5146.8  779.79  5152.2  779.44  5161.6  779.69
  5200.7  781.57  5230.3  781.94  5247.8  782.75  5254.5  783.64  5269.3  784.19
#Mann=5,-1,0
  4650.1    0.05       0  4857.7    0.12       0  5007.5    0.07       0
  5011.5    0.12       0  5094.3    0.05       0
Bank Sta=5007.5,5011.5
Exp/Cntr=0.3,0.1

Type RM Length L Ch R = 1,9312,337,337,337
BEGIN DESCRIPTION:
Unnamed Tributary to Walnut Creek 2A 22.0
END DESCRIPTION:
XS GIS Cut Line= 3
      2314229.00      7050460.00      2314379.00      7050260.00
      2314329.00      7050160.00
#Sta/Elev= 30
  4743.0  778.34  4746.1  778.34  4750.3  777.64  4756.5  777.30  4808.2  776.28
  4832.8  775.41  4850.3  774.96  4856.5  775.13  4879.5  774.43  4893.0  774.37
  4906.5  772.99  4921.1  771.98  4935.7  770.28  4943.0  770.07  4964.9  770.96
  4979.5  770.74  4987.9  767.64  4988.1  767.14  4991.6  767.14  4991.9  767.64
  5015.4  768.44  5020.9  769.46  5023.7  770.48  5029.3  769.61  5037.7  771.05
  5046.1  772.83  5052.0  772.76  5074.1  776.16  5082.4  776.85  5104.8  777.88
#Mann=6,-1,0
  4743.0    0.12       0  4808.2    0.05       0  4832.8    0.12       0
  4987.9    0.07       0  4991.9    0.12       0  5052.0    0.05       0
Bank Sta=4987.9,4991.9
Exp/Cntr=0.3,0.1

Type RM Length L Ch R = 1,8975,388,388,388
BEGIN DESCRIPTION:
Unnamed Tributary to Walnut Creek 2A 21.0
END DESCRIPTION:
XS GIS Cut Line= 3
      2314378.98      7050660.02      2314679.00      7050360.00
      2314479.00      7050010.01
#Sta/Elev= 30
  4569.1  779.93  4758.5  775.59  4788.0  773.95  4809.5  772.23  4860.0  770.86
  4894.4  769.34  4965.1  767.86  5022.9  769.96  5081.9  770.19  5087.7  769.58
  5103.5  770.39  5109.3  768.79  5119.4  769.12  5123.1  767.19  5123.4  766.69
  5127.1  767.19  5131.6  768.52  5162.6  768.07  5168.3  768.86  5177.7  767.63
  5184.2  770.27  5189.9  770.07  5200.0  772.81  5205.7  772.30  5212.2  774.01
  5221.6  775.06  5280.6  776.35  5292.8  775.87  5356.6  778.55  5396.5  779.80
#Mann=7,-1,0
  4569.1    0.05       0  4758.5    0.12       0  4788.0    0.05       0
  4860.0    0.12       0  5123.1    0.07       0  5127.1    0.12       0
  5356.6    0.05       0
Bank Sta=5123.1,5127.1
Exp/Cntr=0.3,0.1

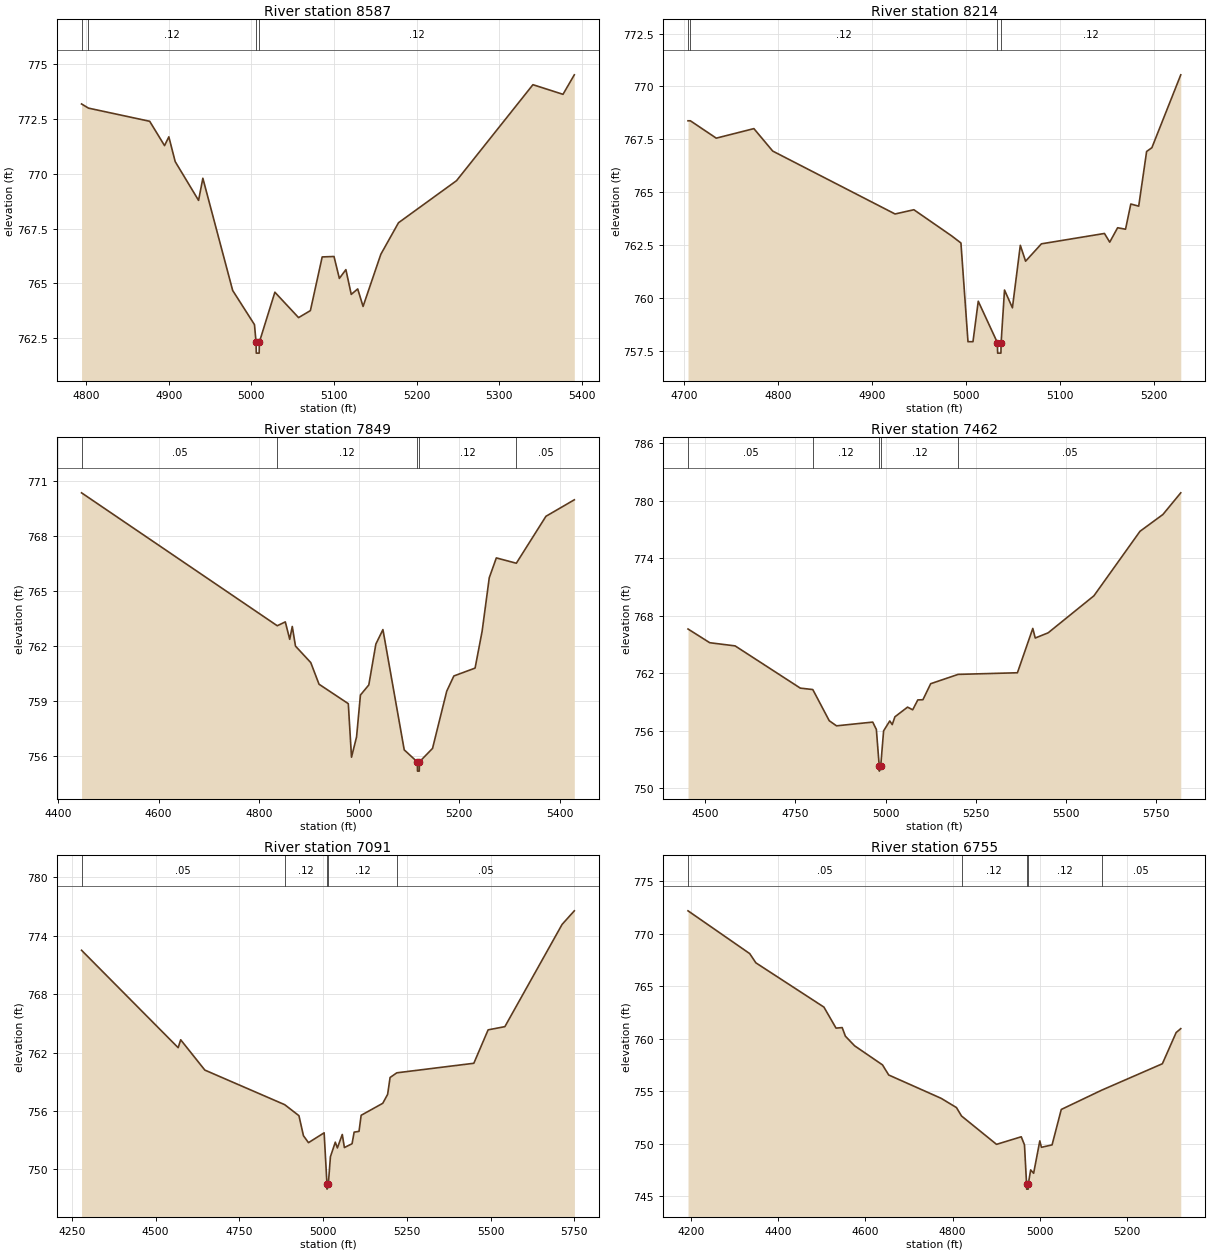
Type RM Length L Ch R = 1,8587,373,373,373
BEGIN DESCRIPTION:
Unnamed Tributary to Walnut Creek 2A 20.0
END DESCRIPTION:
XS GIS Cut Line= 3
      2314979.00      7050560.00      2315029.00      7050360.00
      2314728.98      7050109.98
#Sta/Elev= 30
  4794.3  773.19  4802.7  773.00  4876.8  772.40  4894.8  771.29  4900.0  771.69
  4907.7  770.56  4936.0  768.79  4941.2  769.80  4977.3  764.68  5003.7  763.12
  5005.6  762.32  5005.9  761.82  5009.4  761.82  5009.6  762.32  5028.4  764.60
  5057.1  763.44  5071.4  763.76  5085.7  766.21  5100.0  766.23  5106.5  765.23
  5114.4  765.63  5120.9  764.50  5128.7  764.75  5135.2  763.95  5156.7  766.33
  5178.1  767.77  5248.4  769.69  5340.9  774.07  5377.3  773.63  5391.0  774.52
#Mann=4,-1,0
  4794.3    0.05       0  4802.7    0.12       0  5005.6    0.07       0
  5009.6    0.12       0
Bank Sta=5005.6,5009.6
Exp/Cntr=0.3,0.1

Type RM Length L Ch R = 1,8214,365,365,365
BEGIN DESCRIPTION:
Unnamed Tributary to Walnut Creek 2A 19.0
END DESCRIPTION:
XS GIS Cut Line= 3
      2315229.00      7050410.00      2315229.00      7050110.00
      2315129.00      7049910.00
#Sta/Elev= 30
  4704.5  768.38  4707.0  768.38  4734.5  767.56  4774.5  768.01  4794.5  766.95
  4924.5  763.98  4944.5  764.18  4984.5  762.95  4994.5  762.61  5002.0  757.95
  5007.3  757.95  5012.9  759.86  5033.2  757.91  5033.5  757.41  5037.0  757.41
  5037.2  757.91  5040.8  760.39  5049.2  759.55  5057.6  762.50  5063.2  761.75
  5080.0  762.57  5147.0  763.06  5152.6  762.65  5161.0  763.33  5169.4  763.26
  5175.0  764.45  5183.4  764.35  5191.8  766.93  5197.4  767.11  5228.1  770.55
#Mann=4,-1,0
  4704.5    0.05       0  4707.0    0.12       0  5033.2    0.07       0
  5037.2    0.12       0
Bank Sta=5033.2,5037.2
Exp/Cntr=0.3,0.1

Type RM Length L Ch R = 1,7849,387,387,387
BEGIN DESCRIPTION:
Unnamed Tributary to Walnut Creek 2A 18.0
END DESCRIPTION:
XS GIS Cut Line= 3
      2315479.00      7050609.99      2315579.00      7050060.00
      2315278.98      7049759.98
#Sta/Elev= 30
  4446.2  770.35  4836.7  763.10  4852.8  763.31  4861.6  762.36  4866.7  763.06
  4873.1  761.99  4903.6  761.09  4920.1  759.91  4978.5  758.85  4984.9  755.93
  4995.0  757.04  5002.7  759.32  5019.4  759.87  5033.5  762.10  5047.6  762.89
  5090.1  756.33  5116.3  755.67  5116.6  755.17  5120.1  755.17  5120.3  755.67
  5146.6  756.41  5174.9  759.53  5189.1  760.36  5231.5  760.79  5245.6  762.81
  5259.8  765.72  5273.9  766.80  5313.8  766.51  5372.9  769.07  5429.5  769.97
#Mann=5,-1,0
  4446.2    0.05       0  4836.7    0.12       0  5116.3    0.07       0
  5120.3    0.12       0  5313.8    0.05       0
Bank Sta=5116.3,5120.3
Exp/Cntr=0.3,0.1

Type RM Length L Ch R = 1,7462,371,371,371
BEGIN DESCRIPTION:
Unnamed Tributary to Walnut Creek 2A 17.0
END DESCRIPTION:
XS GIS Cut Line= 3
      2315879.00      7050410.03      2315829.00      7049860.00
      2315279.02      7049260.03
#Sta/Elev= 30
  4452.2  766.62  4512.5  765.19  4582.8  764.86  4763.5  760.46  4798.2  760.31
  4843.8  757.06  4863.9  756.53  4964.3  756.92  4974.4  756.15  4982.4  752.31
  4982.7  751.81  4986.4  752.31  4994.5  756.01  5011.6  757.04  5018.4  756.66
  5025.8  757.47  5060.9  758.48  5075.1  758.20  5089.3  759.23  5103.5  759.25
  5125.0  760.92  5201.1  761.89  5365.5  762.06  5408.1  766.68  5414.9  765.68
  5450.6  766.22  5577.6  770.08  5705.3  776.80  5768.8  778.55  5818.4  780.81
#Mann=5,-1,0
  4452.2    0.05       0  4798.2    0.12       0  4982.4    0.07       0
  4986.4    0.12       0  5201.1    0.05       0
Bank Sta=4982.4,4986.4
Exp/Cntr=0.3,0.1

Type RM Length L Ch R = 1,7091,336,336,336
BEGIN DESCRIPTION:
Unnamed Tributary to Walnut Creek 2A 16.0
END DESCRIPTION:
XS GIS Cut Line= 3
      2316679.00      7050110.00      2316079.00      7049710.00
      2315479.01      7049260.01
#Sta/Elev= 30
  4278.9  772.50  4567.3  762.50  4574.9  763.31  4647.0  760.20  4885.4  756.65
  4927.9  755.52  4941.4  753.46  4956.4  752.75  5003.1  753.76  5011.6  748.48
  5011.8  747.98  5015.6  748.48  5021.9  751.31  5036.5  752.80  5042.7  752.21
  5057.3  753.59  5063.6  752.25  5086.5  752.64  5092.7  753.83  5107.3  753.91
  5113.6  755.56  5178.1  756.79  5192.7  757.71  5200.0  759.44  5220.1  759.92
  5450.0  760.90  5492.7  764.33  5542.7  764.66  5713.6  775.16  5750.0  776.55
#Mann=5,-1,0
  4278.9    0.05       0  4885.4    0.12       0  5011.6    0.07       0
  5015.6    0.12       0  5220.1    0.05       0
Bank Sta=5011.6,5015.6
Exp/Cntr=0.3,0.1

Type RM Length L Ch R = 1,6755,352,352,352
BEGIN DESCRIPTION:
Unnamed Tributary to Walnut Creek 2A 15.0
END DESCRIPTION:
XS GIS Cut Line= 3
      2316779.00      7049960.00      2316179.00      7049410.00
      2315878.97      7049510.01
#Sta/Elev= 30
  4193.2  772.17  4334.7  768.10  4348.9  767.22  4504.9  763.01  4532.7  761.01
  4546.8  761.06  4554.2  760.24  4575.2  759.33  4639.3  757.51  4653.5  756.55
  4773.8  754.33  4808.9  753.45  4820.5  752.65  4900.8  749.95  4957.5  750.67
  4964.9  749.90  4969.7  746.19  4969.9  745.69  4973.4  745.69  4973.7  746.19
  4979.1  747.52  4985.9  747.20  5000.1  750.28  5003.8  749.67  5028.2  749.90
  5049.3  753.27  5141.7  755.10  5281.2  757.62  5312.8  760.59  5323.4  760.96
#Mann=5,-1,0
  4193.2    0.05       0  4820.5    0.12       0  4969.7    0.07       0
  4973.7    0.12       0  5141.7    0.05       0
Bank Sta=4969.7,4973.7
Exp/Cntr=0.3,0.1

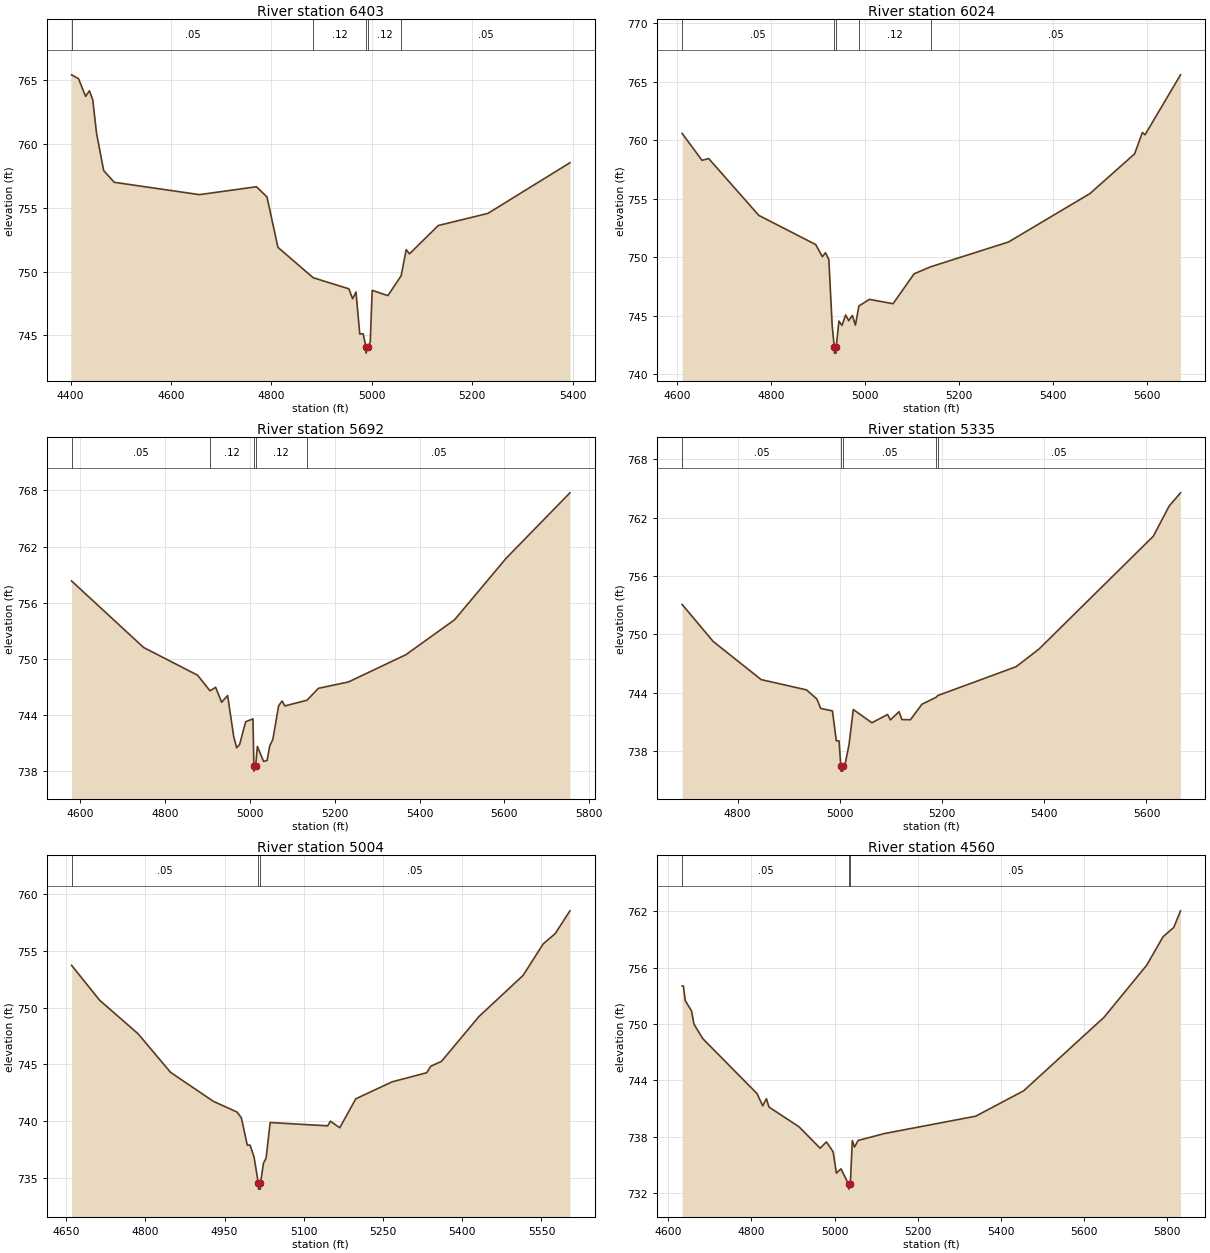
Type RM Length L Ch R = 1,6403,379,379,379
BEGIN DESCRIPTION:
Unnamed Tributary to Walnut Creek 2A 14.0
END DESCRIPTION:
XS GIS Cut Line= 3
      2316728.98      7049609.98      2316279.00      7049210.00
      2315978.97      7048959.98
#Sta/Elev= 30
  4402.0  765.42  4415.8  765.12  4430.0  763.73  4437.5  764.17  4444.2  763.46
  4451.7  760.85  4465.9  757.92  4486.8  757.00  4656.6  756.03  4770.3  756.65
  4791.2  755.85  4813.0  751.90  4883.2  749.52  4954.3  748.65  4961.8  747.87
  4968.5  748.40  4976.0  745.11  4982.7  745.13  4988.3  744.11  4988.5  743.61
  4992.3  744.11  4996.9  744.48  5000.7  748.53  5032.0  748.12  5058.4  749.67
  5068.5  751.72  5075.0  751.39  5132.3  753.61  5231.2  754.56  5394.6  758.53
#Mann=5,-1,0
  4402.0    0.05       0  4883.2    0.12       0  4988.3    0.07       0
  4992.3    0.12       0  5058.4    0.05       0
Bank Sta=4988.3,4992.3
Exp/Cntr=0.3,0.1

Type RM Length L Ch R = 1,6024,332,332,332
BEGIN DESCRIPTION:
Unnamed Tributary to Walnut Creek 2A 13.0
END DESCRIPTION:
XS GIS Cut Line= 3
      2316828.97      7049259.98      2316529.00      7049010.00
      2315929.00      7048710.00
#Sta/Elev= 30
  4610.1  760.58  4652.4  758.28  4666.7  758.43  4773.4  753.58  4894.5  751.09
  4908.8  750.05  4915.3  750.39  4922.5  749.82  4929.6  744.19  4934.1  742.32
  4934.4  741.82  4937.9  741.82  4938.1  742.32  4944.0  744.56  4950.5  744.18
  4958.3  745.08  4964.8  744.59  4972.6  745.04  4979.1  744.21  4986.5  745.85
  5009.0  746.41  5059.3  746.04  5104.0  748.59  5139.2  749.19  5305.2  751.31
  5478.5  755.44  5573.6  758.83  5590.3  760.66  5595.9  760.46  5671.4  765.58
#Mann=5,-1,0
  4610.1    0.05       0  4934.1    0.07       0  4938.1    0.05       0
  4986.5    0.12       0  5139.2    0.05       0
Bank Sta=4934.1,4938.1
Exp/Cntr=0.3,0.1

Type RM Length L Ch R = 1,5692,357,357,357
BEGIN DESCRIPTION:
Unnamed Tributary to Walnut Creek 2A 12.0
END DESCRIPTION:
XS GIS Cut Line= 3
      2316928.97      7049059.97      2316629.00      7048760.00
      2316029.02      7048310.02
#Sta/Elev= 30
  4580.2  758.32  4749.9  751.22  4877.1  748.26  4906.5  746.59  4919.6  746.97
  4933.7  745.37  4947.9  746.09  4962.0  741.77  4969.1  740.51  4976.1  740.86
  4990.3  743.29  5007.6  743.60  5009.7  738.52  5010.0  738.02  5013.7  738.52
  5018.0  740.66  5032.6  739.06  5040.9  739.16  5047.1  740.71  5054.4  741.40
  5068.0  744.99  5076.3  745.51  5082.6  744.98  5134.9  745.59  5161.7  746.86
  5232.6  747.54  5368.0  750.45  5482.6  754.18  5604.4  760.76  5754.4  767.73
#Mann=5,-1,0
  4580.2    0.05       0  4906.5    0.12       0  5009.7    0.07       0
  5013.7    0.12       0  5134.9    0.05       0
Bank Sta=5009.7,5013.7
Exp/Cntr=0.3,0.1

Type RM Length L Ch R = 1,5335,331,331,331
BEGIN DESCRIPTION:
Unnamed Tributary to Walnut Creek 2A 11.0
END DESCRIPTION:
XS GIS Cut Line= 3
      2317078.96      7048509.99      2316779.00      7048460.00
      2316179.02      7048160.01
#Sta/Elev= 30
  4691.7  753.07  4752.5  749.26  4846.3  745.34  4935.0  744.28  4955.2  743.35
  4962.8  742.37  4985.7  742.12  4993.3  739.04  4998.6  739.04  5002.2  736.42
  5002.4  735.92  5005.9  735.92  5006.2  736.42  5009.8  736.44  5018.2  738.67
  5026.5  742.26  5062.9  740.90  5093.6  741.75  5099.2  741.19  5116.0  742.04
  5121.6  741.23  5138.3  741.21  5160.7  742.80  5189.0  743.53  5191.4  743.69
  5345.2  746.67  5389.9  748.49  5613.5  760.10  5644.3  763.19  5666.6  764.56
#Mann=5,-1,0
  4691.7    0.05       0  5002.2   0.033       0  5006.2    0.05       0
  5189.0    0.12       0  5191.4    0.05       0
Bank Sta=5002.2,5006.2
Exp/Cntr=0.3,0.1

Type RM Length L Ch R = 1,5004,444,444,444
BEGIN DESCRIPTION:
Unnamed Tributary to Walnut Creek 2A 10.0
END DESCRIPTION:
XS GIS Cut Line= 3
      2317179.03      7048310.02      2316879.00      7048160.00
      2316279.02      7048060.00
#Sta/Elev= 30
  4660.2  753.73  4713.3  750.65  4786.0  747.70  4847.5  744.30  4928.6  741.74
  4973.3  740.80  4981.7  740.29  4992.9  737.88  4998.2  737.88  5005.8  736.82
  5013.9  734.50  5014.2  734.00  5017.7  734.00  5017.9  734.50  5023.5  736.28
  5028.6  736.74  5036.2  739.87  5145.2  739.58  5150.3  739.99  5168.0  739.41
  5198.4  741.96  5266.8  743.45  5332.7  744.26  5340.3  744.83  5360.6  745.26
  5431.6  749.21  5515.2  752.84  5553.2  755.61  5576.0  756.52  5603.9  758.53
#Mann=3,-1,0
  4660.2    0.05       0  5013.9   0.033       0  5017.9    0.05       0
Bank Sta=5013.9,5017.9
Exp/Cntr=0.3,0.1

Type RM Length L Ch R = 1,4560,421,421,421
BEGIN DESCRIPTION:
Unnamed Tributary to Walnut Creek 2A 9.0
END DESCRIPTION:
XS GIS Cut Line= 3
      2317329.00      7047960.00      2317029.00      7047760.00
      2316229.01      7048010.00
#Sta/Elev= 30
  4633.2  754.05  4636.2  754.05  4640.7  752.49  4655.7  751.40  4661.7  749.98
  4682.8  748.45  4813.5  742.59  4827.0  741.30  4836.0  742.06  4842.0  741.17
  4914.1  739.08  4965.2  736.79  4980.2  737.47  4996.4  736.41  5004.2  734.14
  5015.2  734.60  5033.7  732.94  5033.9  732.44  5037.7  732.94  5042.5  737.61
  5047.7  736.91  5056.6  737.62  5119.5  738.35  5339.5  740.20  5454.7  742.90
  5648.0  750.72  5750.7  756.26  5790.0  759.29  5815.7  760.27  5831.9  762.04
#Mann=3,-1,0
  4633.2    0.05       0  5033.7   0.033       0  5037.7    0.05       0
Bank Sta=5033.7,5037.7
Exp/Cntr=0.3,0.1

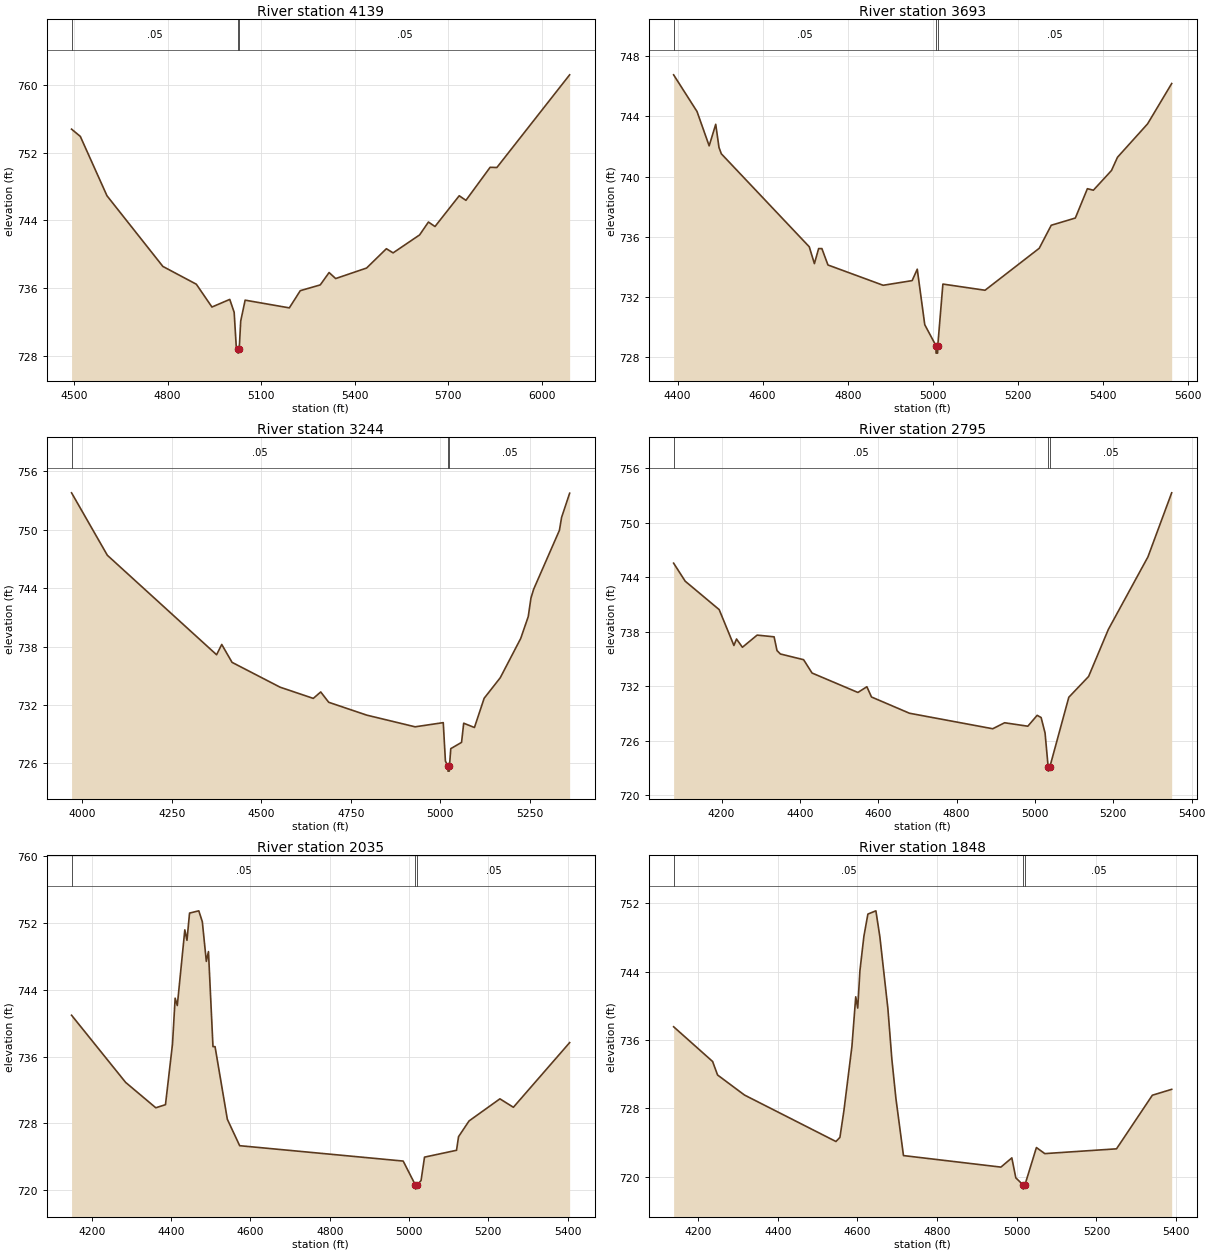
Type RM Length L Ch R = 1,4139,446,446,446
BEGIN DESCRIPTION:
Unnamed Tributary to Walnut Creek 2A 8.0
END DESCRIPTION:
XS GIS Cut Line= 3
      2317478.99      7047809.99      2317179.00      7047410.00
      2316428.98      7046609.98
#Sta/Elev= 30
  4492.1  754.77  4520.2  753.91  4605.6  746.91  4784.8  738.57  4892.1  736.47
  4942.1  733.78  4999.2  734.68  5013.3  733.16  5020.2  729.00  5025.3  728.84
  5025.7  728.34  5029.6  728.84  5034.3  732.12  5048.5  734.59  5190.2  733.68
  5225.3  735.71  5289.3  736.39  5317.6  737.85  5338.7  737.14  5437.8  738.38
  5501.3  740.66  5522.8  740.17  5607.8  742.29  5636.1  743.81  5657.1  743.28
  5734.8  746.91  5756.3  746.37  5833.9  750.27  5855.4  750.24  6088.7  761.18
#Mann=3,-1,0
  4492.1    0.05       0  5025.3   0.033       0  5029.6    0.05       0
Bank Sta=5025.3,5029.6
Exp/Cntr=0.3,0.1

Type RM Length L Ch R = 1,3693,449,449,449
BEGIN DESCRIPTION:
Unnamed Tributary to Walnut Creek 2A 7.0
END DESCRIPTION:
XS GIS Cut Line= 3
      2317579.02      7047560.04      2317329.00      7047010.00
      2316928.99      7046609.99
#Sta/Elev= 30
  4390.8  746.77  4445.8  744.33  4474.3  742.05  4489.7  743.48  4497.4  741.94
  4502.9  741.52  4709.4  735.34  4721.5  734.22  4731.4  735.22  4739.1  735.22
  4753.3  734.13  4883.0  732.78  4951.1  733.09  4963.1  733.85  4980.7  730.16
  5006.9  728.77  5007.3  728.27  5010.9  728.27  5011.3  728.77  5023.3  732.86
  5122.3  732.45  5249.6  735.24  5277.8  736.77  5334.4  737.25  5362.7  739.20
  5376.8  739.10  5419.3  740.41  5433.4  741.29  5504.1  743.51  5560.7  746.19
#Mann=3,-1,0
  4390.8    0.05       0  5006.9   0.033       0  5011.3    0.05       0
Bank Sta=5006.9,5011.3
Exp/Cntr=0.3,0.1

Type RM Length L Ch R = 1,3244,449,449,449
BEGIN DESCRIPTION:
Unnamed Tributary to Walnut Creek 2A 6.0
END DESCRIPTION:
XS GIS Cut Line= 3
      2318129.01      7047410.01      2317479.00      7046610.00
      2317279.02      7046310.04
#Sta/Elev= 30
  3969.9  753.79  4069.8  747.38  4375.0  737.16  4389.4  738.22  4418.2  736.38
  4552.4  733.83  4645.1  732.68  4665.9  733.34  4688.2  732.28  4794.5  730.96
  4929.6  729.76  5008.2  730.19  5014.2  726.25  5021.0  725.71  5021.4  725.21
  5025.0  725.21  5025.5  725.71  5029.2  727.52  5059.3  728.16  5065.3  730.13
  5095.3  729.69  5122.4  732.69  5167.4  734.80  5224.5  738.83  5245.6  741.08
  5253.1  742.97  5260.6  743.88  5332.7  749.94  5338.7  751.26  5361.2  753.75
#Mann=3,-1,0
  3969.9    0.05       0  5021.0   0.033       0  5025.5    0.05       0
Bank Sta=5021,5025.5
Exp/Cntr=0.3,0.1

Type RM Length L Ch R = 1,2795,760,760,760
BEGIN DESCRIPTION:
Unnamed Tributary to Walnut Creek 2A 5.0
END DESCRIPTION:
XS GIS Cut Line= 3
      2318478.99      7046709.99      2317679.00      7046260.00
      2317329.02      7046210.00
#Sta/Elev= 30
  4077.6  745.56  4107.2  743.57  4193.9  740.44  4231.5  736.49  4238.2  737.20
  4253.2  736.29  4290.8  737.63  4334.1  737.44  4341.5  735.93  4350.1  735.55
  4409.4  734.92  4431.0  733.45  4548.0  731.31  4570.9  731.94  4582.7  730.81
  4679.6  729.02  4892.2  727.31  4922.5  727.97  4981.8  727.59  5005.6  728.79
  5015.7  728.55  5025.8  726.84  5033.6  723.14  5034.1  722.64  5038.2  723.14
  5086.4  730.78  5136.9  733.07  5187.4  738.26  5288.4  746.25  5349.0  753.31
#Mann=3,-1,0
  4077.6    0.05       0  5033.6    0.04       0  5038.2    0.05       0
Bank Sta=5033.6,5038.2
Exp/Cntr=0.3,0.1

Type RM Length L Ch R = 1,2035,187,187,187
BEGIN DESCRIPTION:
Unnamed Tributary to Walnut Creek 2A 4.0
END DESCRIPTION:
XS GIS Cut Line= 4
      2318825.88      7045881.04      2318493.99      7045750.57
      2317966.41      7045608.43      2317619.75      7045542.40
#Sta/Elev= 30
  4149.1  740.95  4285.4  732.91  4361.5  729.87  4385.9  730.24  4403.6  737.50
  4410.3  742.99  4415.7  742.11  4434.7  751.17  4440.1  749.92  4446.6  753.18
  4469.9  753.45  4478.8  752.15  4488.9  747.40  4494.3  748.57  4505.7  737.19
  4510.9  737.19  4541.9  728.49  4573.0  725.33  4985.3  723.49  5016.0  720.63
  5016.5  720.13  5020.8  720.63  5030.4  721.17  5039.1  723.96  5119.8  724.78
  5124.9  726.41  5151.3  728.29  5229.2  730.94  5263.2  729.93  5405.0  737.67
#Mann=3,-1,0
  4149.1    0.05       0  5016.0    0.04       0  5020.8    0.05       0
Bank Sta=5016,5020.8
Exp/Cntr=0.3,0.1

Type RM Length L Ch R = 1,1848,959,959,959
BEGIN DESCRIPTION:
Unnamed Tributary to Walnut Creek 2A 3.0
END DESCRIPTION:
XS GIS Cut Line= 4
      2318936.95      7045681.52      2318587.48      7045511.12
      2318109.48      7045470.86      2317742.36      7045366.75
#Sta/Elev= 30
  4138.7  737.56  4236.6  733.49  4249.0  731.91  4316.6  729.56  4546.1  724.12
  4556.1  724.60  4566.1  727.72  4586.2  735.25  4595.8  741.07  4600.8  739.75
  4606.3  744.12  4616.3  748.16  4626.3  750.76  4646.4  751.14  4656.4  748.09
  4676.5  739.69  4686.5  733.74  4696.6  729.18  4715.6  722.47  4960.2  721.12
  4987.6  722.20  4997.6  719.86  5015.7  719.04  5016.2  718.54  5020.5  719.04
  5049.3  723.41  5070.3  722.70  5250.3  723.26  5340.3  729.54  5388.8  730.23
#Mann=3,-1,0
  4138.7    0.05       0  5015.7    0.04       0  5020.5    0.05       0
Bank Sta=5015.7,5020.5
Exp/Cntr=0.3,0.1

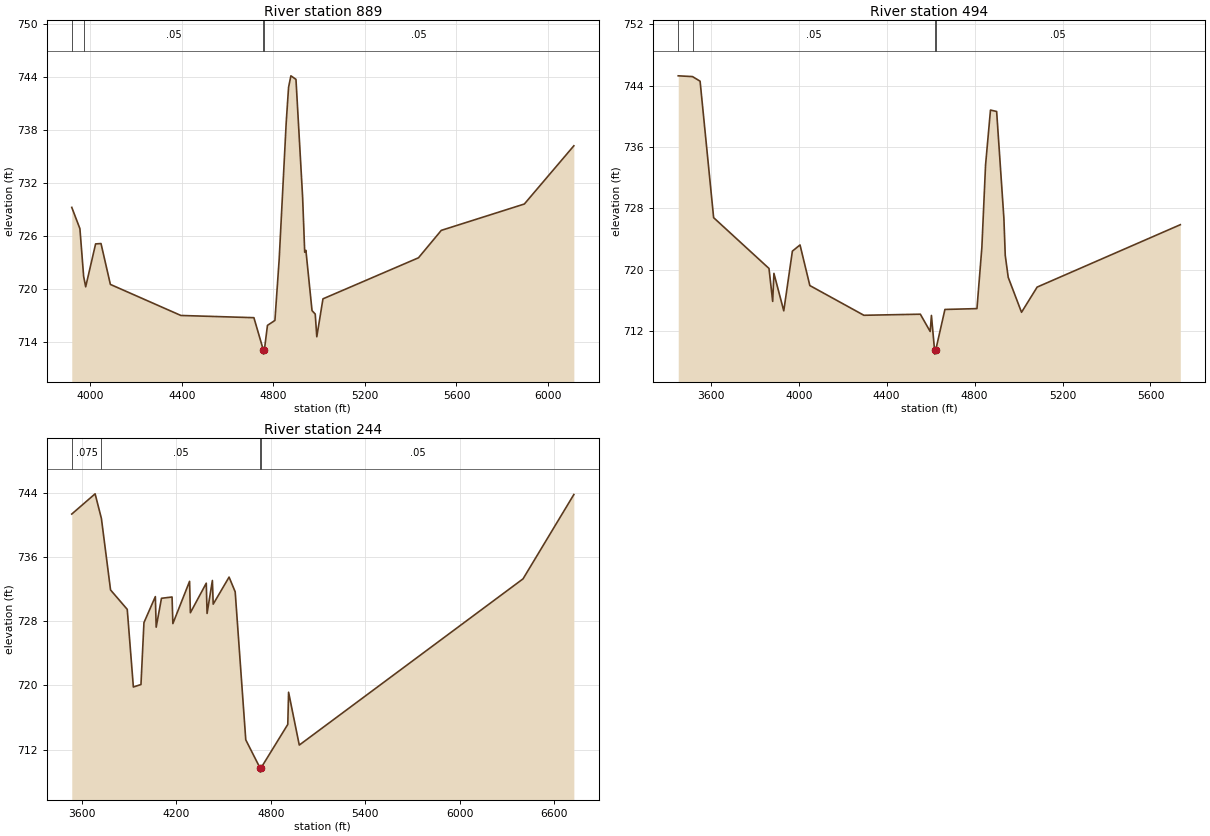
Type RM Length L Ch R = 1,889,395,395,395
BEGIN DESCRIPTION:
Unnamed Tributary to Walnut Creek 2A 2.0
END DESCRIPTION:
XS GIS Cut Line= 4
      2319333.74      7044838.17      2318316.96      7044610.71
      2318170.69      7044568.83      2317628.98      7045410.04
#Sta/Elev= 30
  3918.6  729.25  3954.2  726.84  3970.6  721.43  3979.4  720.27  4022.8  725.12
  4046.4  725.16  4087.4  720.54  4395.6  717.03  4714.7  716.78  4755.6  713.16
  4756.3  712.66  4760.6  713.16  4774.0  715.91  4806.6  716.47  4825.2  723.38
  4855.9  738.83  4866.2  742.81  4876.4  744.12  4898.6  743.72  4927.7  730.39
  4936.8  724.18  4942.0  724.39  4968.8  717.58  4982.8  717.19  4989.6  714.62
  5016.6  718.91  5434.1  723.55  5533.8  726.65  5896.9  729.63  6113.2  736.21
#Mann=4,-1,0
  3918.6   0.075       0  3970.6    0.05       0  4755.6   0.033       0
  4760.6    0.05       0
Bank Sta=4755.6,4760.6
Exp/Cntr=0.3,0.1

Type RM Length L Ch R = 1,494,250,250,250
BEGIN DESCRIPTION:
Unnamed Tributary to Walnut Creek 2A 1.5
END DESCRIPTION:
XS GIS Cut Line= 4
      2319704.83      7044858.39      2318358.73      7044187.96
      2318191.12      7044376.52      2317914.37      7044825.58
#Sta/Elev= 30
  3452.1  745.29  3517.0  745.19  3551.5  744.59  3613.1  726.78  3864.9  720.15
  3881.7  715.85  3887.3  719.51  3932.1  714.62  3971.3  722.41  4006.0  723.22
  4050.7  717.92  4296.5  714.04  4553.3  714.18  4598.1  711.92  4603.7  714.02
  4618.0  709.47  4618.6  708.97  4623.0  709.47  4665.1  714.80  4810.8  714.91
  4833.1  722.89  4849.9  733.65  4872.3  740.82  4900.3  740.64  4933.3  726.70
  4939.5  721.84  4953.0  718.99  5013.5  714.43  5084.6  717.72  5735.7  725.86
#Mann=4,-1,0
  3452.1     0.1       0  3517.0    0.05       0  4618.0   0.033       0
  4623.0    0.05       0
Bank Sta=4618,4623
Exp/Cntr=0.3,0.1

Type RM Length L Ch R = 1,244,0,0,0
BEGIN DESCRIPTION:
Unnamed Tributary to Walnut Creek 2A 1.0
END DESCRIPTION:
XS GIS Cut Line= 4
      2319741.51      7044303.19      2318489.67      7043941.78
      2318300.70      7043976.49      2317478.99      7045460.02
#Sta/Elev= 30
  3534.8  741.34  3683.1  743.86  3723.2  740.79  3781.3  731.89  3887.4  729.47
  3926.3  719.80  3974.6  720.11  3993.6  727.82  4066.0  731.06  4071.3  727.25
  4104.9  730.85  4172.2  731.01  4177.4  727.70  4283.5  732.96  4288.7  729.05
  4389.6  732.73  4394.8  728.96  4428.5  733.07  4433.7  730.12  4534.6  733.49
  4573.4  731.66  4640.7  713.22  4731.9  709.70  4732.5  709.20  4736.9  709.70
  4907.7  715.14  4912.8  719.15  4980.8  712.57  6402.9  733.27  6725.8  743.77
#Mann=4,-1,0
  3534.8   0.075       0  3723.2    0.05       0  4731.9   0.033       0
  4736.9    0.05       0
Bank Sta=4731.9,4736.9
Exp/Cntr=0.3,0.1

Chan Stop Cuts=-1