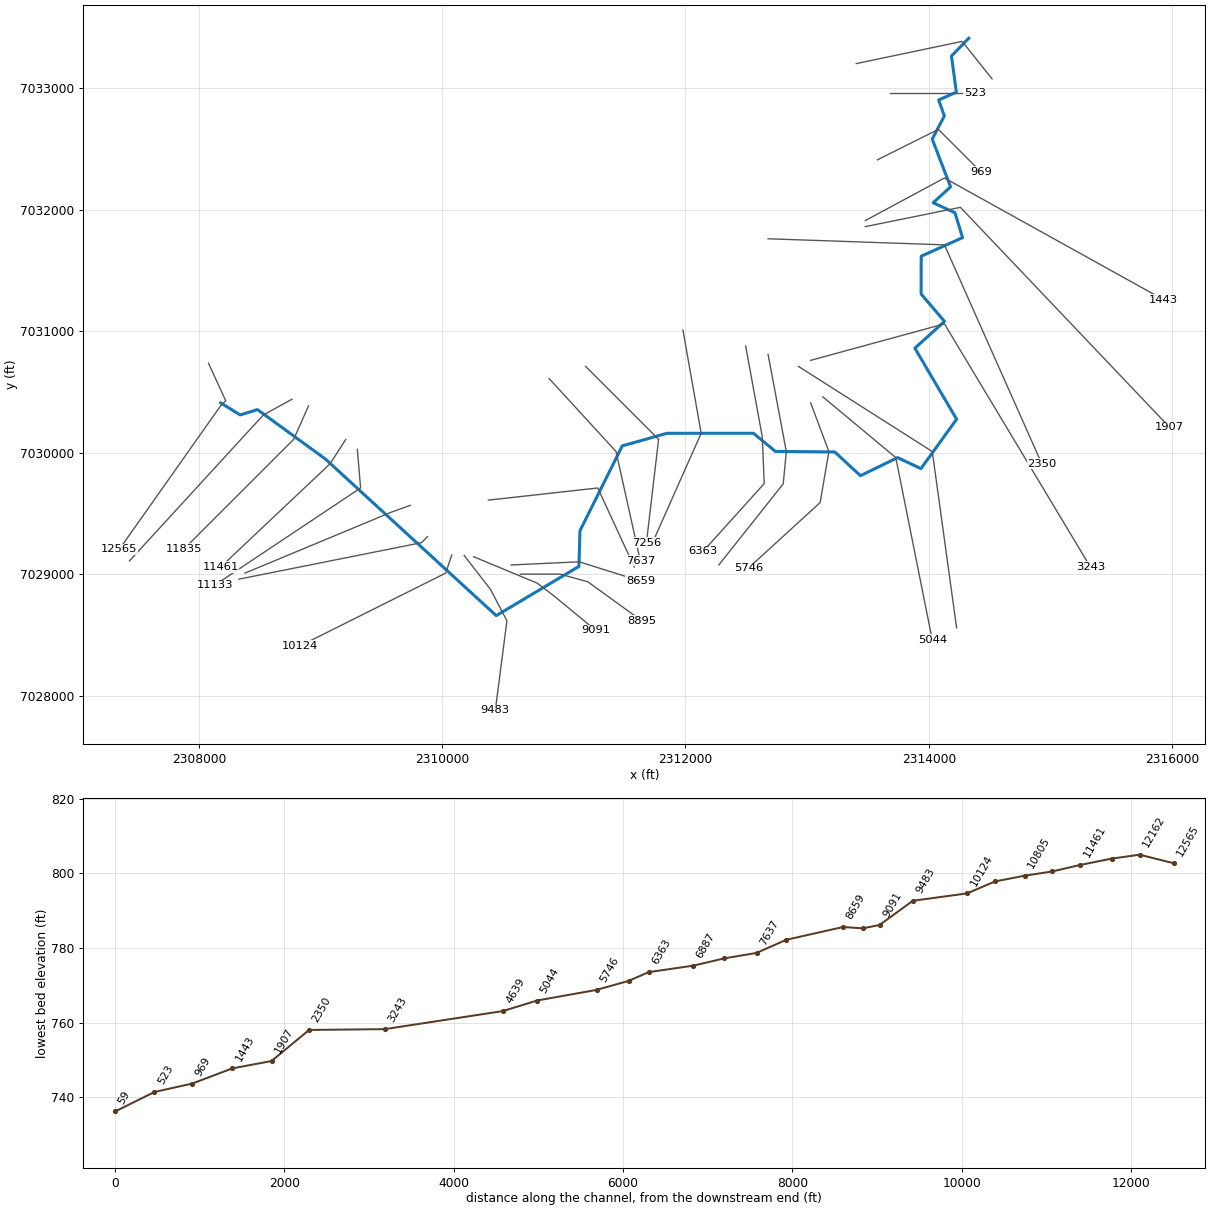
--- Unnamed Tr to Walnut Cr 2B.prj (project) ---

Proj Title=Unnamed Tr to Walnut Cr 2B Base Level Engineering
Current Plan=p01
Default Exp/Contr=0.3,0.1
English Units
Geom File=g01
Flow File=f01
Plan File=p01
BEGIN DESCRIPTION:
Unnamed Tr to Walnut Cr 2B
END DESCRIPTION:

--- Unnamed Tr to Walnut Cr 2B.p01 (plan) ---

Plan Title=Multiple Run
Short Identifier=Multiple
Geom File=g01
Flow File=f01
Subcritical Flow
K Sum by GR= 0
Std Step Tol= 0.01
Critical Tol= 0.01
Num of Std Step Trials= 20
Max Error Tol= 0.3
Flow Tol Ratio= 0.001
Split Flow NTrial= 30
Split Flow Tol= 0.02
Split Flow Ratio= 0.02
Log Output Level= 0
Friction Slope Method= 1
Unsteady Friction Slope Method= 2
Unsteady Bridges Friction Slope Method= 1
Parabolic Critical Depth
Global Vel Dist=  1 , 1 , 1
Global Log Level= 0
CheckData=True
Encroach Param= -1, 0, 0, 0
BEGIN DESCRIPTION:
Multiple Run
END DESCRIPTION:

--- Unnamed Tr to Walnut Cr 2B.f01 (steady flow) ---

Flow Title=Multiple
Number of Profiles=7
Profile Names=10-year,25-year,50-year,1pct_min,100-year,1pct_plu,500-year
River Rch & RM= Unnamed Tr to Wa,Reach-1,12565
     363     475     563     331     660    1320     907
River Rch & RM= Unnamed Tr to Wa,Reach-1,12162
     377     494     586     345     688    1370     947
River Rch & RM= Unnamed Tr to Wa,Reach-1,9483
     493     658     790     470     938    1870    1320
River Rch & RM= Unnamed Tr to Wa,Reach-1,7987
     597     808     977     586    1170    2330    1670
River Rch & RM= Unnamed Tr to Wa,Reach-1,4639
     819    1130    1380     838    1670    3340    2450
Boundary for River Rch & Prof#=Unnamed Tr to Wa,Reach-1,1
Up Type=0
Dn Type=3
Dn Slope=0.005
Boundary for River Rch & Prof#=Unnamed Tr to Wa,Reach-1,2
Up Type=0
Dn Type=3
Dn Slope=0.005
Boundary for River Rch & Prof#=Unnamed Tr to Wa,Reach-1,3
Up Type=0
Dn Type=3
Dn Slope=0.005
Boundary for River Rch & Prof#=Unnamed Tr to Wa,Reach-1,4
Up Type=0
Dn Type=3
Dn Slope=0.005
Boundary for River Rch & Prof#=Unnamed Tr to Wa,Reach-1,5
Up Type=0
Dn Type=3
Dn Slope=0.005
Boundary for River Rch & Prof#=Unnamed Tr to Wa,Reach-1,6
Up Type=0
Dn Type=3
Dn Slope=0.005
Boundary for River Rch & Prof#=Unnamed Tr to Wa,Reach-1,7
Up Type=0
Dn Type=3
Dn Slope=0.005

--- Unnamed Tr to Walnut Cr 2B.g01 (geometry) ---

Geom Title=Existing Conditions

River Reach=Unnamed Tr to Wa,Reach-1
Reach XY= 30
      2308179.00      7030410.00      2308339.68      7030310.74
      2308481.30      7030354.91      2309038.68      7029949.22
      2310444.34      7028659.95      2311123.99      7029065.01
      2311132.75      7029358.45      2311480.48      7030056.39
      2311847.27      7030159.79      2312559.02      7030160.04
      2312738.59      7030011.20      2313227.50      7030006.38
      2313438.45      7029811.14      2313744.34      7029960.05
      2313935.75      7029869.10      2314229.10      7030275.65
      2313885.99      7030860.22      2314129.48      7031080.16
      2313936.79      7031306.58      2313938.12      7031616.76
      2314277.98      7031769.46      2314215.55      7031973.63
      2314036.39      7032056.57      2314179.50      7032187.08
      2314028.38      7032580.04      2314128.24      7032770.69
      2314081.66      7032902.14      2314227.03      7032965.65
      2314186.79      7033263.42      2314329.00      7033410.00

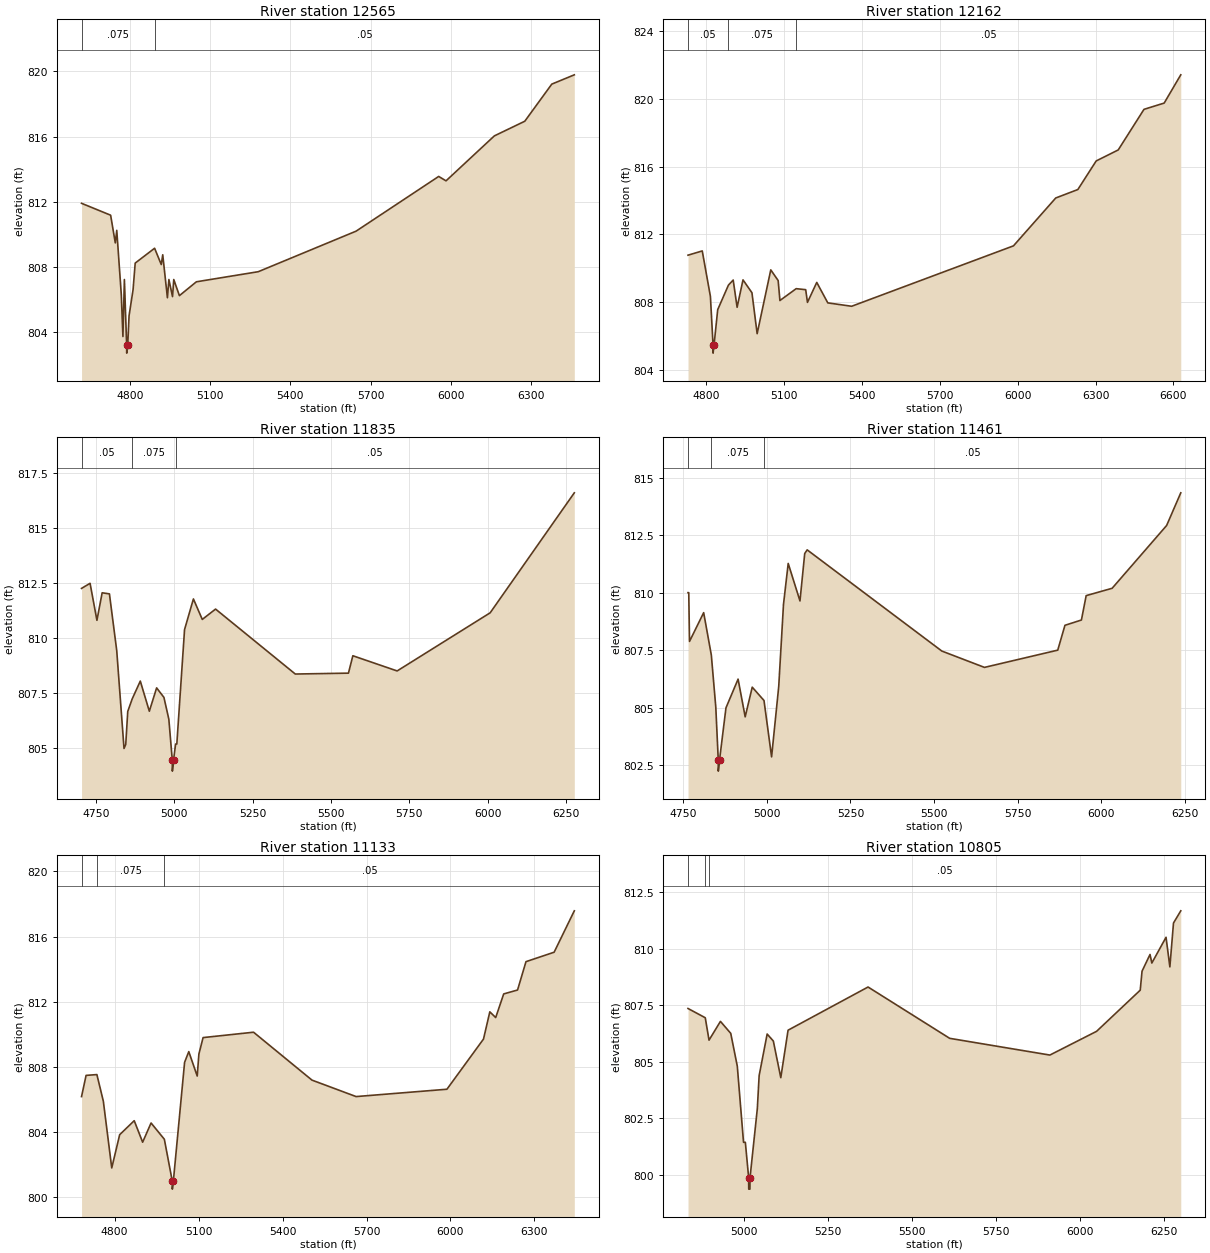
Type RM Length L Ch R = 1,12565,403,403,403
BEGIN DESCRIPTION:
Unnamed Tributary to Walnut Creek 2B 26.0
END DESCRIPTION:
XS GIS Cut Line= 4
      2308079.11      7030734.89      2308220.43      7030427.90
      2308174.91      7030381.19      2307345.89      7029205.83
#Sta/Elev= 30
  4619.7  811.90  4728.4  811.17  4745.8  809.47  4751.3  810.24  4768.2  806.30
  4774.3  803.72  4779.8  807.22  4788.2  803.20  4788.5  802.70  4792.2  803.20
  4797.3  805.00  4812.2  806.59  4820.2  808.23  4892.7  809.14  4917.6  808.14
  4923.1  808.74  4940.6  806.10  4946.1  807.22  4959.7  806.17  4964.3  807.22
  4985.4  806.23  5048.8  807.08  5280.0  807.70  5645.7  810.19  5954.4  813.55
  5981.8  813.28  6162.4  816.04  6276.1  816.94  6377.1  819.22  6461.2  819.79
#Mann=2,-1,0
  4619.7   0.075       0  4892.7    0.05       0
Bank Sta=4788.2,4792.2
Exp/Cntr=0.3,0.1

Type RM Length L Ch R = 1,12162,327,327,327
BEGIN DESCRIPTION:
Unnamed Tributary to Walnut Creek 2B 25.0
END DESCRIPTION:
XS GIS Cut Line= 3
      2308764.40      7030440.13      2308529.00      7030310.00
      2307428.97      7029109.97
#Sta/Elev= 30
  4731.3  810.77  4786.1  811.02  4817.5  808.33  4827.6  805.48  4827.8  804.98
  4831.6  805.48  4845.6  807.55  4886.9  809.00  4905.2  809.30  4920.3  807.69
  4943.0  809.31  4977.4  808.55  4997.4  806.13  5049.9  809.90  5078.3  809.27
  5085.1  808.09  5147.7  808.79  5184.3  808.73  5191.1  807.98  5226.9  809.16
  5269.4  807.95  5361.3  807.75  5984.1  811.32  6146.9  814.15  6232.0  814.65
  6302.6  816.34  6387.4  816.99  6486.6  819.39  6564.3  819.76  6628.2  821.43
#Mann=3,-1,0
  4731.3    0.05       0  4886.9   0.075       0  5147.7    0.05       0
Bank Sta=4827.6,4831.6
Exp/Cntr=0.3,0.1

Type RM Length L Ch R = 1,11835,374,374,374
BEGIN DESCRIPTION:
Unnamed Tributary to Walnut Creek 2B 24.0
END DESCRIPTION:
XS GIS Cut Line= 3
      2308900.74      7030384.87      2308779.00      7030110.00
      2307879.01      7029210.01
#Sta/Elev= 30
  4703.7  812.24  4730.9  812.47  4752.8  810.79  4769.5  812.04  4792.7  811.99
  4816.0  809.42  4839.3  804.97  4844.8  805.15  4851.2  806.65  4865.4  807.22
  4891.3  808.03  4920.1  806.66  4943.4  807.72  4966.7  807.29  4982.4  806.30
  4993.4  804.44  4993.7  803.94  4997.4  804.44  5004.0  805.17  5007.9  805.17
  5032.6  810.37  5060.9  811.76  5089.2  810.83  5131.6  811.30  5386.2  808.35
  5555.9  808.39  5570.0  809.18  5711.4  808.49  6008.4  811.13  6277.1  816.58
#Mann=3,-1,0
  4703.7    0.05       0  4865.4   0.075       0  5004.0    0.05       0
Bank Sta=4993.4,4997.4
Exp/Cntr=0.3,0.1

Type RM Length L Ch R = 1,11461,328,328,328
BEGIN DESCRIPTION:
Unnamed Tributary to Walnut Creek 2B 23.0
END DESCRIPTION:
XS GIS Cut Line= 3
      2309206.58      7030108.58      2309079.00      7029910.00
      2308178.98      7029059.98
#Sta/Elev= 30
  4764.2  810.00  4766.4  810.00  4768.7  807.88  4811.0  809.13  4833.9  807.29
  4847.3  805.02  4854.6  802.74  4854.8  802.24  4858.6  802.74  4877.7  804.99
  4914.0  806.24  4935.2  804.60  4956.3  805.89  4991.5  805.31  5014.2  802.86
  5035.6  805.93  5049.8  809.49  5063.9  811.27  5099.1  809.64  5113.3  811.70
  5120.6  811.86  5523.5  807.46  5651.0  806.75  5870.2  807.50  5891.7  808.58
  5941.0  808.81  5955.2  809.87  6032.9  810.19  6195.9  812.92  6238.2  814.34
#Mann=3,-1,0
  4764.2    0.05       0  4833.9   0.075       0  4991.5    0.05       0
Bank Sta=4854.6,4858.6
Exp/Cntr=0.3,0.1

Type RM Length L Ch R = 1,11133,328,328,328
BEGIN DESCRIPTION:
Unnamed Tributary to Walnut Creek 2B 22.0
END DESCRIPTION:
XS GIS Cut Line= 3
      2309302.34      7030027.51      2309329.00      7029710.00
      2308129.04      7028910.03
#Sta/Elev= 30
  4681.7  806.18  4697.9  807.48  4736.5  807.53  4759.5  805.90  4789.6  801.80
  4817.9  803.84  4869.9  804.70  4900.0  803.38  4930.1  804.56  4977.6  803.56
  5005.8  801.00  5006.1  800.50  5009.8  801.00  5049.9  808.28  5064.9  808.94
  5095.0  807.44  5101.0  808.79  5116.0  809.80  5296.3  810.13  5505.1  807.19
  5662.8  806.18  5987.3  806.63  6118.0  809.71  6140.6  811.38  6161.6  811.03
  6190.2  812.48  6239.7  812.72  6269.8  814.46  6370.4  815.04  6442.5  817.58
#Mann=3,-1,0
  4681.7    0.05       0  4736.5   0.075       0  4977.6    0.05       0
Bank Sta=5005.8,5009.8
Exp/Cntr=0.3,0.1

Type RM Length L Ch R = 1,10805,352,352,352
BEGIN DESCRIPTION:
Unnamed Tributary to Walnut Creek 2B 21.0
END DESCRIPTION:
XS GIS Cut Line= 3
      2309737.13      7029566.93      2309579.00      7029510.00
      2308378.97      7029009.99
#Sta/Elev= 30
  4832.2  807.35  4883.6  806.94  4894.8  805.95  4928.8  806.78  4959.5  806.25
  4979.0  804.80  4997.6  801.43  5003.0  801.43  5012.9  799.86  5013.1  799.36
  5016.6  799.36  5016.9  799.86  5038.7  802.92  5044.1  804.38  5068.0  806.22
  5086.4  805.91  5108.6  804.29  5130.3  806.39  5368.6  808.30  5611.8  806.03
  5910.3  805.29  6049.5  806.34  6179.5  808.16  6184.9  809.00  6208.7  809.74
  6214.1  809.36  6256.4  810.50  6267.8  809.19  6278.6  811.13  6300.3  811.67
#Mann=3,-1,0
  4832.2    0.05       0  4883.6   0.075       0  4894.8    0.05       0
Bank Sta=5012.9,5016.9
Exp/Cntr=0.3,0.1

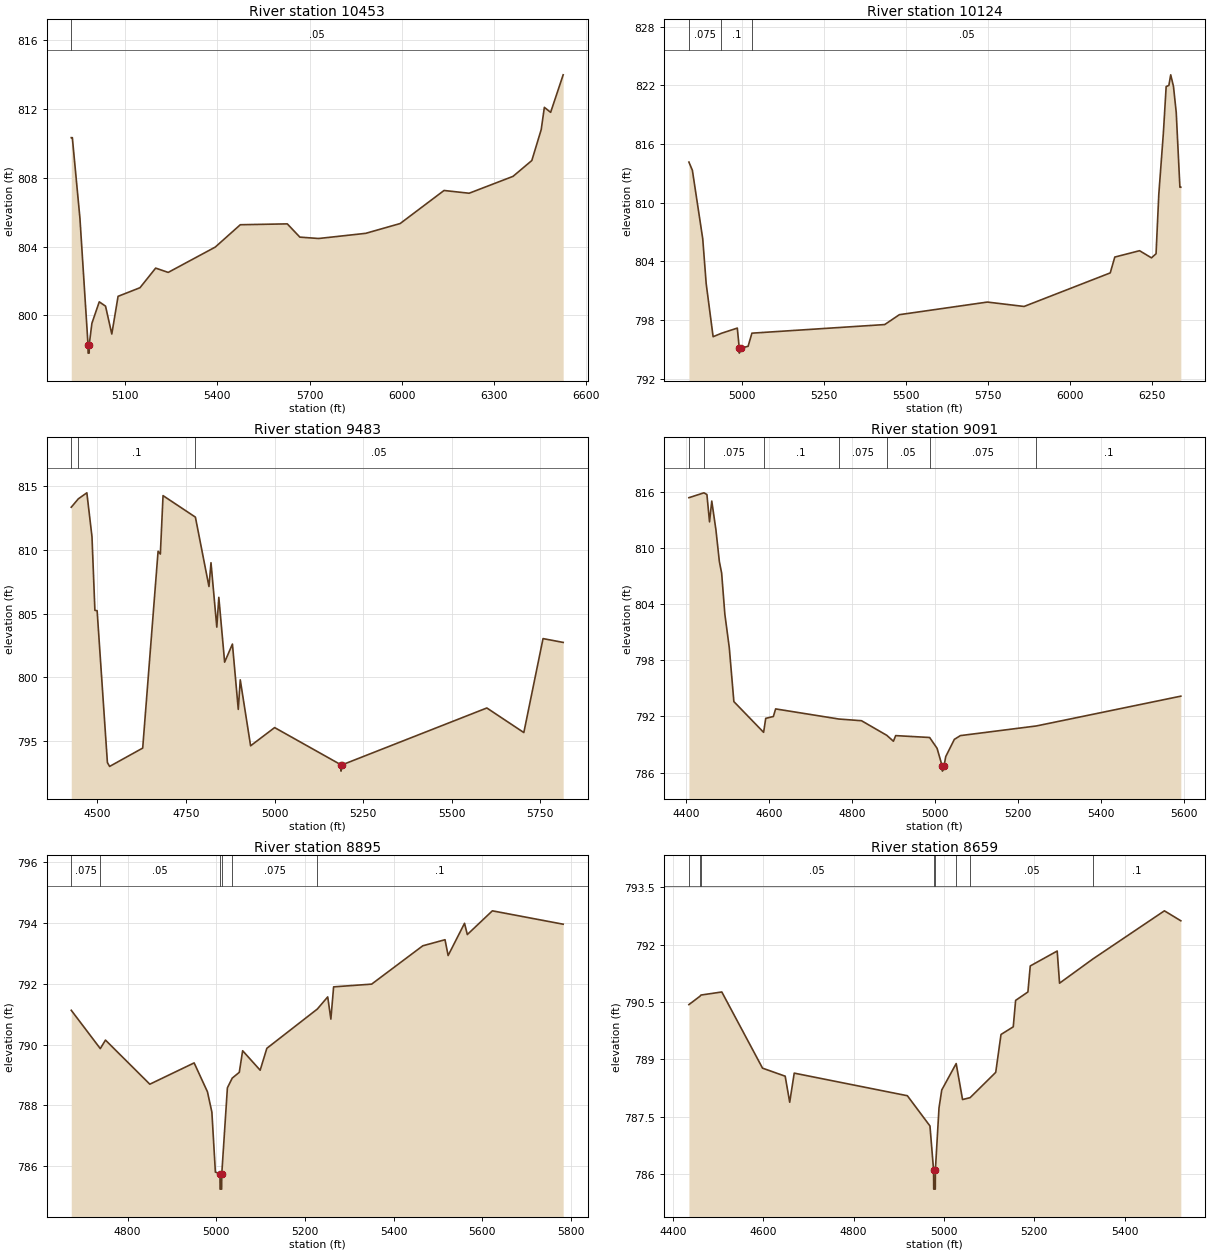
Type RM Length L Ch R = 1,10453,329,329,329
BEGIN DESCRIPTION:
Unnamed Tributary to Walnut Creek 2B 20.0
END DESCRIPTION:
XS GIS Cut Line= 3
      2309878.97      7029309.97      2309829.00      7029260.00
      2308328.97      7028959.99
#Sta/Elev= 30
  4924.9  810.33  4928.4  810.33  4953.1  805.65  4979.4  798.31  4979.7  797.81
  4983.2  797.81  4983.4  798.31  4992.0  799.54  5016.0  800.79  5036.4  800.54
  5056.8  798.92  5077.2  801.11  5148.5  801.61  5199.5  802.75  5240.3  802.50
  5393.3  803.97  5474.9  805.27  5627.8  805.32  5668.6  804.55  5729.8  804.47
  5882.8  804.77  5995.0  805.34  6137.7  807.26  6219.3  807.10  6362.1  808.08
  6423.3  809.00  6453.9  810.80  6464.1  812.09  6484.5  811.80  6525.3  813.98
#Mann=1,-1,0
  4924.9    0.05       0
Bank Sta=4979.4,4983.4
Exp/Cntr=0.3,0.1

Type RM Length L Ch R = 1,10124,641,641,641
BEGIN DESCRIPTION:
Unnamed Tributary to Walnut Creek 2B 19.0
END DESCRIPTION:
XS GIS Cut Line= 3
      2310079.01      7029160.02      2310029.00      7029010.00
      2308828.98      7028409.99
#Sta/Elev= 30
  4837.5  814.15  4848.1  813.31  4879.7  806.30  4890.2  801.71  4911.3  796.30
  4936.8  796.65  4985.1  797.18  4991.0  795.12  4991.3  794.62  4995.0  795.12
  5018.0  795.32  5029.6  796.66  5434.5  797.54  5479.2  798.55  5747.5  799.84
  5859.3  799.39  6122.1  802.82  6136.0  804.44  6211.5  805.09  6247.8  804.36
  6261.8  804.78  6270.2  810.86  6284.2  817.16  6292.6  821.87  6300.9  821.99
  6306.5  823.07  6314.9  821.89  6323.3  819.23  6334.5  811.58  6337.3  811.58
#Mann=3,-1,0
  4837.5   0.075       0  4936.8     0.1       0  5029.6    0.05       0
Bank Sta=4991,4995
Exp/Cntr=0.3,0.1

Type RM Length L Ch R = 1,9483,392,392,392
BEGIN DESCRIPTION:
Unnamed Tributary to Walnut Creek 2B 18.0
END DESCRIPTION:
XS GIS Cut Line= 5
      2310180.85      7029154.75      2310396.73      7028876.14
      2310532.02      7028617.80      2310523.75      7028553.89
      2310436.54      7027879.94
#Sta/Elev= 30
  4426.4  813.36  4446.4  814.02  4470.4  814.49  4484.9  811.04  4493.1  805.26
  4499.4  805.23  4528.4  793.30  4534.7  793.00  4628.0  794.44  4671.4  809.90
  4677.8  809.68  4685.4  814.27  4776.7  812.58  4815.0  807.13  4820.7  809.00
  4837.1  803.94  4842.8  806.28  4859.2  801.19  4881.2  802.61  4897.7  797.48
  4903.3  799.80  4932.5  794.62  5000.3  796.05  5187.3  793.13  5187.5  792.63
  5191.3  793.13  5599.1  797.59  5703.5  795.66  5757.7  803.04  5814.5  802.74
#Mann=3,-1,0
  4426.4   0.075       0  4446.4     0.1       0  4776.7    0.05       0
Bank Sta=5187.3,5191.3
Exp/Cntr=0.3,0.1

Type RM Length L Ch R = 1,9091,196,196,196
BEGIN DESCRIPTION:
Unnamed Tributary to Walnut Creek 2B 16.0
END DESCRIPTION:
XS GIS Cut Line= 4
      2310258.91      7029144.39      2310781.35      7028927.23
      2310910.05      7028829.31      2311264.00      7028537.85
#Sta/Elev= 30
  4405.9  815.35  4442.1  815.87  4449.3  815.69  4455.6  812.77  4461.0  814.99
  4471.0  811.93  4479.4  808.51  4484.8  807.31  4492.6  802.90  4503.3  799.32
  4514.3  793.59  4586.0  790.31  4591.1  791.80  4609.5  792.00  4615.0  792.81
  4767.4  791.73  4822.0  791.55  4883.0  789.99  4899.0  789.36  4904.4  789.96
  4986.3  789.76  5004.3  788.60  5016.8  786.67  5017.1  786.17  5020.8  786.67
  5025.1  787.72  5045.9  789.56  5060.4  789.96  5243.6  790.99  5591.9  794.17
#Mann=7,-1,0
  4405.9     0.1       0  4442.1   0.075       0  4586.0     0.1       0
  4767.4   0.075       0  4883.0    0.05       0  4986.3   0.075       0
  5243.6     0.1       0
Bank Sta=5016.8,5020.8
Exp/Cntr=0.3,0.1

Type RM Length L Ch R = 1,8895,236,236,236
BEGIN DESCRIPTION:
Unnamed Tributary to Walnut Creek 2B 15.2
END DESCRIPTION:
XS GIS Cut Line= 4
      2310641.84      7029001.19      2310969.95      7029001.19
      2311196.51      7028938.69      2311639.25      7028618.35
#Sta/Elev= 30
  4673.0  791.13  4738.5  789.87  4750.2  790.15  4850.2  788.70  4950.2  789.40
  4980.2  788.45  4990.2  787.78  4998.1  785.81  5008.5  785.75  5008.7  785.25
  5012.2  785.25  5012.5  785.75  5025.2  788.58  5036.1  788.90  5052.0  789.09
  5059.6  789.80  5099.1  789.16  5114.2  789.88  5228.0  791.17  5251.5  791.57
  5258.6  790.84  5264.8  791.90  5350.6  791.99  5465.9  793.25  5516.1  793.45
  5523.1  792.93  5560.1  793.99  5566.4  793.62  5622.9  794.40  5782.6  793.96
#Mann=6,-1,0
  4673.0   0.075       0  4738.5    0.05       0  5008.5    0.05       0
  5012.5    0.05       0  5036.1   0.075       0  5228.0     0.1       0
Bank Sta=5008.5,5012.5
Exp/Cntr=0.3,0.1

Type RM Length L Ch R = 1,8659,672,672,672
BEGIN DESCRIPTION:
Unnamed Tributary to Walnut Creek 2B 15.3
END DESCRIPTION:
XS GIS Cut Line= 3
      2310566.26      7029076.71      2311126.20      7029102.75
      2311629.65      7028944.45
#Sta/Elev= 30
  4435.8  790.43  4460.4  790.65  4462.5  790.68  4508.6  790.76  4598.7  788.77
  4648.8  788.56  4658.8  787.88  4668.8  788.64  4919.1  788.05  4969.1  787.26
  4977.1  786.11  4977.4  785.61  4980.9  785.61  4981.1  786.11  4989.1  787.73
  4995.2  788.20  5027.1  788.89  5041.2  787.95  5058.0  788.00  5114.6  788.66
  5126.3  789.65  5153.4  789.85  5158.6  790.54  5185.8  790.76  5191.0  791.44
  5250.6  791.83  5255.8  790.99  5329.3  791.62  5487.8  792.88  5524.1  792.62
#Mann=8,-1,0
  4435.8     0.1       0  4460.4   0.075       0  4462.5    0.05       0
  4977.1    0.05       0  4981.1    0.05       0  5027.1   0.075       0
  5058.0    0.05       0  5329.3     0.1       0
Bank Sta=4977.1,4981.1
Exp/Cntr=0.3,0.1

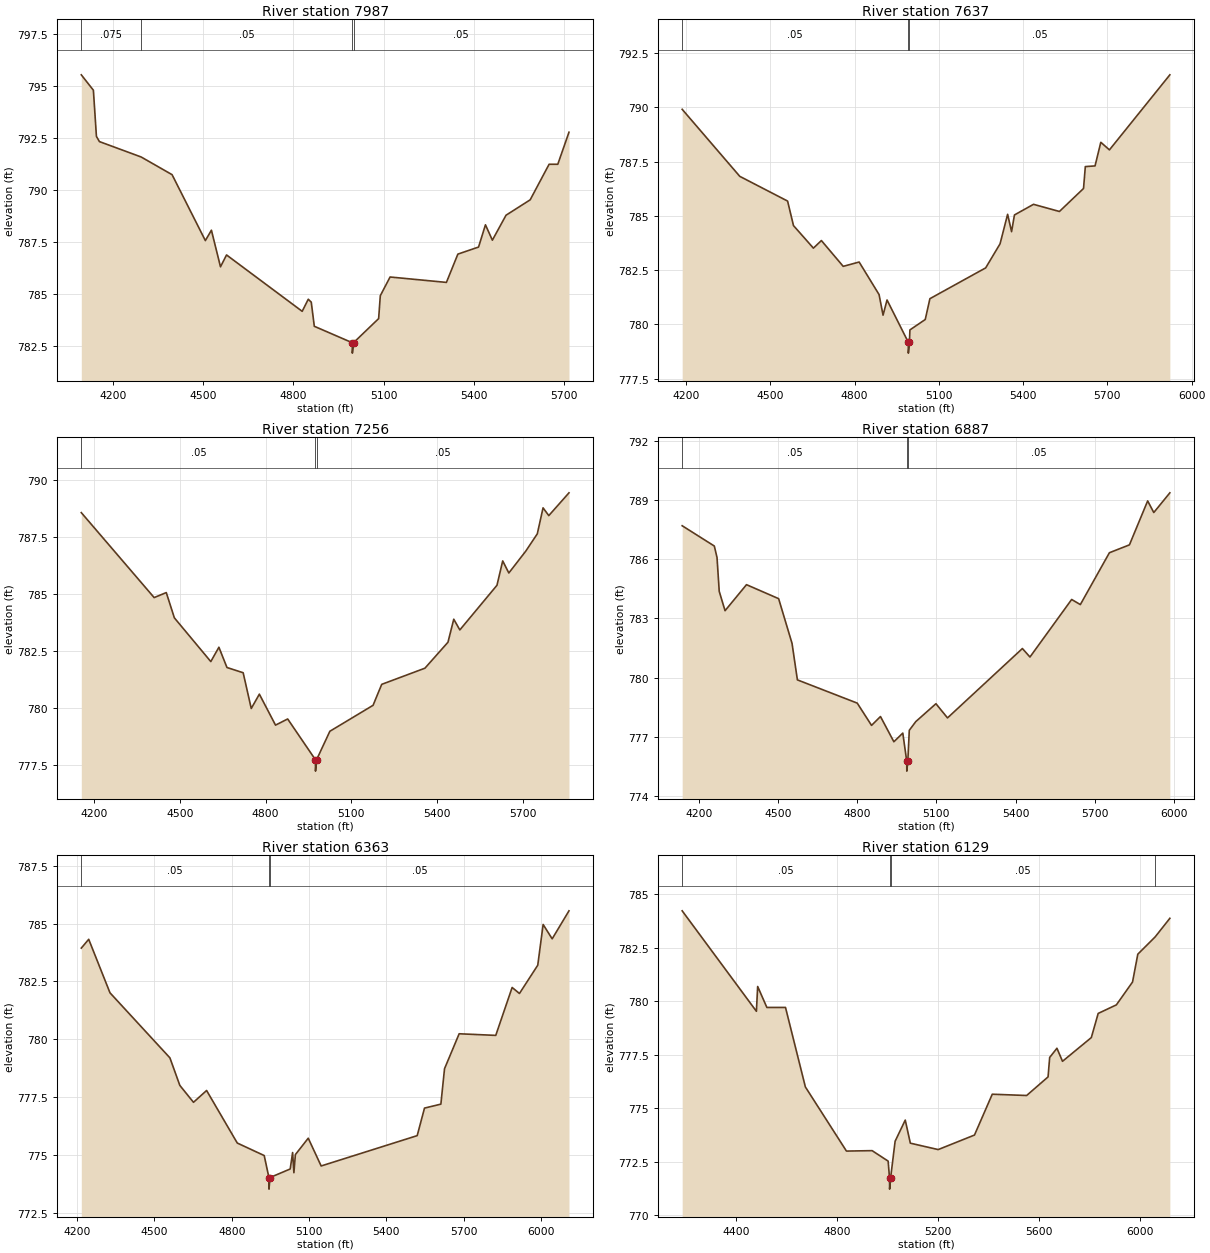
Type RM Length L Ch R = 1,7987,350,350,350
BEGIN DESCRIPTION:
Unnamed Tributary to Walnut Creek 2B 15.0
END DESCRIPTION:
XS GIS Cut Line= 3
      2310379.04      7029610.00      2311279.00      7029710.00
      2311579.01      7029059.99
#Sta/Elev= 30
  4094.9  795.56  4135.1  794.82  4145.2  792.60  4155.2  792.35  4293.9  791.61
  4396.7  790.76  4507.4  787.59  4527.5  788.09  4557.7  786.33  4577.8  786.90
  4829.3  784.19  4849.5  784.77  4859.5  784.63  4869.6  783.47  4995.9  782.68
  4996.1  782.18  4999.9  782.68  5083.5  783.84  5089.0  784.94  5121.5  785.84
  5308.8  785.58  5346.9  786.94  5415.7  787.28  5438.6  788.35  5461.6  787.61
  5507.0  788.81  5587.3  789.55  5650.2  791.26  5679.1  791.26  5716.3  792.80
#Mann=4,-1,0
  4094.9   0.075       0  4293.9    0.05       0  4995.9   0.033       0
  4999.9    0.05       0
Bank Sta=4995.9,4999.9
Exp/Cntr=0.3,0.1

Type RM Length L Ch R = 1,7637,381,381,381
BEGIN DESCRIPTION:
Unnamed Tributary to Walnut Creek 2B 14.0
END DESCRIPTION:
XS GIS Cut Line= 3
      2310878.99      7030610.01      2311429.00      7030010.00
      2311629.00      7029110.01
#Sta/Elev= 30
  4186.5  789.91  4391.5  786.82  4561.7  785.68  4582.7  784.55  4653.6  783.51
  4682.0  783.86  4759.7  782.67  4816.4  782.87  4887.3  781.37  4901.5  780.42
  4915.7  781.12  4991.4  779.17  4991.6  778.67  4995.4  779.17  4997.1  779.74
  5051.7  780.22  5068.3  781.18  5266.8  782.60  5318.0  783.71  5344.9  785.07
  5359.0  784.27  5369.2  785.04  5437.1  785.53  5529.3  785.20  5615.1  786.26
  5621.5  787.27  5656.1  787.30  5676.6  788.39  5707.3  788.04  5922.4  791.50
#Mann=3,-1,0
  4186.5    0.05       0  4991.4   0.033       0  4995.4    0.05       0
Bank Sta=4991.4,4995.4
Exp/Cntr=0.3,0.1

Type RM Length L Ch R = 1,7256,369,369,369
BEGIN DESCRIPTION:
Unnamed Tributary to Walnut Creek 2B 13.0
END DESCRIPTION:
XS GIS Cut Line= 3
      2311178.98      7030710.02      2311779.00      7030110.00
      2311679.00      7029260.01
#Sta/Elev= 30
  4156.0  788.56  4410.6  784.83  4453.0  785.05  4481.3  783.94  4608.6  782.02
  4636.9  782.65  4665.1  781.76  4721.7  781.53  4750.0  779.96  4778.3  780.59
  4834.8  779.23  4877.3  779.50  4974.3  777.71  4974.5  777.21  4978.3  777.71
  5024.7  778.96  5175.7  780.10  5205.9  781.02  5357.0  781.73  5437.5  782.87
  5457.7  783.88  5479.0  783.41  5608.7  785.37  5628.8  786.44  5650.2  785.91
  5709.4  786.87  5749.7  787.63  5769.8  788.77  5789.9  788.43  5860.4  789.43
#Mann=3,-1,0
  4156.0    0.05       0  4974.3   0.033       0  4978.3    0.05       0
Bank Sta=4974.3,4978.3
Exp/Cntr=0.3,0.1

Type RM Length L Ch R = 1,6887,524,524,524
BEGIN DESCRIPTION:
Unnamed Tributary to Walnut Creek 2B 12.0
END DESCRIPTION:
XS GIS Cut Line= 3
      2311979.00      7031009.98      2312129.00      7030160.00
      2311729.00      7029260.00
#Sta/Elev= 30
  4136.9  787.70  4258.7  786.67  4268.9  786.09  4277.3  784.37  4299.4  783.39
  4380.6  784.71  4502.4  784.00  4553.2  781.73  4573.5  779.88  4800.3  778.70
  4854.5  777.57  4888.3  778.02  4939.1  776.74  4972.9  777.18  4987.9  775.75
  4988.1  775.25  4991.9  775.75  4997.5  777.32  5021.9  777.76  5098.5  778.67
  5142.3  777.95  5426.1  781.47  5454.8  781.04  5612.8  783.96  5645.7  783.70
  5755.8  786.33  5831.7  786.73  5900.8  788.96  5924.0  788.37  5984.9  789.37
#Mann=3,-1,0
  4136.9    0.05       0  4987.9   0.033       0  4991.9    0.05       0
Bank Sta=4987.9,4991.9
Exp/Cntr=0.3,0.1

Type RM Length L Ch R = 1,6363,234,234,234
BEGIN DESCRIPTION:
Unnamed Tributary to Walnut Creek 2B 11.0
END DESCRIPTION:
XS GIS Cut Line= 4
      2312494.69      7030878.32      2312631.30      7030131.26
      2312647.34      7029746.16      2312146.62      7029190.73
#Sta/Elev= 30
  4216.3  783.94  4245.1  784.32  4327.6  782.01  4560.2  779.20  4598.7  778.01
  4651.7  777.28  4702.6  777.79  4821.7  775.52  4926.2  774.98  4944.5  774.03
  4944.8  773.53  4948.5  774.03  5027.1  774.40  5036.4  775.11  5041.4  774.24
  5047.1  775.02  5097.1  775.73  5147.2  774.53  5519.9  775.84  5548.3  777.03
  5611.8  777.20  5626.0  778.73  5682.8  780.24  5824.8  780.17  5888.4  782.24
  5916.8  781.98  5987.8  783.20  6008.7  784.96  6043.8  784.34  6109.0  785.55
#Mann=3,-1,0
  4216.3    0.05       0  4944.5   0.033       0  4948.5    0.05       0
Bank Sta=4944.5,4948.5
Exp/Cntr=0.3,0.1

Type RM Length L Ch R = 1,6129,383,383,383
BEGIN DESCRIPTION:
Unnamed Tributary to Walnut Creek 2B 10.0
END DESCRIPTION:
XS GIS Cut Line= 4
      2312679.01      7030809.95      2312829.00      7030010.00
      2312803.64      7029744.20      2312273.97      7029076.73
#Sta/Elev= 30
  4186.0  784.23  4480.2  779.53  4485.2  780.69  4521.7  779.71  4595.5  779.71
  4674.3  775.99  4837.1  772.99  4938.8  773.01  5002.4  772.52  5007.9  771.71
  5008.2  771.21  5011.9  771.71  5030.0  773.45  5070.2  774.44  5090.3  773.36
  5200.8  773.06  5344.6  773.74  5415.1  775.65  5551.3  775.59  5636.2  776.46
  5642.6  777.37  5671.4  777.80  5693.5  777.19  5807.7  778.30  5834.9  779.43
  5907.0  779.83  5971.1  780.90  5991.9  782.20  6060.7  783.01  6119.0  783.88
#Mann=4,-1,0
  4186.0    0.05       0  5007.9    0.05       0  5011.9    0.05       0
  6060.7   0.075       0
Bank Sta=5007.9,5011.9
Exp/Cntr=0.3,0.1

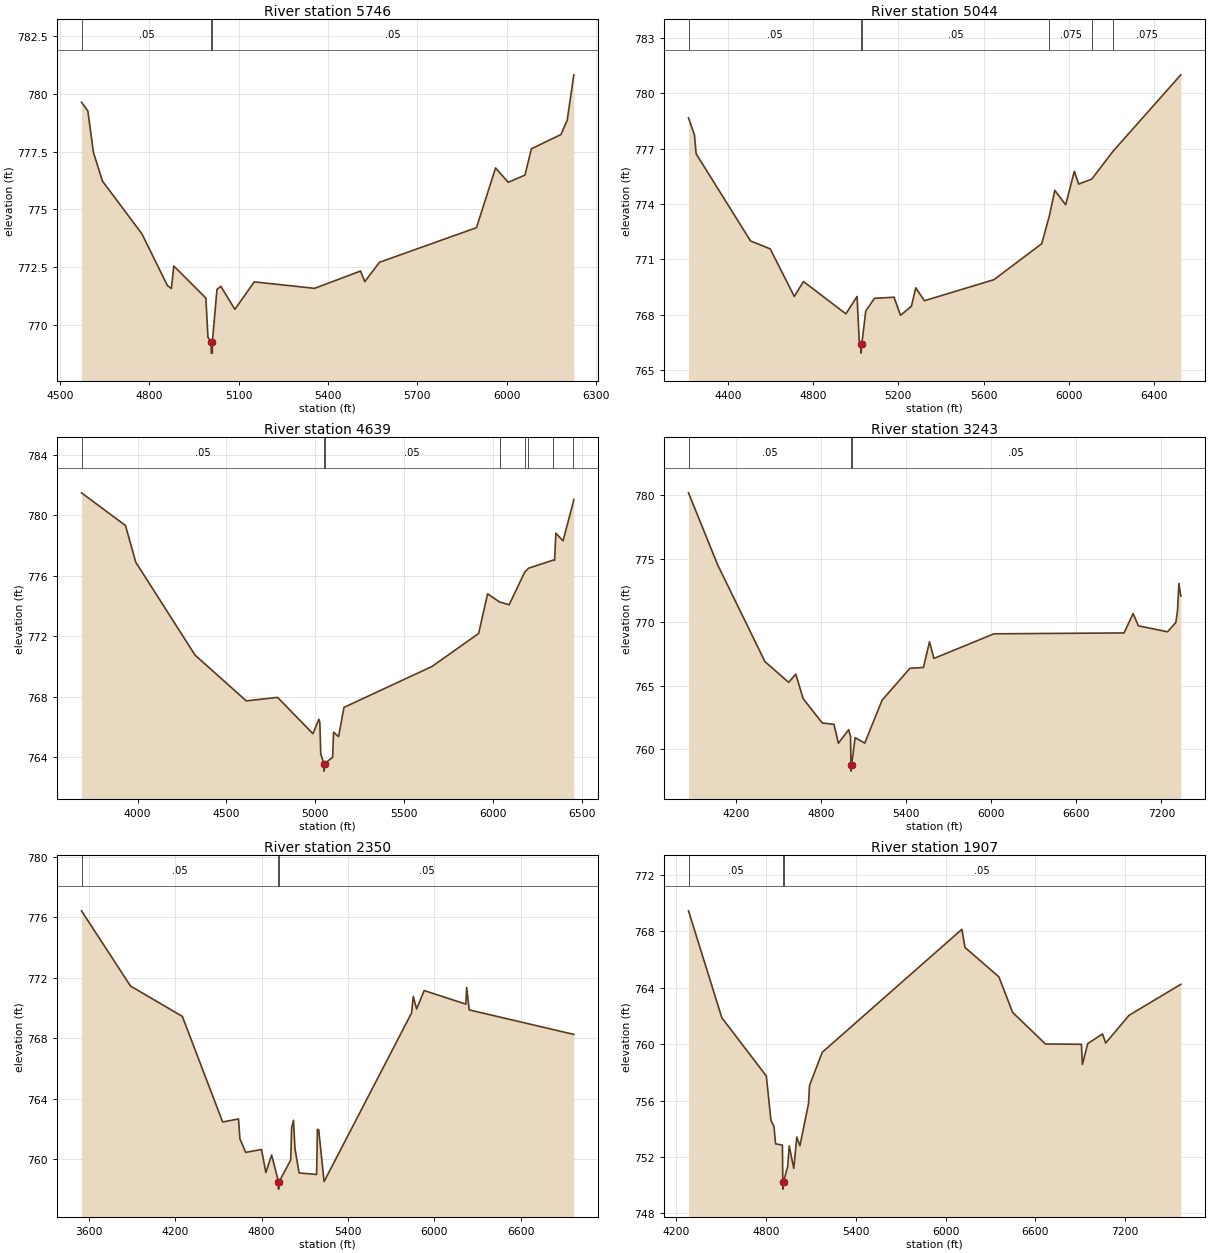
Type RM Length L Ch R = 1,5746,702,702,702
BEGIN DESCRIPTION:
Unnamed Tributary to Walnut Creek 2B 9.0
END DESCRIPTION:
XS GIS Cut Line= 4
      2313029.02      7030409.96      2313179.00      7030010.00
      2313107.18      7029590.30      2312516.98      7029050.62
#Sta/Elev= 30
  4572.9  779.64  4594.2  779.26  4612.9  777.46  4643.2  776.22  4775.8  773.93
  4861.2  771.69  4874.6  771.56  4882.6  772.54  4990.3  771.15  4997.4  769.44
  5008.2  769.26  5008.4  768.76  5011.9  768.76  5012.2  769.26  5027.6  771.52
  5040.6  771.66  5087.6  770.66  5152.8  771.85  5355.1  771.57  5509.6  772.32
  5523.8  771.86  5573.1  772.70  5898.8  774.20  5962.9  776.79  6005.5  776.17
  6061.6  776.48  6083.2  777.62  6182.2  778.24  6203.4  778.86  6225.6  780.83
#Mann=3,-1,0
  4572.9    0.05       0  5008.2    0.04       0  5012.2    0.05       0
Bank Sta=5008.2,5012.2
Exp/Cntr=0.3,0.1

Type RM Length L Ch R = 1,5044,405,405,405
BEGIN DESCRIPTION:
Unnamed Tributary to Walnut Creek 2B 8.0
END DESCRIPTION:
XS GIS Cut Line= 3
      2313128.98      7030460.01      2313729.00      7029960.00
      2314029.01      7028459.95
#Sta/Elev= 30
  4215.3  778.67  4243.3  777.74  4251.1  776.72  4506.3  772.00  4598.7  771.57
  4711.9  768.99  4754.9  769.80  4954.0  768.05  5006.5  768.99  5016.7  766.58
  5024.9  766.42  5025.2  765.92  5028.9  766.42  5047.3  768.20  5088.1  768.89
  5179.9  768.95  5210.5  767.97  5261.5  768.46  5281.9  769.46  5322.7  768.76
  5649.0  769.90  5873.4  771.85  5909.6  773.38  5934.6  774.74  5985.6  773.96
  6026.3  775.77  6046.7  775.08  6108.1  775.35  6207.3  776.85  6526.1  781.00
#Mann=6,-1,0
  4215.3    0.05       0  5024.9   0.033       0  5028.9    0.05       0
  5909.6   0.075       0  6108.1    0.05       0  6207.3   0.075       0
Bank Sta=5024.9,5028.9
Exp/Cntr=0.3,0.1

Type RM Length L Ch R = 1,4639,1396,1396,1396
BEGIN DESCRIPTION:
Unnamed Tributary to Walnut Creek 2B 7.0
END DESCRIPTION:
XS GIS Cut Line= 3
      2312929.00      7030710.00      2314029.00      7030010.00
      2314229.00      7028559.97
#Sta/Elev= 30
  3685.1  781.47  3932.3  779.31  3989.9  776.89  4323.5  770.75  4611.3  767.73
  4787.4  767.96  4986.0  765.56  5019.2  766.52  5024.9  766.30  5030.0  764.23
  5047.3  763.59  5047.7  763.09  5051.8  763.59  5096.8  764.00  5101.9  765.66
  5130.3  765.37  5160.6  767.30  5655.2  770.00  5917.7  772.18  5968.1  774.80
  6035.5  774.26  6089.3  774.08  6177.0  776.24  6197.9  776.49  6338.0  777.03
  6344.8  777.01  6351.7  778.80  6392.1  778.30  6447.2  780.74  6452.7  781.03
#Mann=8,-1,0
  3685.1    0.05       0  5047.3    0.04       0  5051.8    0.05       0
  6035.5   0.075       0  6177.0    0.05       0  6197.9   0.075       0
  6338.0    0.05       0  6447.2   0.075       0
Bank Sta=5047.3,5051.8
Exp/Cntr=0.3,0.1

Type RM Length L Ch R = 1,3243,893,893,893
BEGIN DESCRIPTION:
Unnamed Tributary to Walnut Creek 2B 6.0
END DESCRIPTION:
XS GIS Cut Line= 3
      2313028.97      7030759.99      2314129.00      7031060.00
      2315329.01      7029059.99
#Sta/Elev= 30
  3864.5  780.20  4070.1  774.52  4403.5  766.89  4571.1  765.25  4621.2  765.90
  4673.0  763.97  4807.8  762.05  4890.7  761.94  4921.8  760.45  4994.3  761.52
  5007.6  760.98  5010.2  758.75  5010.7  758.25  5014.8  758.75  5039.7  760.89
  5107.7  760.46  5230.2  763.85  5426.5  766.36  5521.7  766.43  5564.5  768.45
  5595.6  767.14  6019.3  769.08  6936.7  769.15  7000.8  770.68  7037.8  769.71
  7243.8  769.24  7302.1  769.97  7313.8  770.89  7323.5  773.05  7337.1  772.06
#Mann=3,-1,0
  3864.5    0.05       0  5010.2    0.04       0  5014.8    0.05       0
Bank Sta=5010.2,5014.8
Exp/Cntr=0.3,0.1

Type RM Length L Ch R = 1,2350,443,443,443
BEGIN DESCRIPTION:
Unnamed Tributary to Walnut Creek 2B 5.0
END DESCRIPTION:
XS GIS Cut Line= 3
      2312678.97      7031760.00      2314129.00      7031710.00
      2314929.01      7029909.97
#Sta/Elev= 30
  3549.1  776.44  3889.3  771.47  4249.5  769.46  4529.7  762.48  4639.8  762.68
  4649.8  761.37  4689.8  760.47  4799.9  760.66  4829.9  759.13  4869.9  760.30
  4917.6  758.54  4918.1  758.04  4922.3  758.54  5002.7  759.97  5008.9  762.09
  5021.9  762.59  5032.1  760.73  5060.9  759.11  5182.6  759.01  5188.1  761.99
  5197.0  761.97  5234.6  758.54  5842.6  769.69  5854.2  770.78  5877.5  769.95
  5930.2  771.17  6219.5  770.27  6225.6  771.37  6242.7  769.89  6969.8  768.27
#Mann=3,-1,0
  3549.1    0.05       0  4917.6   0.033       0  4922.3    0.05       0
Bank Sta=4917.6,4922.3
Exp/Cntr=0.3,0.1

Type RM Length L Ch R = 1,1907,464,464,464
BEGIN DESCRIPTION:
Unnamed Tributary to Walnut Creek 2B 4.0
END DESCRIPTION:
XS GIS Cut Line= 3
      2313478.97      7031859.99      2314260.27      7032018.65
      2315979.00      7030210.00
#Sta/Elev= 30
  4280.6  769.45  4503.4  761.87  4801.0  757.74  4831.7  754.60  4852.1  754.16
  4862.9  752.93  4908.5  752.84  4911.2  750.22  4911.7  749.72  4915.9  750.22
  4943.9  751.33  4954.0  752.78  4984.7  751.19  5004.6  753.41  5025.5  752.79
  5083.1  755.78  5090.0  757.07  5174.9  759.42  6108.8  768.14  6129.9  766.85
  6356.4  764.77  6448.2  762.25  6667.5  760.01  6908.1  759.99  6915.0  758.56
  6950.6  760.04  7049.3  760.72  7070.7  760.08  7226.4  762.04  7572.9  764.24
#Mann=3,-1,0
  4280.6    0.05       0  4911.2   0.033       0  4915.9    0.05       0
Bank Sta=4911.2,4915.9
Exp/Cntr=0.3,0.1

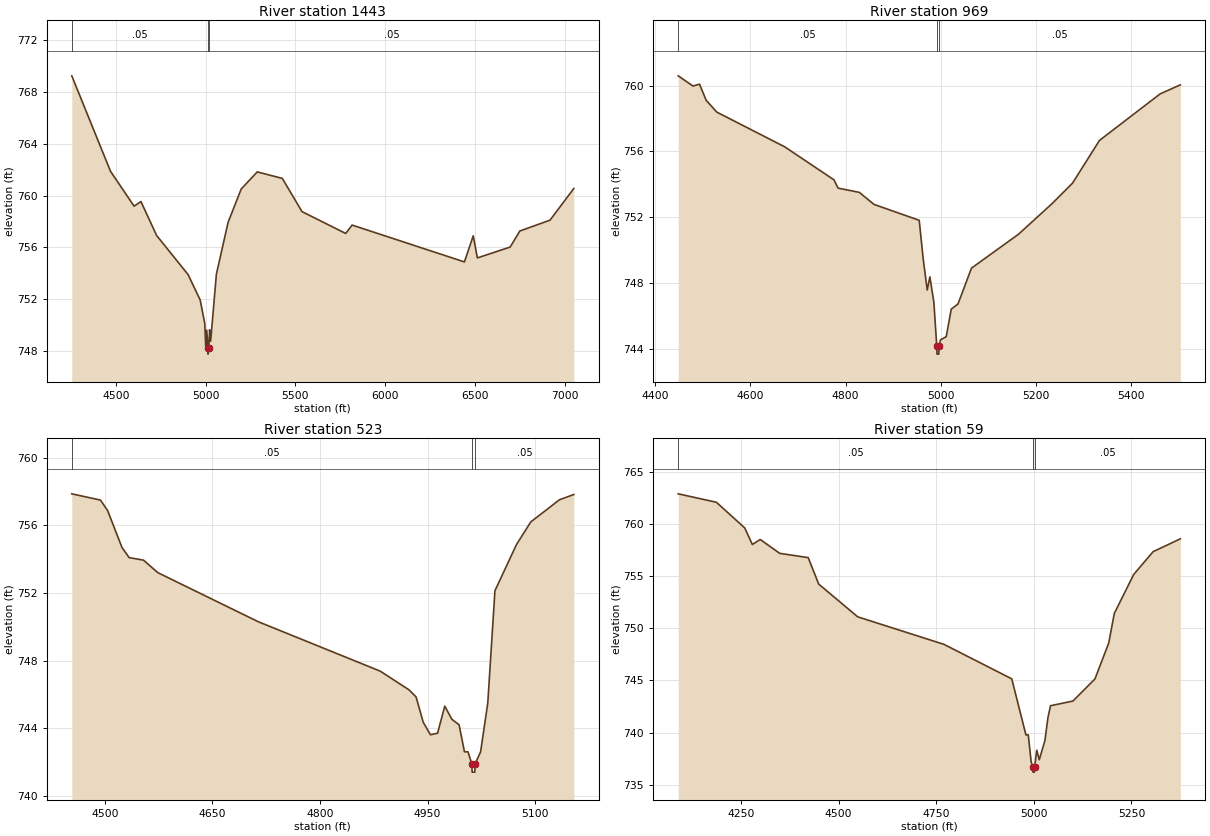
Type RM Length L Ch R = 1,1443,474,474,474
BEGIN DESCRIPTION:
Unnamed Tributary to Walnut Creek 2B 3.0
END DESCRIPTION:
XS GIS Cut Line= 3
      2313478.96      7031909.98      2314129.00      7032260.00
      2315928.99      7031260.01
#Sta/Elev= 30
  4254.1  769.26  4469.9  761.88  4601.4  759.18  4639.5  759.54  4727.1  756.91
  4902.3  753.89  4969.7  751.92  4995.2  750.10  5000.4  748.38  5006.1  749.59
  5012.9  748.24  5013.4  747.74  5017.6  748.24  5022.1  749.62  5027.8  748.74
  5059.9  753.92  5125.1  757.93  5198.3  760.51  5287.5  761.83  5427.1  761.33
  5536.9  758.76  5780.6  757.07  5816.0  757.72  6441.8  754.87  6491.0  756.89
  6513.9  755.18  6696.9  756.02  6750.6  757.26  6918.8  758.10  7051.5  760.55
#Mann=3,-1,0
  4254.1    0.05       0  5012.9    0.04       0  5017.6    0.05       0
Bank Sta=5012.9,5017.6
Exp/Cntr=0.3,0.1

Type RM Length L Ch R = 1,969,446,446,446
BEGIN DESCRIPTION:
Unnamed Tributary to Walnut Creek 2B 2.0
END DESCRIPTION:
XS GIS Cut Line= 3
      2313578.98      7032409.99      2314079.00      7032660.00
      2314428.99      7032310.01
#Sta/Elev= 30
  4448.7  760.60  4479.5  759.98  4493.4  760.09  4507.4  759.11  4529.8  758.39
  4672.3  756.28  4775.8  754.27  4784.1  753.77  4828.9  753.51  4859.6  752.78
  4954.6  751.81  4963.0  749.45  4971.4  747.57  4977.0  748.37  4985.4  746.82
  4991.4  744.17  4991.9  743.67  4995.6  743.67  4996.2  744.17  4999.4  744.54
  5011.3  744.73  5021.9  746.41  5036.0  746.72  5064.3  748.90  5163.3  750.97
  5234.0  752.84  5276.4  754.07  5333.0  756.67  5460.3  759.50  5502.7  760.05
#Mann=3,-1,0
  4448.7    0.05       0  4991.4   0.033       0  4996.2    0.05       0
Bank Sta=4991.4,4996.2
Exp/Cntr=0.3,0.1

Type RM Length L Ch R = 1,523,464,464,464
BEGIN DESCRIPTION:
Unnamed Tributary to Walnut Creek 2B 1.0
END DESCRIPTION:
XS GIS Cut Line= 3
      2313678.97      7032960.00      2314229.00      7032960.00
      2314378.97      7032960.00
#Sta/Elev= 30
  4454.0  757.87  4494.0  757.50  4504.0  756.88  4524.0  754.70  4534.0  754.10
  4554.0  753.95  4574.0  753.21  4714.0  750.31  4884.0  747.39  4924.0  746.29
  4934.0  745.87  4944.0  744.37  4954.0  743.63  4964.0  743.72  4974.0  745.32
  4984.0  744.54  4994.0  744.22  5001.5  742.62  5006.5  742.62  5011.6  741.92
  5012.2  741.42  5015.9  741.42  5016.5  741.92  5024.0  742.62  5034.0  745.51
  5044.0  752.14  5074.0  754.87  5094.0  756.21  5134.0  757.52  5154.0  757.83
#Mann=3,-1,0
  4454.0    0.05       0  5011.6   0.033       0  5016.5    0.05       0
Bank Sta=5011.6,5016.5
Exp/Cntr=0.3,0.1

Type RM Length L Ch R = 1,59,0,0,0
BEGIN DESCRIPTION:
9999
END DESCRIPTION:
XS GIS Cut Line= 3
      2313403.34      7033200.92      2314274.93      7033383.75
      2314520.75      7033074.89
#Sta/Elev= 30
  4089.7  762.90  4187.4  762.09  4259.9  759.63  4279.4  758.04  4299.6  758.52
  4349.5  757.19  4422.4  756.78  4449.3  754.24  4549.1  751.10  4769.8  748.46
  4943.5  745.15  4979.8  739.77  4985.8  739.77  4993.1  737.21  4997.0  736.70
  4997.7  736.20  5001.4  736.20  5002.0  736.70  5007.5  738.30  5013.9  737.39
  5028.4  739.23  5036.2  741.44  5042.8  742.57  5100.1  743.02  5156.5  745.14
  5191.7  748.58  5206.1  751.43  5255.8  755.17  5305.4  757.35  5375.0  758.58
#Mann=3,-1,0
  4089.7    0.05       0  4997.0   0.033       0  5002.0    0.05       0
Bank Sta=4997,5002
Exp/Cntr=0.3,0.1

Chan Stop Cuts=-1