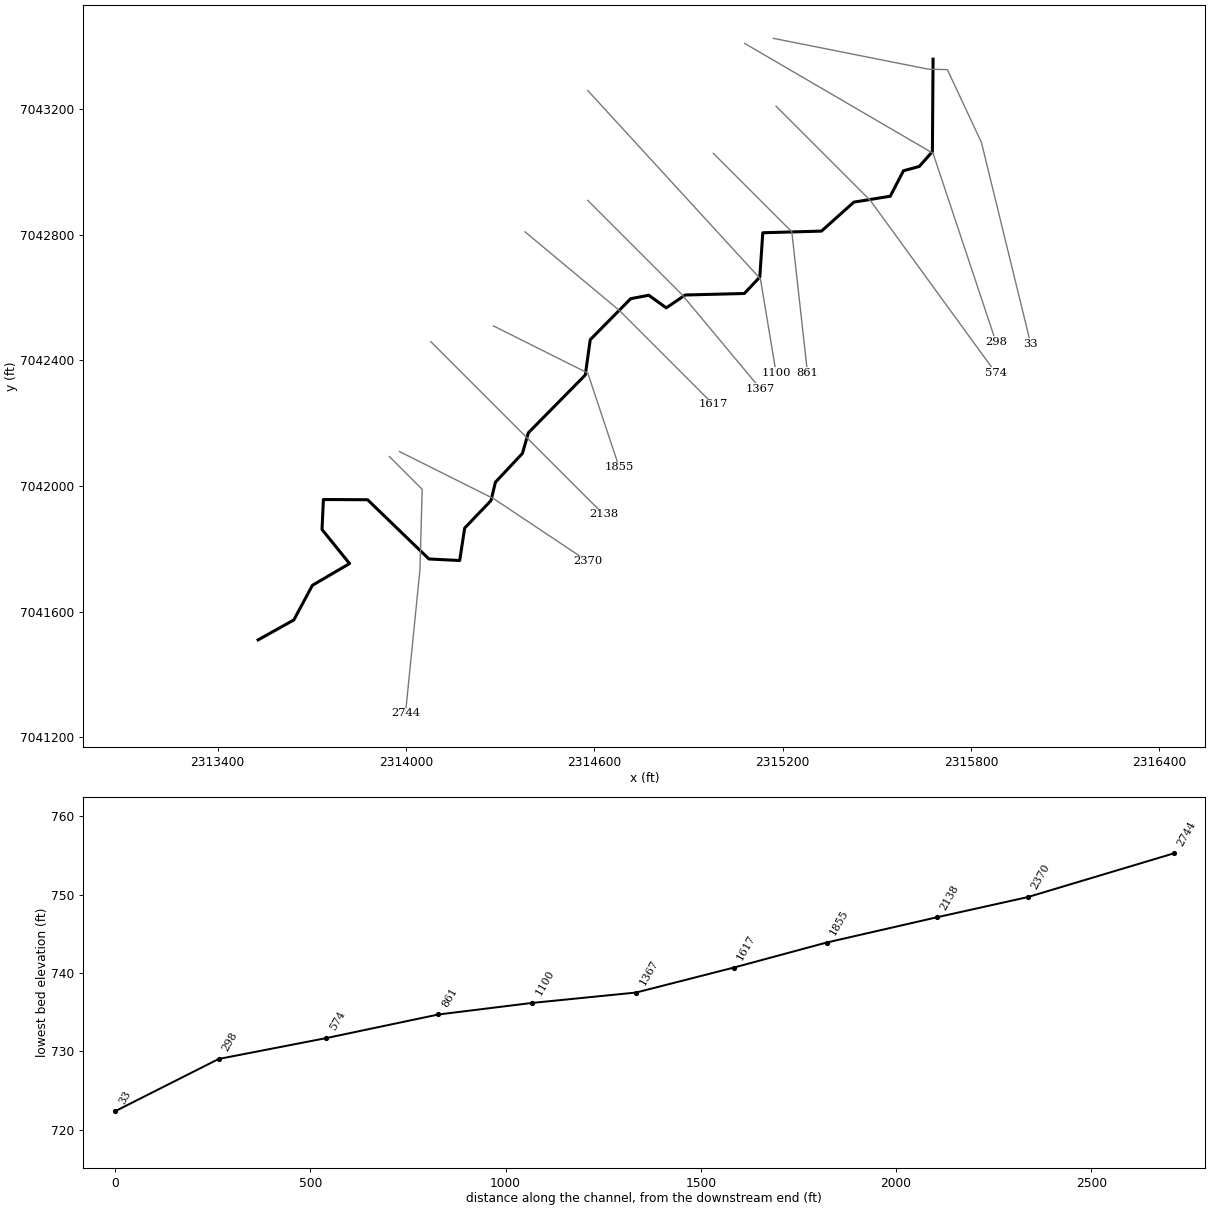
--- Unnamed Tr to Walnut Cr 2D.prj (project) ---

Proj Title=Unnamed Tr to Walnut Cr 2D Base Level Engineering
Current Plan=p01
Default Exp/Contr=0.3,0.1
English Units
Geom File=g01
Flow File=f01
Plan File=p01
BEGIN DESCRIPTION:
Unnamed Tr to Walnut Cr 2D
END DESCRIPTION:

--- Unnamed Tr to Walnut Cr 2D.p01 (plan) ---

Plan Title=Multiple Run
Short Identifier=Multiple
Geom File=g01
Flow File=f01
Subcritical Flow
K Sum by GR= 0
Std Step Tol= 0.01
Critical Tol= 0.01
Num of Std Step Trials= 20
Max Error Tol= 0.3
Flow Tol Ratio= 0.001
Split Flow NTrial= 30
Split Flow Tol= 0.02
Split Flow Ratio= 0.02
Log Output Level= 0
Friction Slope Method= 1
Unsteady Friction Slope Method= 2
Unsteady Bridges Friction Slope Method= 1
Parabolic Critical Depth
Global Vel Dist=  1 , 1 , 1
Global Log Level= 0
CheckData=True
Encroach Param= -1, 0, 0, 0
BEGIN DESCRIPTION:
Multiple Run
END DESCRIPTION:

--- Unnamed Tr to Walnut Cr 2D.f01 (steady flow) ---

Flow Title=Multiple
Number of Profiles=7
Profile Names=10-year,25-year,50-year,1pct_min,100-year,1pct_plu,500-year
River Rch & RM= Unnamed Tr to Wa,Reach-1,2744
     337     445     530     314     627    1250     875
Boundary for River Rch & Prof#=Unnamed Tr to Wa,Reach-1,1
Up Type=0
Dn Type=3
Dn Slope=0.005
Boundary for River Rch & Prof#=Unnamed Tr to Wa,Reach-1,2
Up Type=0
Dn Type=3
Dn Slope=0.005
Boundary for River Rch & Prof#=Unnamed Tr to Wa,Reach-1,3
Up Type=0
Dn Type=3
Dn Slope=0.005
Boundary for River Rch & Prof#=Unnamed Tr to Wa,Reach-1,4
Up Type=0
Dn Type=3
Dn Slope=0.005
Boundary for River Rch & Prof#=Unnamed Tr to Wa,Reach-1,5
Up Type=0
Dn Type=3
Dn Slope=0.005
Boundary for River Rch & Prof#=Unnamed Tr to Wa,Reach-1,6
Up Type=0
Dn Type=3
Dn Slope=0.005
Boundary for River Rch & Prof#=Unnamed Tr to Wa,Reach-1,7
Up Type=0
Dn Type=3
Dn Slope=0.005

--- Unnamed Tr to Walnut Cr 2D.g01 (geometry) ---

Geom Title=Existing Conditions

River Reach=Unnamed Tr to Wa,Reach-1
Reach XY= 30
      2313529.00      7041510.00      2313642.60      7041573.42
      2313701.87      7041683.83      2313820.15      7041753.05
      2313732.45      7041861.58      2313736.85      7041957.08
      2313877.52      7041956.48      2314072.88      7041767.74
      2314170.99      7041762.84      2314186.90      7041866.11
      2314270.82      7041953.96      2314284.87      7042012.28
      2314370.82      7042103.96      2314389.78      7042169.68
      2314571.14      7042353.83      2314586.86      7042466.17
      2314715.79      7042596.87      2314773.36      7042607.90
      2314828.99      7042567.59      2314889.44      7042608.62
      2315077.78      7042613.43      2315127.01      7042665.66
      2315136.62      7042806.93      2315323.55      7042812.18
      2315426.58      7042904.46      2315542.63      7042923.33
      2315584.67      7043004.33      2315635.08      7043018.14
      2315676.88      7043065.27      2315679.00      7043360.00

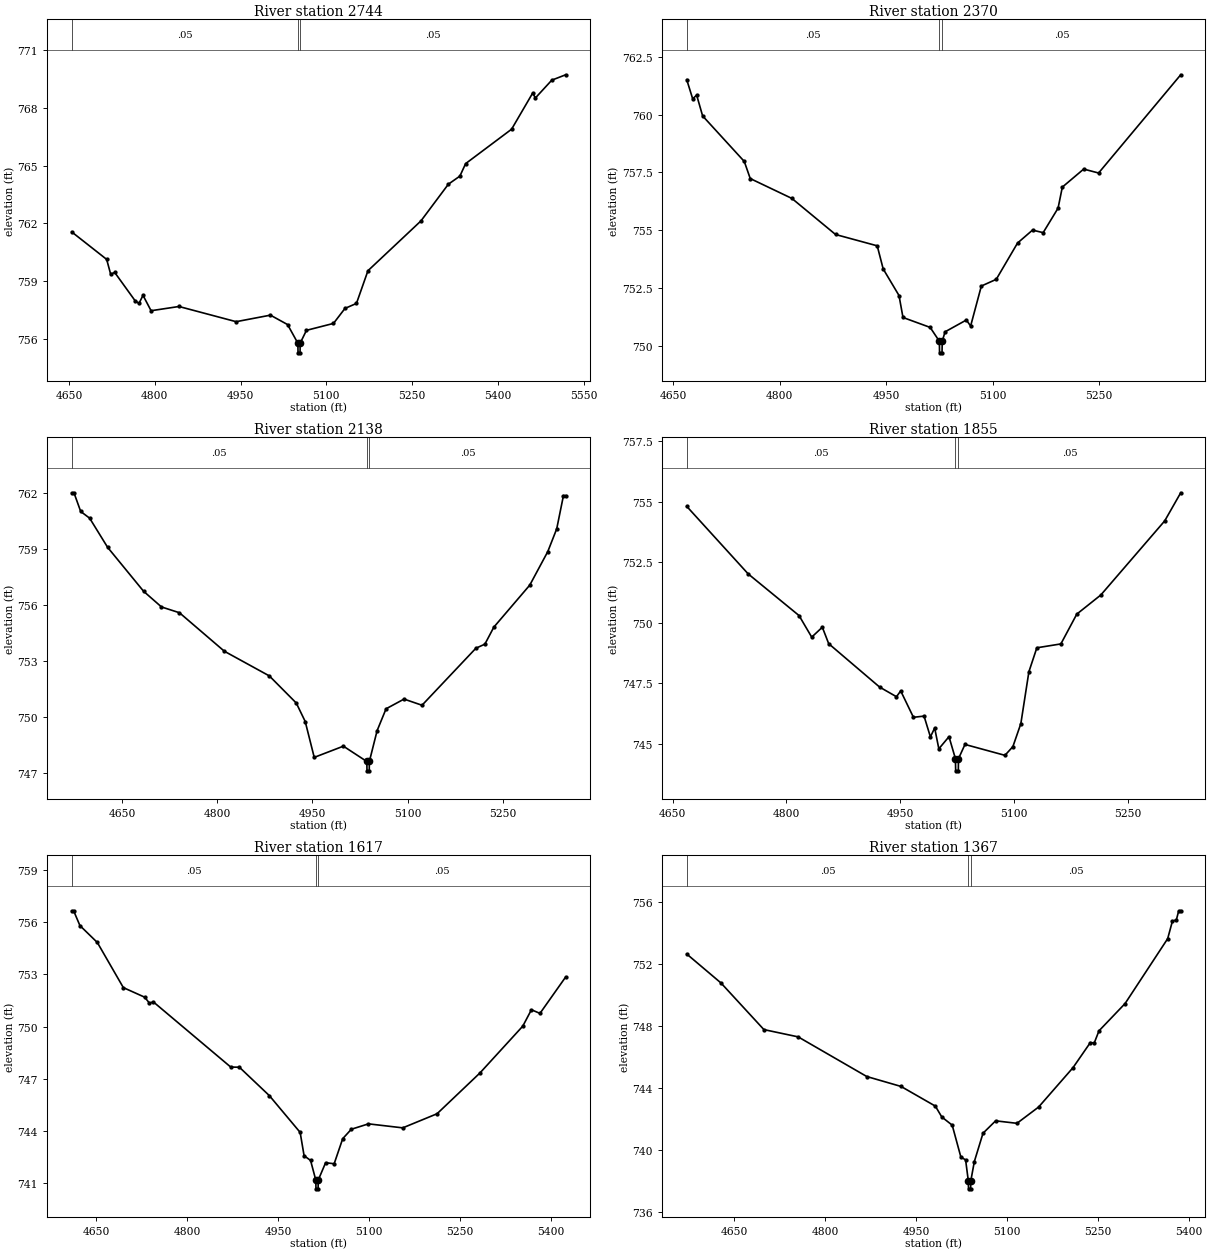
Type RM Length L Ch R = 1,2744,374,374,374
BEGIN DESCRIPTION:
Unnamed Tributary to Walnut Creek 2D 10.0
END DESCRIPTION:
XS GIS Cut Line= 4
      2313946.76      7042094.25      2314051.54      7041989.47
      2314044.40      7041733.09      2313998.36      7041275.86
#Sta/Elev= 30
  4654.6  761.56  4715.8  760.13  4722.8  759.36  4729.9  759.45  4765.3  757.99
  4772.3  757.84  4779.4  758.26  4793.5  757.46  4842.3  757.68  4942.3  756.89
  5002.3  757.23  5032.3  756.74  5050.3  755.77  5050.6  755.27  5054.1  755.27
  5054.3  755.77  5065.3  756.44  5112.6  756.80  5132.7  757.58  5152.8  757.84
  5172.9  759.54  5265.6  762.13  5313.6  764.04  5333.7  764.46  5343.8  765.11
  5424.2  766.90  5460.9  768.77  5466.0  768.53  5494.5  769.45  5518.8  769.73
#Mann=3,-1,0
  4654.6    0.05       0  5050.3   0.033       0  5054.3    0.05       0
Bank Sta=5050.3,5054.3
Exp/Cntr=0.3,0.1

Type RM Length L Ch R = 1,2370,232,232,232
BEGIN DESCRIPTION:
Unnamed Tributary to Walnut Creek 2D 9.0
END DESCRIPTION:
XS GIS Cut Line= 3
      2313978.97      7042110.02      2314279.00      7041960.00
      2314579.00      7041760.00
#Sta/Elev= 30
  4668.9  761.51  4677.3  760.68  4682.9  760.84  4691.3  759.94  4750.0  757.97
  4758.4  757.23  4817.1  756.37  4878.6  754.81  4937.3  754.32  4945.7  753.32
  4968.0  752.17  4973.6  751.22  5011.9  750.79  5024.9  750.19  5025.1  749.69
  5028.6  749.69  5028.9  750.19  5032.9  750.60  5062.9  751.11  5068.9  750.85
  5084.0  752.58  5105.0  752.87  5135.0  754.44  5156.1  755.00  5171.1  754.89
  5192.1  755.95  5198.1  756.86  5228.2  757.64  5249.2  757.47  5364.9  761.72
#Mann=3,-1,0
  4668.9    0.05       0  5024.9   0.033       0  5028.9    0.05       0
Bank Sta=5024.9,5028.9
Exp/Cntr=0.3,0.1

Type RM Length L Ch R = 1,2138,283,283,283
BEGIN DESCRIPTION:
Unnamed Tributary to Walnut Creek 2D 8.0
END DESCRIPTION:
XS GIS Cut Line= 3
      2314078.98      7042460.02      2314379.00      7042160.00
      2314628.97      7041910.03
#Sta/Elev= 30
  4570.9  762.00  4574.5  762.00  4585.1  761.00  4599.2  760.64  4627.5  759.08
  4684.1  756.73  4712.3  755.89  4740.6  755.58  4811.3  753.52  4882.1  752.20
  4924.5  750.75  4938.6  749.76  4952.8  747.84  4998.7  748.44  5035.6  747.62
  5035.9  747.12  5039.4  747.12  5039.6  747.62  5051.8  749.27  5065.9  750.44
  5094.2  750.96  5122.5  750.63  5207.3  753.68  5221.5  753.90  5235.6  754.81
  5292.2  757.06  5320.5  758.85  5334.6  760.07  5345.2  761.85  5348.7  761.85
#Mann=3,-1,0
  4570.9    0.05       0  5035.6   0.033       0  5039.6    0.05       0
Bank Sta=5035.6,5039.6
Exp/Cntr=0.3,0.1

Type RM Length L Ch R = 1,1855,238,238,238
BEGIN DESCRIPTION:
Unnamed Tributary to Walnut Creek 2D 7.0
END DESCRIPTION:
XS GIS Cut Line= 3
      2314278.97      7042510.01      2314579.00      7042360.00
      2314679.01      7042059.97
#Sta/Elev= 30
  4668.5  754.81  4749.6  752.02  4816.7  750.30  4833.4  749.41  4847.4  749.82
  4855.8  749.14  4922.9  747.35  4945.2  746.95  4950.8  747.19  4967.6  746.10
  4981.6  746.15  4990.0  745.29  4995.6  745.66  5001.1  744.80  5014.5  745.30
  5023.0  744.39  5023.3  743.89  5026.8  743.89  5027.0  744.39  5035.6  744.98
  5088.3  744.53  5098.8  744.89  5109.3  745.84  5119.9  747.98  5130.4  748.97
  5162.1  749.13  5183.1  750.36  5214.8  751.15  5299.1  754.21  5320.2  755.37
#Mann=3,-1,0
  4668.5    0.05       0  5023.0   0.033       0  5027.0    0.05       0
Bank Sta=5023,5027
Exp/Cntr=0.3,0.1

Type RM Length L Ch R = 1,1617,250,250,250
BEGIN DESCRIPTION:
Unnamed Tributary to Walnut Creek 2D 6.0
END DESCRIPTION:
XS GIS Cut Line= 3
      2314379.03      7042809.98      2314679.00      7042560.00
      2314978.97      7042260.03
#Sta/Elev= 30
  4609.8  756.65  4613.0  756.65  4623.4  755.80  4652.1  754.83  4695.0  752.24
  4730.2  751.69  4738.0  751.35  4744.5  751.42  4872.1  747.68  4886.4  747.67
  4935.8  746.04  4986.6  743.93  4993.1  742.59  5003.8  742.32  5012.4  741.19
  5012.7  740.69  5016.2  740.69  5016.4  741.19  5028.6  742.19  5042.7  742.13
  5056.8  743.57  5071.0  744.11  5099.3  744.42  5155.8  744.19  5212.4  745.00
  5283.1  747.34  5353.8  750.03  5368.0  750.97  5382.1  750.76  5424.5  752.85
#Mann=3,-1,0
  4609.8    0.05       0  5012.4   0.033       0  5016.4    0.05       0
Bank Sta=5012.4,5016.4
Exp/Cntr=0.3,0.1

Type RM Length L Ch R = 1,1367,267,267,267
BEGIN DESCRIPTION:
Unnamed Tributary to Walnut Creek 2D 5.0
END DESCRIPTION:
XS GIS Cut Line= 3
      2314579.01      7042909.99      2314879.00      7042610.00
      2315129.03      7042309.97
#Sta/Elev= 30
  4571.2  752.67  4627.7  750.80  4698.5  747.79  4755.0  747.32  4868.2  744.76
  4924.7  744.12  4981.3  742.85  4991.9  742.15  5009.1  741.62  5023.4  739.56
  5031.2  739.38  5035.7  738.01  5036.0  737.51  5039.5  737.51  5039.7  738.01
  5045.6  739.27  5059.9  741.10  5080.7  741.90  5115.9  741.74  5151.6  742.79
  5208.3  745.33  5236.9  746.95  5243.4  746.93  5251.2  747.71  5294.2  749.47
  5364.5  753.66  5372.3  754.79  5378.8  754.87  5382.7  755.46  5386.0  755.46
#Mann=3,-1,0
  4571.2    0.05       0  5035.7   0.033       0  5039.7    0.05       0
Bank Sta=5035.7,5039.7
Exp/Cntr=0.3,0.1

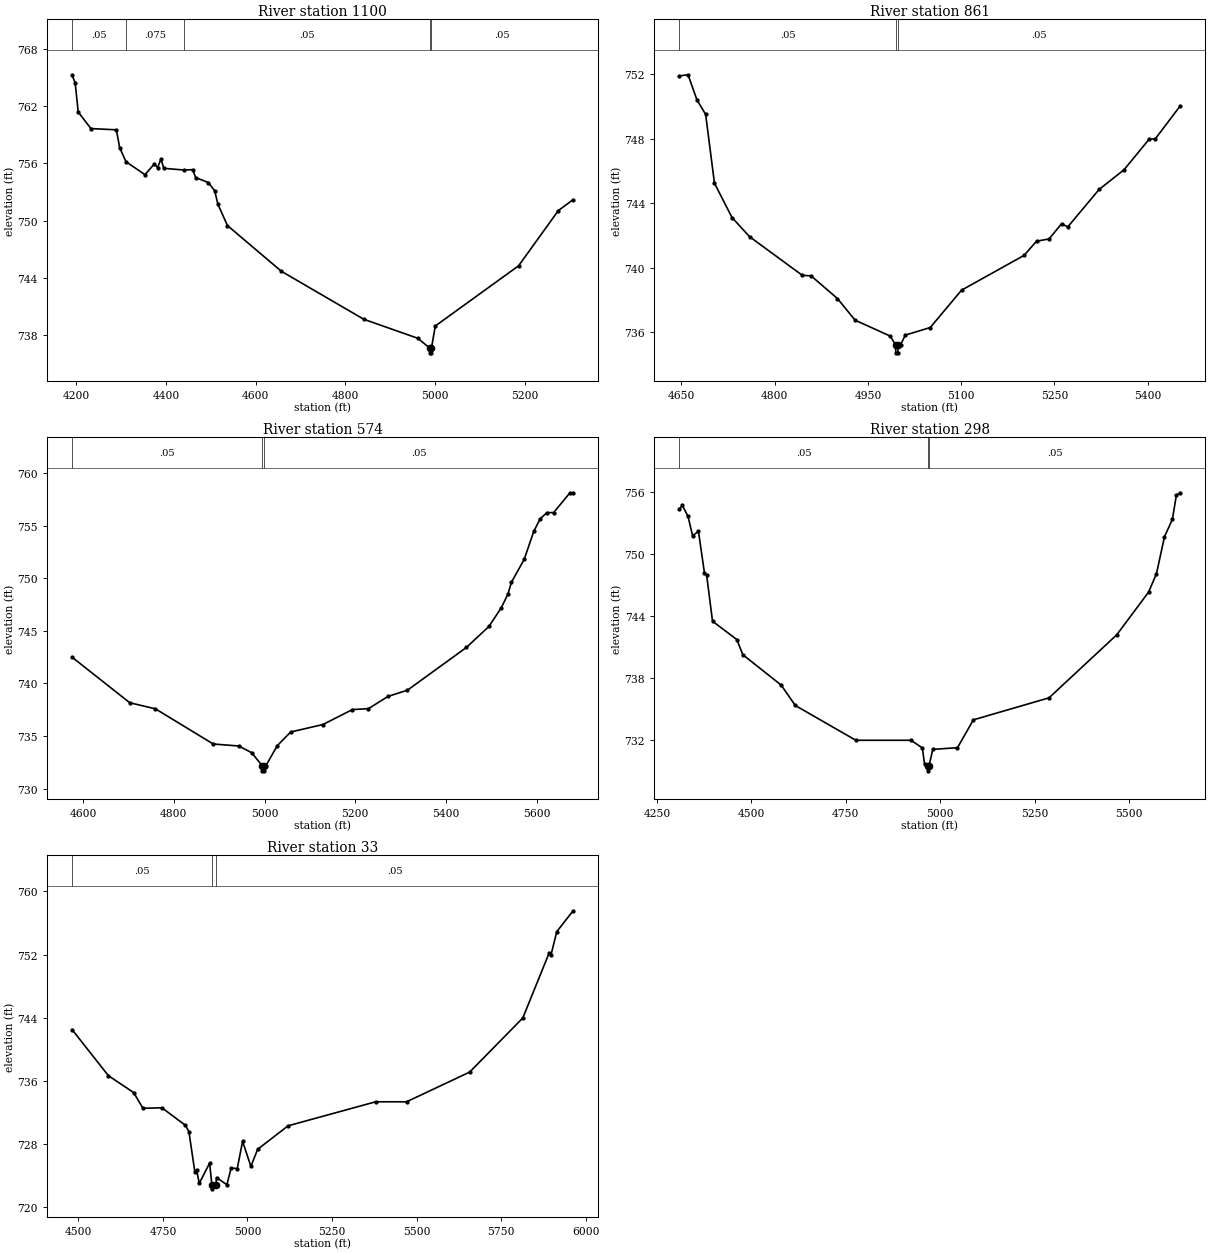
Type RM Length L Ch R = 1,1100,239,239,239
BEGIN DESCRIPTION:
Unnamed Tributary to Walnut Creek 2D 4.0
END DESCRIPTION:
XS GIS Cut Line= 3
      2314579.03      7043259.96      2315129.00      7042660.00
      2315179.00      7042360.03
#Sta/Elev= 30
  4190.3  765.28  4197.3  764.43  4204.1  761.38  4232.5  759.65  4289.2  759.52
  4296.6  757.65  4310.7  756.18  4353.0  754.83  4374.3  755.97  4381.1  755.55
  4388.5  756.45  4395.3  755.49  4440.4  755.31  4459.4  755.35  4466.2  754.52
  4494.6  754.00  4508.7  753.13  4515.8  751.72  4537.1  749.50  4657.3  744.72
  4841.4  739.69  4962.0  737.70  4988.3  736.68  4988.6  736.18  4992.1  736.18
  4992.3  736.68  5000.8  738.99  5186.7  745.29  5275.4  751.07  5308.3  752.21
#Mann=5,-1,0
  4190.3    0.05       0  4310.7   0.075       0  4440.4    0.05       0
  4988.3   0.033       0  4992.3    0.05       0
Bank Sta=4988.3,4992.3
Exp/Cntr=0.3,0.1

Type RM Length L Ch R = 1,861,287,287,287
BEGIN DESCRIPTION:
Unnamed Tributary to Walnut Creek 2D 3.0
END DESCRIPTION:
XS GIS Cut Line= 3
      2314979.01      7043059.99      2315229.00      7042810.00
      2315279.00      7042360.01
#Sta/Elev= 30
  4646.5  751.90  4660.6  751.97  4674.8  750.42  4688.9  749.51  4703.1  745.24
  4731.3  743.11  4759.6  741.92  4844.5  739.52  4858.6  739.49  4901.0  738.08
  4929.3  736.74  4985.9  735.75  4994.5  735.21  4994.8  734.71  4998.3  734.71
  4998.5  735.21  5002.6  735.21  5010.1  735.81  5050.3  736.28  5100.7  738.60
  5201.3  740.76  5221.4  741.64  5241.5  741.78  5261.6  742.72  5271.7  742.53
  5322.0  744.85  5362.3  746.08  5402.5  747.97  5412.6  748.00  5452.8  750.05
#Mann=3,-1,0
  4646.5    0.05       0  4994.5   0.033       0  4998.5    0.05       0
Bank Sta=4994.5,4998.5
Exp/Cntr=0.3,0.1

Type RM Length L Ch R = 1,574,276,276,276
BEGIN DESCRIPTION:
Unnamed Tributary to Walnut Creek 2D 2.0
END DESCRIPTION:
XS GIS Cut Line= 3
      2315178.97      7043210.03      2315479.00      7042910.00
      2315879.02      7042359.98
#Sta/Elev= 30
  4575.7  742.50  4703.0  738.17  4759.6  737.59  4886.9  734.25  4943.4  734.06
  4971.7  733.42  4994.5  732.20  4994.7  731.70  4998.2  731.70  4998.5  732.20
  5003.1  732.20  5028.2  734.10  5057.6  735.39  5128.7  736.10  5193.6  737.52
  5229.1  737.61  5272.0  738.77  5314.9  739.36  5444.8  743.42  5494.6  745.42
  5522.0  747.21  5536.7  748.52  5544.1  749.61  5572.3  751.79  5593.5  754.46
  5607.8  755.67  5622.5  756.23  5637.2  756.24  5672.7  758.09  5680.1  758.12
#Mann=3,-1,0
  4575.7    0.05       0  4994.5   0.033       0  4998.5    0.05       0
Bank Sta=4994.5,4998.5
Exp/Cntr=0.3,0.1

Type RM Length L Ch R = 1,298,265,265,265
BEGIN DESCRIPTION:
Unnamed Tributary to Walnut Creek 2D 1.0
END DESCRIPTION:
XS GIS Cut Line= 3
      2315079.04      7043409.98      2315679.00      7043060.00
      2315878.99      7042460.03
#Sta/Elev= 30
  4309.2  754.35  4317.0  754.75  4332.3  753.68  4344.3  751.81  4360.0  752.21
  4375.7  748.23  4381.5  748.03  4397.2  743.52  4461.7  741.74  4477.4  740.28
  4579.1  737.33  4616.4  735.36  4776.8  731.99  4922.7  731.99  4952.9  731.25
  4958.7  729.69  4966.6  729.53  4966.9  729.03  4970.6  729.53  4980.6  731.11
  5045.9  731.27  5088.1  733.97  5288.4  736.10  5467.6  742.20  5551.9  746.33
  5573.0  748.13  5594.1  751.70  5615.1  753.39  5625.7  755.74  5636.2  755.96
#Mann=3,-1,0
  4309.2    0.05       0  4966.6   0.033       0  4970.6    0.05       0
Bank Sta=4966.6,4970.6
Exp/Cntr=0.3,0.1

Type RM Length L Ch R = 1,33,0,0,0
BEGIN DESCRIPTION:
UNT WAL T2D 0.1
END DESCRIPTION:
XS GIS Cut Line= 5
      2315170.32      7043426.26      2315665.03      7043327.76
      2315724.59      7043326.66      2315832.99      7043094.93
      2315989.96      7042453.27
#Sta/Elev= 30
  4481.6  742.51  4588.9  736.68  4663.8  734.53  4691.1  732.55  4747.3  732.61
  4816.7  730.39  4826.9  729.60  4844.4  724.51  4849.5  724.79  4857.5  723.05
  4888.1  725.62  4894.8  722.86  4896.4  722.36  4906.4  722.86  4908.5  723.78
  4939.1  722.88  4951.7  725.00  4969.7  724.92  4985.5  728.37  5010.0  725.20
  5030.0  727.36  5119.8  730.33  5378.6  733.37  5470.0  733.37  5656.5  737.13
  5813.4  743.97  5891.5  752.22  5896.6  751.93  5913.9  754.90  5962.0  757.53
#Mann=3,-1,0
  4481.6    0.05       0  4894.8   0.033       0  4906.4    0.05       0
Bank Sta=4894.8,4906.4
Exp/Cntr=0.3,0.1

Chan Stop Cuts=-1