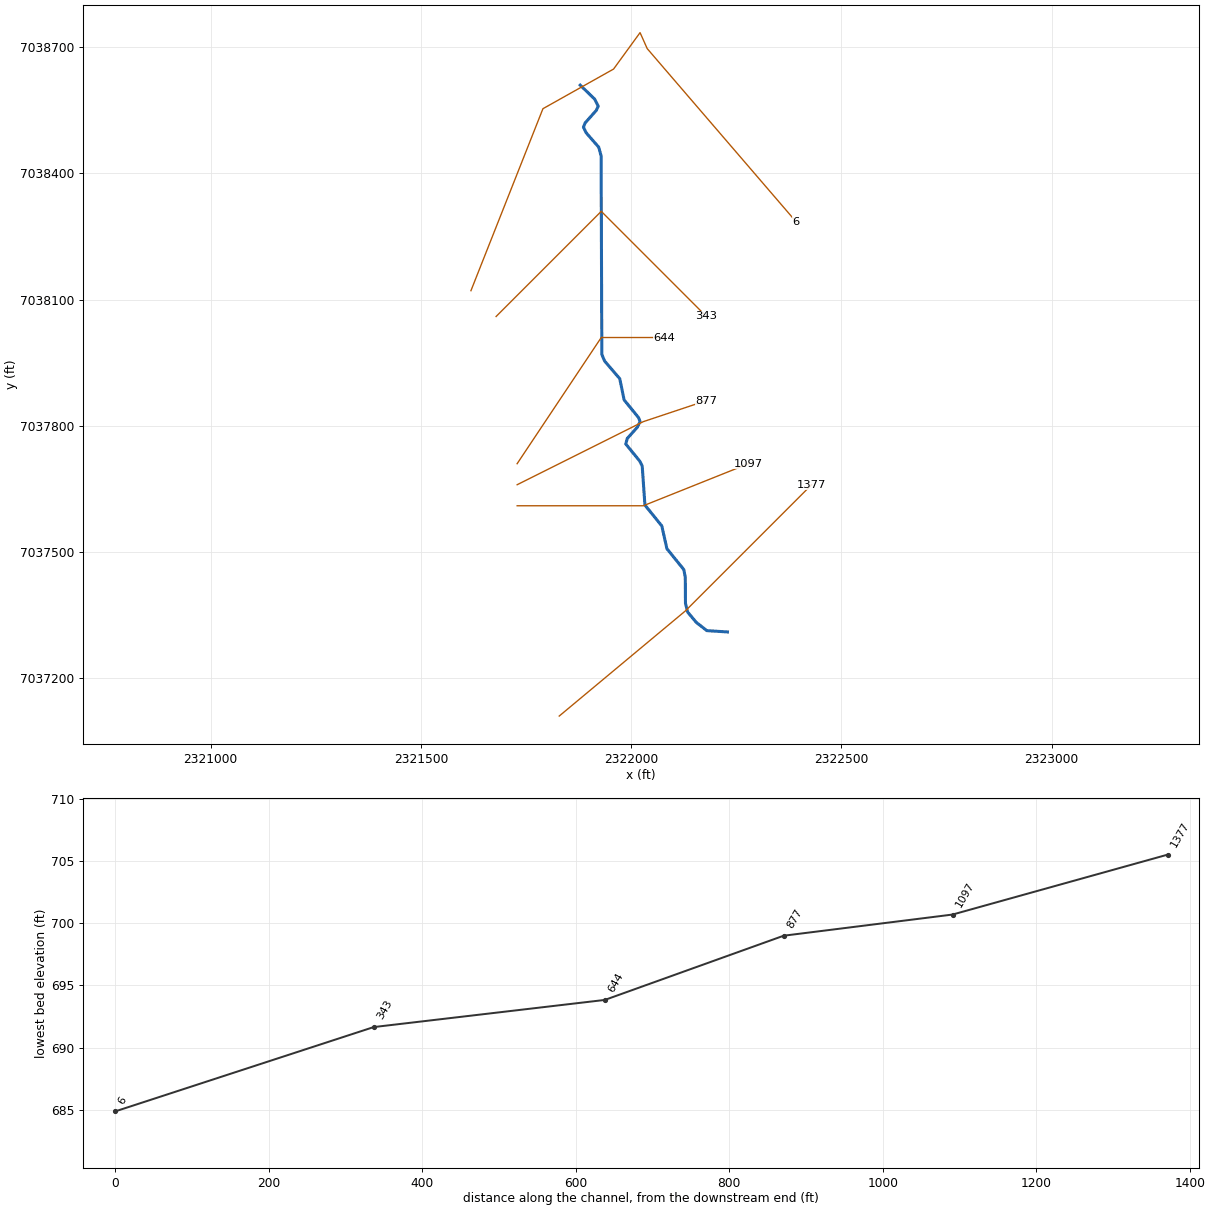
--- Unnamed Tr to Walnut Cr 2E.prj (project) ---

Proj Title=Unnamed Tr to Walnut Cr 2E Base Level Engineering
Current Plan=p01
Default Exp/Contr=0.3,0.1
English Units
Geom File=g01
Flow File=f01
Plan File=p01
BEGIN DESCRIPTION:
Unnamed Tr to Walnut Cr 2E
END DESCRIPTION:

--- Unnamed Tr to Walnut Cr 2E.p01 (plan) ---

Plan Title=Multiple Run
Short Identifier=Multiple
Geom File=g01
Flow File=f01
Subcritical Flow
K Sum by GR= 0
Std Step Tol= 0.01
Critical Tol= 0.01
Num of Std Step Trials= 20
Max Error Tol= 0.3
Flow Tol Ratio= 0.001
Split Flow NTrial= 30
Split Flow Tol= 0.02
Split Flow Ratio= 0.02
Log Output Level= 0
Friction Slope Method= 1
Unsteady Friction Slope Method= 2
Unsteady Bridges Friction Slope Method= 1
Parabolic Critical Depth
Global Vel Dist=  1 , 1 , 1
Global Log Level= 0
CheckData=True
Encroach Param= -1, 0, 0, 0
BEGIN DESCRIPTION:
Multiple Run
END DESCRIPTION:

--- Unnamed Tr to Walnut Cr 2E.f01 (steady flow) ---

Flow Title=Multiple
Number of Profiles=7
Profile Names=10-year,25-year,50-year,1pct_min,100-year,1pct_plu,500-year
River Rch & RM= Unnamed Tr to Wa,Reach-1,1377
     204     258     298     172     343     685     453
Boundary for River Rch & Prof#=Unnamed Tr to Wa,Reach-1,1
Up Type=0
Dn Type=3
Dn Slope=0.01
Boundary for River Rch & Prof#=Unnamed Tr to Wa,Reach-1,2
Up Type=0
Dn Type=3
Dn Slope=0.01
Boundary for River Rch & Prof#=Unnamed Tr to Wa,Reach-1,3
Up Type=0
Dn Type=3
Dn Slope=0.01
Boundary for River Rch & Prof#=Unnamed Tr to Wa,Reach-1,4
Up Type=0
Dn Type=3
Dn Slope=0.01
Boundary for River Rch & Prof#=Unnamed Tr to Wa,Reach-1,5
Up Type=0
Dn Type=3
Dn Slope=0.01
Boundary for River Rch & Prof#=Unnamed Tr to Wa,Reach-1,6
Up Type=0
Dn Type=3
Dn Slope=0.01
Boundary for River Rch & Prof#=Unnamed Tr to Wa,Reach-1,7
Up Type=0
Dn Type=3
Dn Slope=0.01

--- Unnamed Tr to Walnut Cr 2E.g01 (geometry) ---

Geom Title=Existing Conditions

River Reach=Unnamed Tr to Wa,Reach-1
Reach XY= 30
      2322229.00      7037310.00      2322179.99      7037313.12
      2322154.87      7037332.76      2322134.33      7037357.34
      2322129.20      7037378.20      2322128.77      7037439.90
      2322125.17      7037458.41      2322085.11      7037507.82
      2322072.89      7037562.18      2322032.82      7037611.59
      2322026.34      7037704.52      2322020.51      7037716.17
      2321987.28      7037756.78      2321990.83      7037770.05
      2322014.67      7037796.63      2322021.24      7037809.92
      2322017.44      7037819.87      2321983.41      7037861.63
      2321972.91      7037912.17      2321937.10      7037953.92
      2321930.36      7037969.65      2321928.67      7038441.78
      2321923.00      7038462.45      2321893.03      7038496.85
      2321886.64      7038510.11      2321890.57      7038520.06
      2321917.18      7038550.01      2321921.77      7038560.01
      2321913.31      7038576.78      2321879.00      7038610.00

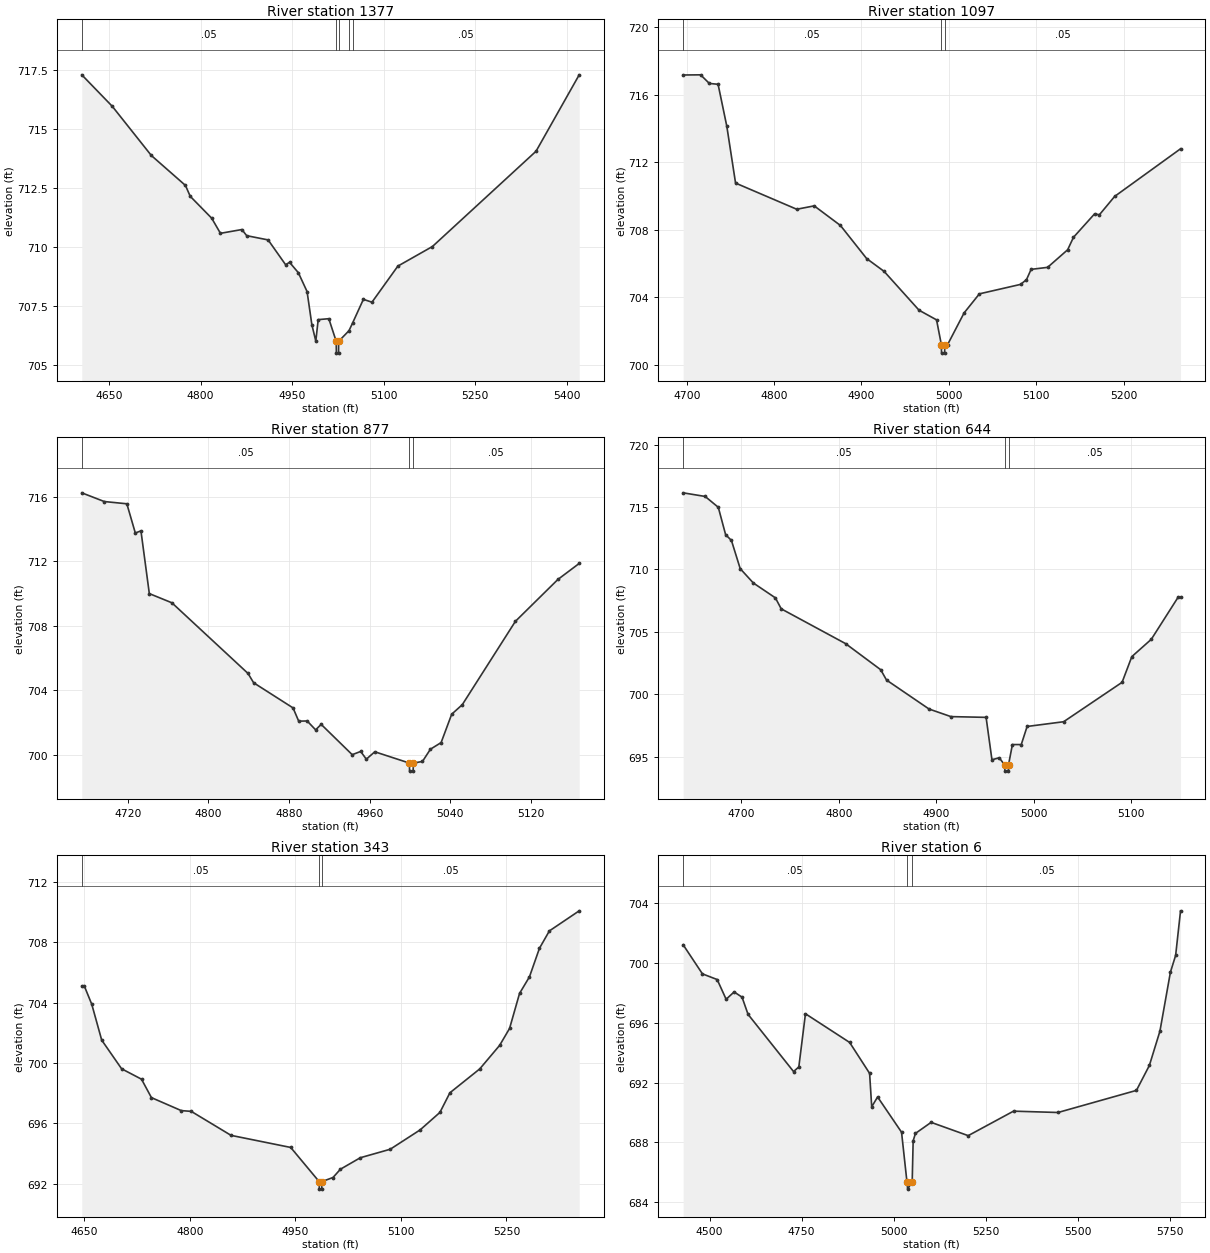
Type RM Length L Ch R = 1,1377,280,280,280
BEGIN DESCRIPTION:
Unnamed Tributary to Walnut Creek 2E 5.0
END DESCRIPTION:
XS GIS Cut Line= 3
      2321829.04      7037110.03      2322129.00      7037360.00
      2322428.98      7037659.98
#Sta/Elev= 30
  4605.4  717.30  4655.5  715.96  4719.3  713.88  4775.2  712.61  4783.0  712.15
  4818.2  711.22  4832.5  710.58  4867.6  710.74  4875.5  710.48  4910.6  710.30
  4939.2  709.25  4945.7  709.35  4960.1  708.91  4974.4  708.11  4982.2  706.71
  4988.7  706.01  4992.6  706.92  5010.0  706.96  5022.1  706.00  5022.4  705.50
  5025.9  705.50  5026.1  706.00  5043.0  706.45  5049.0  706.78  5066.6  707.78
  5080.7  707.66  5123.1  709.19  5179.7  710.02  5349.4  714.06  5420.1  717.30
#Mann=5,-1,0
  4605.4    0.05       0  5022.1   0.033       0  5026.1    0.05       0
  5043.0    0.12       0  5049.0    0.05       0
Bank Sta=5022.1,5026.1
Exp/Cntr=0.3,0.1

Type RM Length L Ch R = 1,1097,220,220,220
BEGIN DESCRIPTION:
Unnamed Tributary to Walnut Creek 2E 4.0
END DESCRIPTION:
XS GIS Cut Line= 3
      2321729.04      7037610.00      2322029.00      7037610.00
      2322278.99      7037709.99
#Sta/Elev= 30
  4695.9  717.16  4715.9  717.17  4725.9  716.66  4735.9  716.61  4745.9  714.12
  4755.9  710.76  4825.9  709.21  4845.9  709.41  4875.9  708.25  4905.9  706.29
  4925.9  705.53  4965.9  703.23  4985.9  702.66  4991.4  701.19  4991.6  700.69
  4995.1  700.69  4995.4  701.19  4998.5  701.19  5017.4  703.07  5034.9  704.20
  5082.0  704.76  5088.8  705.04  5094.1  705.65  5113.0  705.77  5135.9  706.81
  5142.6  707.55  5166.8  708.94  5172.2  708.88  5189.7  709.97  5265.1  712.79
#Mann=3,-1,0
  4695.9    0.05       0  4991.4   0.033       0  4995.4    0.05       0
Bank Sta=4991.4,4995.4
Exp/Cntr=0.3,0.1

Type RM Length L Ch R = 1,877,233,233,233
BEGIN DESCRIPTION:
Unnamed Tributary to Walnut Creek 2E 3.0
END DESCRIPTION:
XS GIS Cut Line= 3
      2321729.03      7037660.02      2322029.00      7037810.00
      2322179.01      7037860.00
#Sta/Elev= 30
  4674.4  716.25  4696.7  715.71  4719.1  715.57  4727.5  713.76  4733.1  713.89
  4741.4  710.00  4763.8  709.43  4839.3  705.05  4844.9  704.47  4884.0  702.91
  4889.6  702.09  4898.0  702.10  4906.4  701.55  4911.9  701.89  4942.7  700.01
  4951.1  700.21  4956.7  699.73  4965.1  700.19  4999.4  699.49  4999.6  698.99
  5003.1  698.99  5003.4  699.49  5012.4  699.59  5020.3  700.35  5030.9  700.76
  5041.4  702.52  5051.9  703.11  5104.6  708.28  5146.8  710.88  5167.9  711.87
#Mann=3,-1,0
  4674.4    0.05       0  4999.4   0.033       0  5003.4    0.05       0
Bank Sta=4999.4,5003.4
Exp/Cntr=0.3,0.1

Type RM Length L Ch R = 1,644,301,301,301
BEGIN DESCRIPTION:
Unnamed Tributary to Walnut Creek 2E 2.0
END DESCRIPTION:
XS GIS Cut Line= 3
      2321728.99      7037709.98      2321929.00      7038010.00
      2322079.03      7038010.00
#Sta/Elev= 30
  4640.1  716.14  4662.7  715.85  4676.2  714.98  4683.7  712.79  4689.7  712.32
  4698.7  710.06  4712.2  708.91  4734.8  707.72  4740.8  706.84  4806.9  704.05
  4842.9  701.96  4848.9  701.13  4892.5  698.81  4915.0  698.20  4951.1  698.14
  4957.1  694.74  4964.6  694.90  4970.1  694.33  4970.4  693.83  4973.9  693.83
  4974.1  694.33  4978.1  695.96  4987.2  695.96  4993.2  697.41  5030.7  697.79
  5090.7  700.95  5100.7  703.01  5120.7  704.40  5148.2  707.77  5150.7  707.77
#Mann=3,-1,0
  4640.1    0.05       0  4970.1   0.033       0  4974.1    0.05       0
Bank Sta=4970.1,4974.1
Exp/Cntr=0.3,0.1

Type RM Length L Ch R = 1,343,337,337,337
BEGIN DESCRIPTION:
Unnamed Tributary to Walnut Creek 2E 1.0
END DESCRIPTION:
XS GIS Cut Line= 3
      2321678.99      7038059.99      2321929.00      7038310.00
      2322178.98      7038060.02
#Sta/Elev= 30
  4646.4  705.10  4650.0  705.10  4660.6  703.89  4674.7  701.52  4703.0  699.62
  4731.3  698.93  4745.4  697.71  4787.8  696.85  4802.0  696.80  4858.6  695.21
  4943.4  694.41  4983.8  692.15  4984.1  691.65  4987.6  691.65  4987.8  692.15
  5003.5  692.42  5014.1  692.97  5042.4  693.73  5084.8  694.29  5127.3  695.57
  5155.5  696.73  5169.7  698.03  5212.1  699.61  5240.4  701.17  5254.5  702.29
  5268.7  704.61  5282.8  705.71  5297.0  707.60  5311.1  708.75  5353.5  710.08
#Mann=3,-1,0
  4646.4    0.05       0  4983.8   0.033       0  4987.8    0.05       0
Bank Sta=4983.8,4987.8
Exp/Cntr=0.3,0.1

Type RM Length L Ch R = 1,6,0,0,0
BEGIN DESCRIPTION:
UNT Walnut Ck 2D 0.5
END DESCRIPTION:
XS GIS Cut Line= 6
      2321619.16      7038121.29      2321790.34      7038553.99
      2321958.25      7038648.22      2322021.25      7038734.84
      2322038.31      7038696.78      2322392.54      7038284.83
#Sta/Elev= 30
  4428.3  701.23  4480.7  699.28  4520.7  698.90  4545.0  697.58  4566.7  698.07
  4588.2  697.72  4604.5  696.57  4728.0  692.74  4742.3  693.05  4760.3  696.61
  4880.2  694.69  4934.4  692.62  4940.1  690.38  4956.1  691.04  5021.1  688.68
  5035.7  685.37  5037.7  684.87  5050.0  685.37  5052.6  688.10  5058.8  688.60
  5101.4  689.34  5202.0  688.45  5325.0  690.09  5445.7  690.00  5658.6  691.48
  5693.7  693.15  5722.3  695.44  5750.8  699.39  5765.0  700.52  5778.3  703.50
#Mann=3,-1,0
  4428.3    0.05       0  5035.7   0.033       0  5050.0    0.05       0
Bank Sta=5035.7,5050
Exp/Cntr=0.3,0.1

Chan Stop Cuts=-1