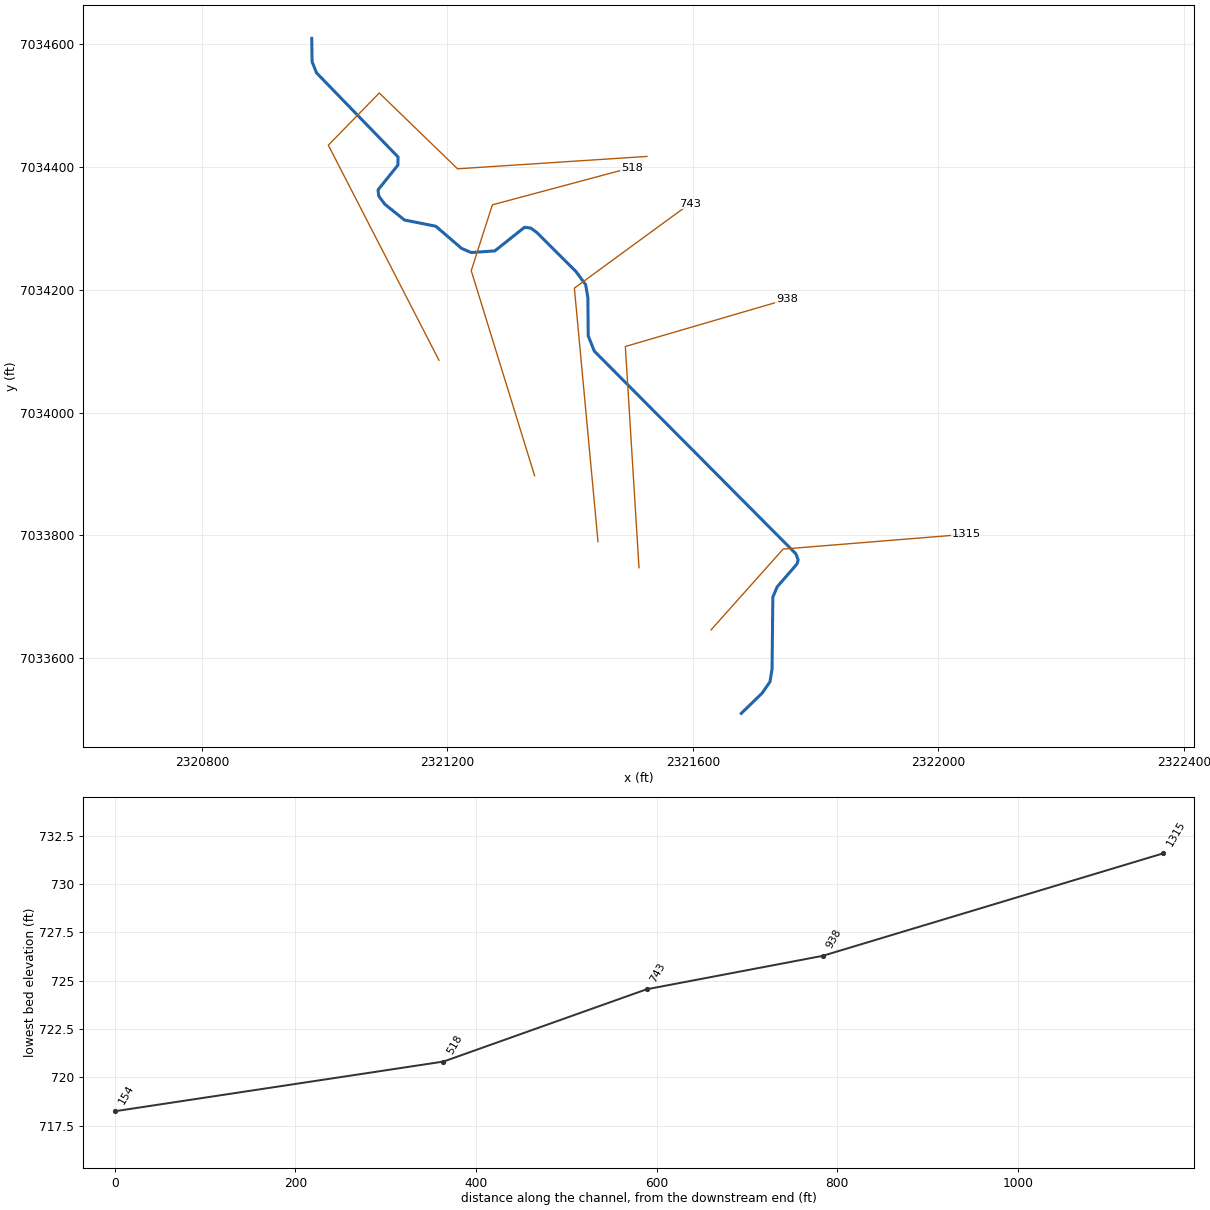
--- Unnamed Tr to Walnut Cr 2F.prj (project) ---

Proj Title=Unnamed Tr to Walnut Cr 2F Base Level Engineering
Current Plan=p01
Default Exp/Contr=0.3,0.1
English Units
Geom File=g01
Flow File=f01
Plan File=p01
BEGIN DESCRIPTION:
Unnamed Tr to Walnut Cr 2F
END DESCRIPTION:

--- Unnamed Tr to Walnut Cr 2F.p01 (plan) ---

Plan Title=Multiple Run
Short Identifier=Multiple
Geom File=g01
Flow File=f01
Subcritical Flow
K Sum by GR= 0
Std Step Tol= 0.01
Critical Tol= 0.01
Num of Std Step Trials= 20
Max Error Tol= 0.3
Flow Tol Ratio= 0.001
Split Flow NTrial= 30
Split Flow Tol= 0.02
Split Flow Ratio= 0.02
Log Output Level= 0
Friction Slope Method= 1
Unsteady Friction Slope Method= 2
Unsteady Bridges Friction Slope Method= 1
Parabolic Critical Depth
Global Vel Dist=  1 , 1 , 1
Global Log Level= 0
CheckData=True
Encroach Param= -1, 0, 0, 0
BEGIN DESCRIPTION:
Multiple Run
END DESCRIPTION:

--- Unnamed Tr to Walnut Cr 2F.f01 (steady flow) ---

Flow Title=Multiple
Number of Profiles=7
Profile Names=10-year,25-year,50-year,1pct_min,100-year,1pct_plu,500-year
River Rch & RM= Unnamed Tr to Wa,Reach-1,1315
     138     170     194     110     219     438     280
Boundary for River Rch & Prof#=Unnamed Tr to Wa,Reach-1,1
Up Type=0
Dn Type=3
Dn Slope=0.005
Boundary for River Rch & Prof#=Unnamed Tr to Wa,Reach-1,2
Up Type=0
Dn Type=3
Dn Slope=0.005
Boundary for River Rch & Prof#=Unnamed Tr to Wa,Reach-1,3
Up Type=0
Dn Type=3
Dn Slope=0.005
Boundary for River Rch & Prof#=Unnamed Tr to Wa,Reach-1,4
Up Type=0
Dn Type=3
Dn Slope=0.005
Boundary for River Rch & Prof#=Unnamed Tr to Wa,Reach-1,5
Up Type=0
Dn Type=3
Dn Slope=0.005
Boundary for River Rch & Prof#=Unnamed Tr to Wa,Reach-1,6
Up Type=0
Dn Type=3
Dn Slope=0.005
Boundary for River Rch & Prof#=Unnamed Tr to Wa,Reach-1,7
Up Type=0
Dn Type=3
Dn Slope=0.005

--- Unnamed Tr to Walnut Cr 2F.g01 (geometry) ---

Geom Title=Existing Conditions

River Reach=Unnamed Tr to Wa,Reach-1
Reach XY= 30
      2321679.00      7033510.00      2321712.91      7033542.94
      2321725.70      7033561.37      2321729.13      7033582.67
      2321730.40      7033699.56      2321737.48      7033716.19
      2321769.72      7033753.47      2321771.68      7033760.10
      2321767.90      7033770.06      2321439.52      7034100.21
      2321429.53      7034125.22      2321429.00      7034187.28
      2321425.39      7034208.53      2321409.37      7034230.24
      2321345.74      7034293.71      2321335.75      7034300.86
      2321325.78      7034302.09      2321277.37      7034263.62
      2321238.86      7034260.96      2321223.07      7034267.79
      2321181.14      7034303.82      2321130.17      7034313.94
      2321098.21      7034339.61      2321088.19      7034353.05
      2321087.08      7034363.15      2321119.38      7034403.32
      2321119.69      7034416.66      2320986.76      7034553.79
      2320979.59      7034571.84      2320979.00      7034610.00

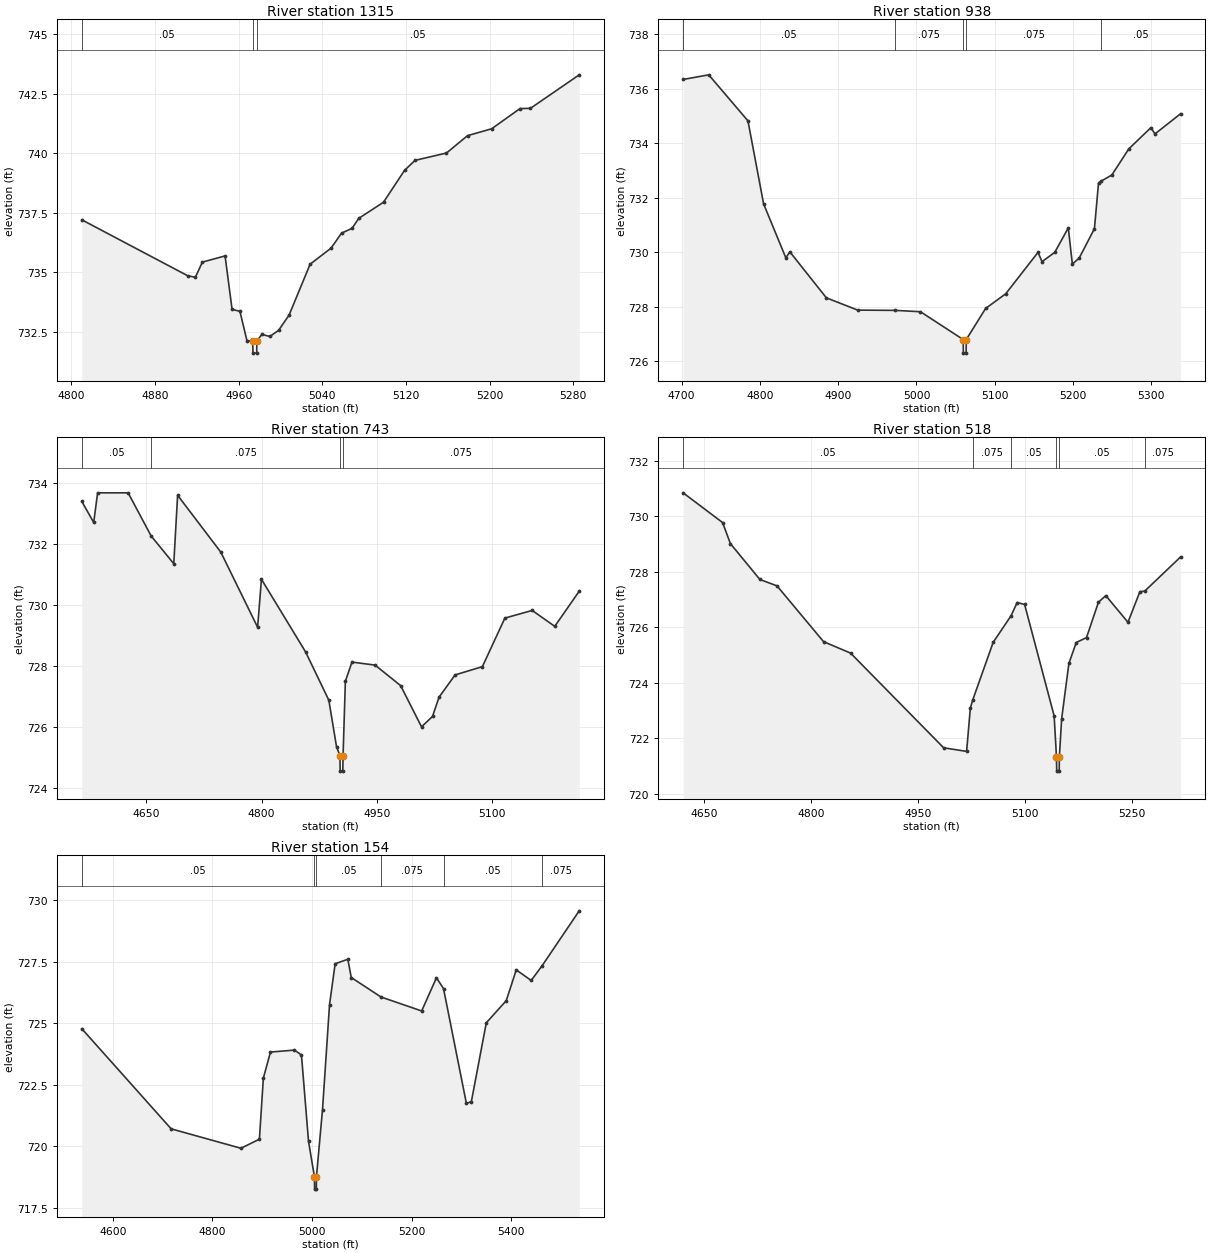
Type RM Length L Ch R = 1,1315,377,377,377
BEGIN DESCRIPTION:
UNT Walnut Ck 2F 6.0
END DESCRIPTION:
XS GIS Cut Line= 3
      2321629.78      7033646.14      2321747.21      7033777.74
      2322045.45      7033801.92
#Sta/Elev= 30
  4810.0  737.20  4911.1  734.85  4918.6  734.78  4925.3  735.42  4947.0  735.68
  4953.7  733.43  4961.2  733.35  4967.9  732.12  4973.4  732.09  4973.7  731.59
  4977.2  731.59  4977.4  732.09  4982.1  732.38  4989.8  732.29  4998.2  732.55
  5008.2  733.19  5028.3  735.33  5048.4  736.01  5058.4  736.64  5068.4  736.84
  5074.8  737.26  5098.5  737.94  5118.6  739.28  5128.6  739.70  5158.7  740.01
  5178.8  740.74  5201.9  741.03  5229.0  741.88  5239.0  741.89  5285.6  743.30
#Mann=3,-1,0
  4810.0    0.05       0  4973.4   0.033       0  4977.4    0.05       0
Bank Sta=4973.4,4977.4
Exp/Cntr=0.3,0.1

Type RM Length L Ch R = 1,938,195,195,195
BEGIN DESCRIPTION:
UNT Walnut Ck 2F 5.0
END DESCRIPTION:
XS GIS Cut Line= 3
      2321512.30      7033747.38      2321490.03      7034107.82
      2321753.29      7034184.77
#Sta/Elev= 30
  4701.9  736.34  4734.6  736.51  4784.7  734.82  4804.7  731.77  4833.1  729.79
  4838.2  730.01  4884.9  728.32  4924.9  727.87  4972.9  727.86  5005.1  727.81
  5059.6  726.79  5059.9  726.29  5063.4  726.29  5063.6  726.79  5088.3  727.93
  5114.0  728.47  5155.2  729.99  5160.4  729.65  5176.6  729.99  5193.9  730.89
  5199.1  729.56  5207.8  729.78  5227.3  730.86  5232.5  732.53  5235.4  732.60
  5249.5  732.83  5271.2  733.79  5299.4  734.57  5304.6  734.34  5337.3  735.08
#Mann=5,-1,0
  4701.9    0.05       0  4972.9   0.075       0  5059.6    0.07       0
  5063.6   0.075       0  5235.4    0.05       0
Bank Sta=5059.6,5063.6
Exp/Cntr=0.3,0.1

Type RM Length L Ch R = 1,743,225,225,225
BEGIN DESCRIPTION:
UNT Walnut Ck 2F 4.0
END DESCRIPTION:
XS GIS Cut Line= 3
      2321445.48      7033789.92      2321407.00      7034202.99
      2321594.63      7034340.18
#Sta/Elev= 30
  4566.1  733.39  4581.6  732.70  4586.7  733.67  4626.4  733.67  4656.3  732.26
  4685.8  731.35  4690.8  733.59  4747.0  731.73  4794.9  729.27  4799.9  730.84
  4857.4  728.46  4887.6  726.88  4897.6  725.36  4902.1  725.06  4902.3  724.56
  4905.8  724.56  4906.1  725.06  4909.1  727.50  4917.7  728.13  4947.8  728.03
  4981.0  727.36  5008.2  726.01  5022.5  726.35  5031.0  726.98  5051.9  727.71
  5087.4  727.98  5116.7  729.57  5152.2  729.82  5181.6  729.30  5213.4  730.45
#Mann=4,-1,0
  4566.1    0.05       0  4656.3   0.075       0  4902.1    0.07       0
  4906.1   0.075       0
Bank Sta=4902.1,4906.1
Exp/Cntr=0.3,0.1

Type RM Length L Ch R = 1,518,364,364,364
BEGIN DESCRIPTION:
UNT Walnut Ck 2F 3.0
END DESCRIPTION:
XS GIS Cut Line= 4
      2321342.21      7033897.18      2321238.93      7034231.34
      2321273.35      7034338.67      2321500.19      7034399.43
#Sta/Elev= 30
  4620.3  730.84  4675.6  729.77  4686.6  729.01  4727.9  727.72  4751.9  727.49
  4817.2  725.48  4855.0  725.07  4985.5  721.66  5017.7  721.53  5022.9  723.08
  5026.1  723.37  5055.0  725.46  5079.9  726.41  5088.6  726.89  5099.0  726.82
  5140.4  722.81  5143.7  721.32  5144.0  720.82  5147.5  720.82  5147.7  721.32
  5150.9  722.70  5161.1  724.70  5171.4  725.45  5185.8  725.63  5202.5  726.90
  5212.8  727.14  5243.9  726.18  5260.6  727.28  5267.3  727.30  5317.6  728.53
#Mann=6,-1,0
  4620.3    0.05       0  5026.1   0.075       0  5079.9    0.05       0
  5143.7   0.033       0  5147.7    0.05       0  5267.3   0.075       0
Bank Sta=5143.7,5147.7
Exp/Cntr=0.3,0.1

Type RM Length L Ch R = 1,154,0,0,0
BEGIN DESCRIPTION:
UNT Walnut Ck 2F 1.0
END DESCRIPTION:
XS GIS Cut Line= 5
      2321186.29      7034085.52      2321006.05      7034435.87
      2321089.08      7034520.92      2321216.65      7034397.39
      2321525.27      7034417.56
#Sta/Elev= 30
  4537.3  724.77  4716.9  720.70  4857.2  719.91  4894.3  720.28  4902.2  722.76
  4916.5  723.82  4964.7  723.90  4978.8  723.70  4993.0  720.19  5004.9  718.75
  5005.2  718.25  5008.7  718.25  5008.9  718.75  5021.1  721.48  5035.2  725.74
  5046.5  727.41  5072.0  727.59  5078.9  726.85  5138.5  726.06  5220.4  725.49
  5250.1  726.84  5264.3  726.40  5310.3  721.73  5320.3  721.81  5350.3  725.01
  5390.4  725.91  5410.5  727.16  5440.5  726.73  5462.5  727.33  5537.0  729.56
#Mann=6,-1,0
  4537.3    0.05       0  5004.9   0.033       0  5008.9    0.05       0
  5138.5   0.075       0  5264.3    0.05       0  5462.5   0.075       0
Bank Sta=5004.9,5008.9
Exp/Cntr=0.3,0.1

Chan Stop Cuts=-1