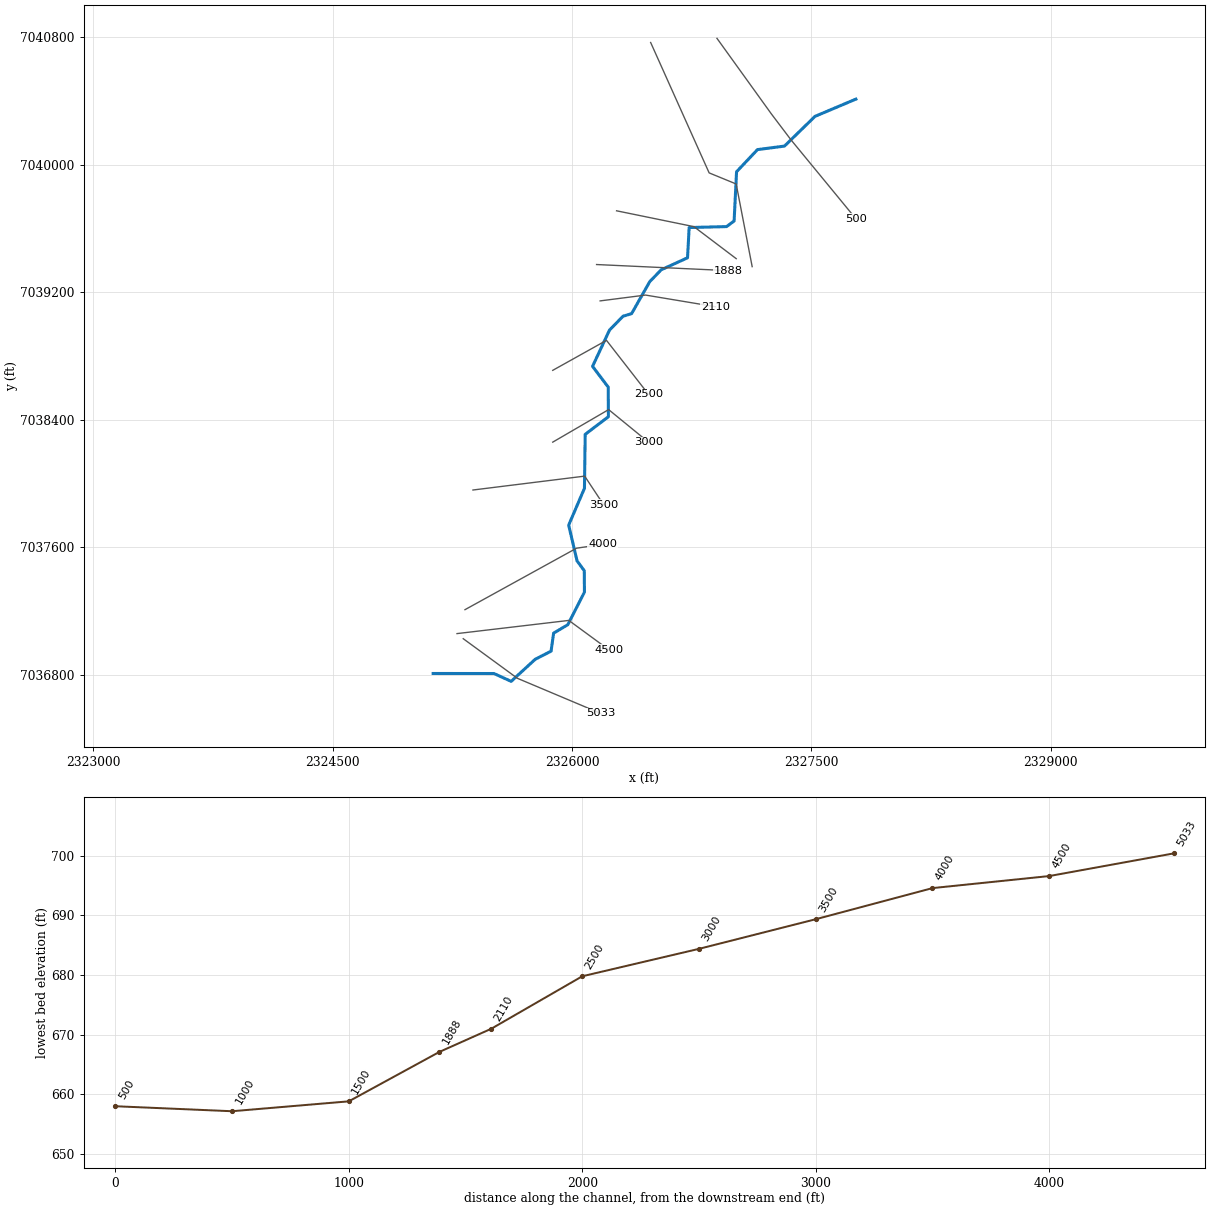
--- Unnamed Tr to Walnut Cr 2G.prj (project) ---

Proj Title=Unnamed Tr to Walnut Cr 2G Base Level Engineering
Current Plan=p01
Default Exp/Contr=0.3,0.1
English Units
Geom File=g01
Flow File=f01
Plan File=p01
BEGIN DESCRIPTION:
Unnamed Tr to Walnut Cr 2G
END DESCRIPTION:

--- Unnamed Tr to Walnut Cr 2G.p01 (plan) ---

Plan Title=Multiple Run
Short Identifier=Multiple
Geom File=g01
Flow File=f01
Subcritical Flow
K Sum by GR= 0
Std Step Tol= 0.01
Critical Tol= 0.01
Num of Std Step Trials= 20
Max Error Tol= 0.3
Flow Tol Ratio= 0.001
Split Flow NTrial= 30
Split Flow Tol= 0.02
Split Flow Ratio= 0.02
Log Output Level= 0
Friction Slope Method= 1
Unsteady Friction Slope Method= 2
Unsteady Bridges Friction Slope Method= 1
Parabolic Critical Depth
Global Vel Dist=  1 , 1 , 1
Global Log Level= 0
CheckData=True
Encroach Param= -1, 0, 0, 0
BEGIN DESCRIPTION:
Multiple Run
END DESCRIPTION:

--- Unnamed Tr to Walnut Cr 2G.f01 (steady flow) ---

Flow Title=Multiple
Number of Profiles=7
Profile Names=10-year,25-year,50-year,1pct_min,100-year,1pct_plu,500-year
River Rch & RM= Unnamed Tr to Wa,Reach-1,5033
     341     445     526     309     617    1230     846
Boundary for River Rch & Prof#=Unnamed Tr to Wa,Reach-1,1
Up Type=0
Dn Type=3
Dn Slope=0.005
Boundary for River Rch & Prof#=Unnamed Tr to Wa,Reach-1,2
Up Type=0
Dn Type=3
Dn Slope=0.005
Boundary for River Rch & Prof#=Unnamed Tr to Wa,Reach-1,3
Up Type=0
Dn Type=3
Dn Slope=0.005
Boundary for River Rch & Prof#=Unnamed Tr to Wa,Reach-1,4
Up Type=0
Dn Type=3
Dn Slope=0.005
Boundary for River Rch & Prof#=Unnamed Tr to Wa,Reach-1,5
Up Type=0
Dn Type=3
Dn Slope=0.005
Boundary for River Rch & Prof#=Unnamed Tr to Wa,Reach-1,6
Up Type=0
Dn Type=3
Dn Slope=0.005
Boundary for River Rch & Prof#=Unnamed Tr to Wa,Reach-1,7
Up Type=0
Dn Type=3
Dn Slope=0.005

--- Unnamed Tr to Walnut Cr 2G.g01 (geometry) ---

Geom Title=Existing Conditions

River Reach=Unnamed Tr to Wa,Reach-1
Reach XY= 30
      2325129.00      7036810.00      2325510.74      7036809.77
      2325618.38      7036760.60      2325769.34      7036899.21
      2325868.61      7036949.90      2325884.46      7037062.66
      2325973.38      7037115.62      2326077.65      7037319.66
      2326076.75      7037454.06      2326031.47      7037515.57
      2325978.90      7037739.90      2326077.78      7037970.50
      2326082.45      7038308.75      2326227.86      7038419.43
      2326226.82      7038604.55      2326128.50      7038734.97
      2326234.83      7038962.31      2326319.56      7039049.12
      2326373.38      7039065.62      2326487.15      7039266.07
      2326558.87      7039340.23      2326723.83      7039415.41
      2326734.00      7039605.00      2326968.74      7039610.98
      2327015.81      7039646.26      2327031.17      7039954.56
      2327162.23      7040093.57      2327331.45      7040115.47
      2327522.94      7040301.86      2327779.00      7040410.00

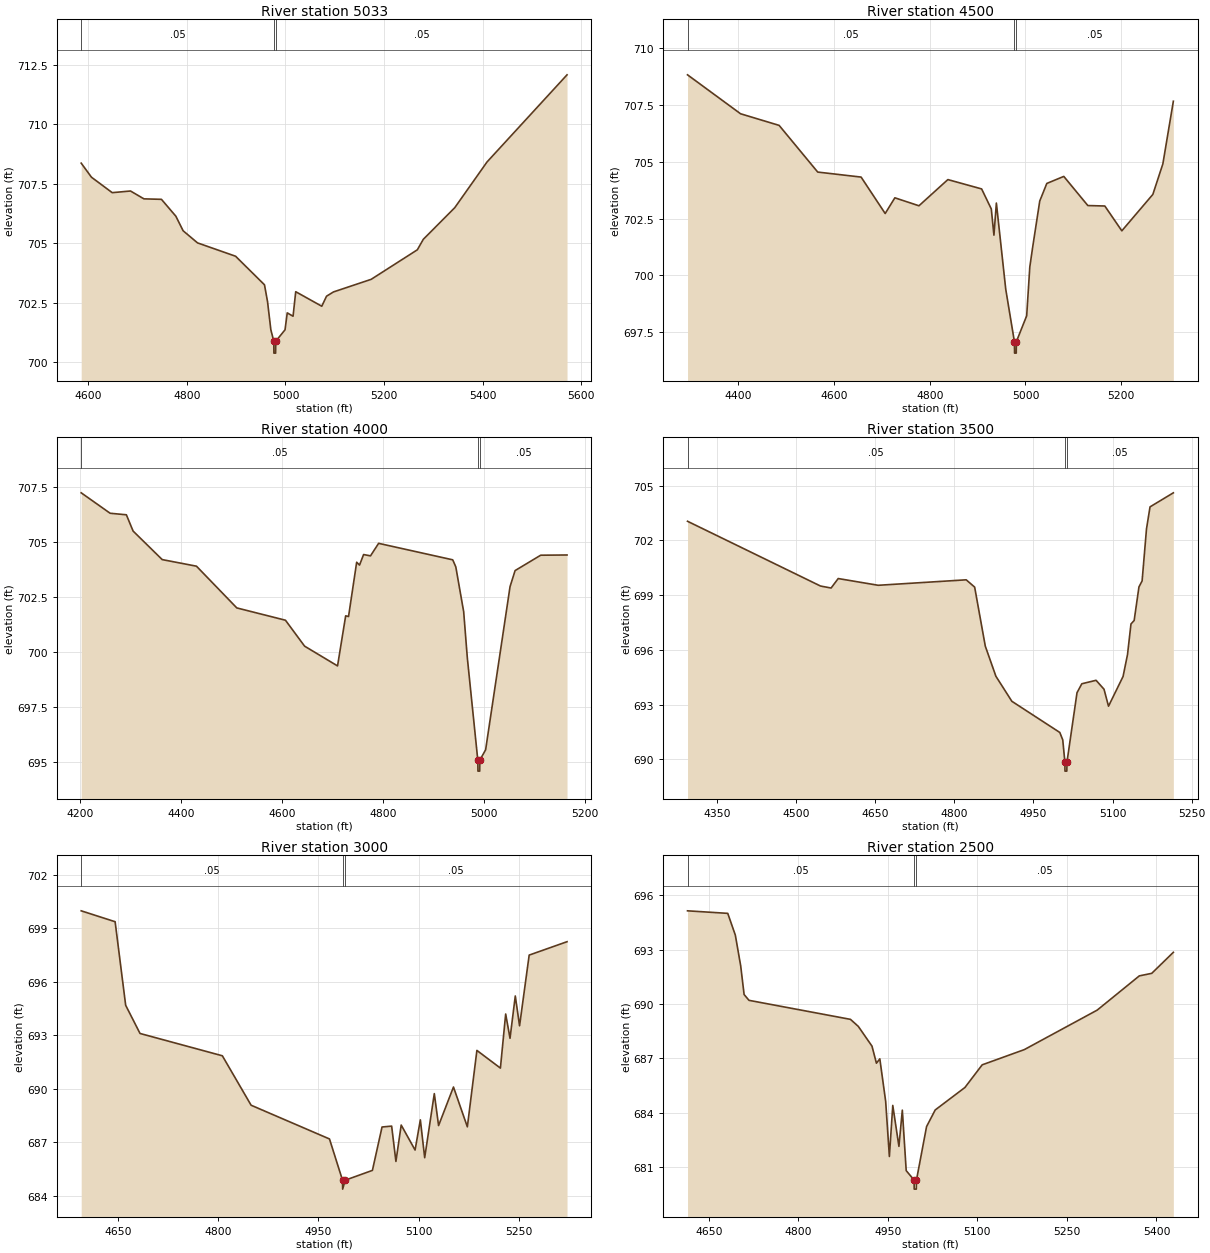
Type RM Length L Ch R = 1,5033,533,533,533
BEGIN DESCRIPTION:
Unnamed Tr to Walnut Cr 2G 10.0
END DESCRIPTION:
XS GIS Cut Line= 3
      2325318.18      7037027.96      2325657.69      7036779.71
      2326179.00      7036560.00
#Sta/Elev= 30
  4585.3  708.37  4606.1  707.78  4648.3  707.13  4685.4  707.20  4712.6  706.87
  4748.2  706.85  4777.5  706.14  4792.2  705.53  4821.5  705.02  4898.7  704.46
  4957.4  703.26  4963.6  702.55  4970.3  701.37  4976.3  700.89  4976.5  700.39
  4980.0  700.39  4980.3  700.89  4999.1  701.37  5003.6  702.08  5015.4  701.94
  5020.8  702.97  5073.7  702.36  5083.3  702.78  5097.4  702.96  5174.0  703.49
  5267.7  704.73  5279.8  705.17  5343.7  706.50  5409.2  708.42  5571.6  712.08
#Mann=3,-1,0
  4585.3    0.05       0  4976.3   0.033       0  4980.3    0.05       0
Bank Sta=4976.3,4980.3
Exp/Cntr=0.3,0.1

Type RM Length L Ch R = 1,4500,500,500,500
BEGIN DESCRIPTION:
Unnamed Tr to Walnut Cr 2G 9.0
END DESCRIPTION:
XS GIS Cut Line= 3
      2325279.01      7037060.00      2325979.95      7037142.65
      2326228.96      7036960.03
#Sta/Elev= 30
  4294.2  708.81  4405.0  707.10  4485.5  706.59  4566.1  704.54  4656.7  704.32
  4707.0  702.72  4727.2  703.41  4777.5  703.06  4837.9  704.21  4908.4  703.80
  4928.6  702.92  4934.1  701.77  4939.2  703.18  4958.8  699.39  4976.9  697.09
  4977.2  696.59  4980.7  696.59  4980.9  697.09  5002.5  698.23  5009.0  700.37
  5015.2  701.27  5029.8  703.27  5044.5  704.04  5080.0  704.35  5130.2  703.07
  5165.7  703.05  5201.2  701.96  5266.0  703.56  5286.9  704.90  5308.8  707.65
#Mann=3,-1,0
  4294.2    0.05       0  4976.9   0.035       0  4980.9    0.05       0
Bank Sta=4976.9,4980.9
Exp/Cntr=0.3,0.1

Type RM Length L Ch R = 1,4000,500,500,500
BEGIN DESCRIPTION:
Unnamed Tr to Walnut Cr 2G 8.0
END DESCRIPTION:
XS GIS Cut Line= 3
      2325328.98      7037209.99      2326028.26      7037595.28
      2326190.68      7037619.35
#Sta/Elev= 30
  4201.6  707.24  4258.9  706.31  4291.1  706.24  4304.4  705.50  4362.1  704.20
  4430.0  703.90  4509.9  702.00  4606.3  701.44  4644.2  700.26  4709.5  699.36
  4725.6  701.64  4731.3  701.61  4747.4  704.08  4753.1  703.95  4761.1  704.43
  4774.8  704.37  4790.9  704.94  4937.7  704.19  4943.8  703.87  4959.4  701.83
  4966.6  699.74  4987.4  695.07  4987.7  694.57  4991.2  694.57  4991.4  695.07
  5002.9  695.54  5051.3  702.97  5061.3  703.70  5112.0  704.40  5164.2  704.41
#Mann=3,-1,0
  4201.6    0.05       0  4987.4   0.035       0  4991.4    0.05       0
Bank Sta=4987.4,4991.4
Exp/Cntr=0.3,0.1

Type RM Length L Ch R = 1,3500,500,500,500
BEGIN DESCRIPTION:
Unnamed Tr to Walnut Cr 2G 7.0
END DESCRIPTION:
XS GIS Cut Line= 3
      2325378.95      7037959.99      2326079.17      7038046.99
      2326197.99      7037867.57
#Sta/Elev= 30
  4294.4  703.05  4546.4  699.50  4566.5  699.39  4580.0  699.91  4655.8  699.54
  4822.6  699.84  4838.6  699.44  4858.8  696.20  4878.9  694.55  4909.1  693.18
  5000.0  691.47  5005.6  691.06  5009.6  689.85  5009.8  689.35  5013.3  689.35
  5013.6  689.85  5032.6  693.65  5041.7  694.14  5068.7  694.33  5083.8  693.84
  5092.3  692.91  5119.9  694.54  5128.3  695.74  5134.9  697.42  5140.9  697.61
  5150.0  699.45  5156.0  699.78  5164.3  702.63  5171.0  703.84  5215.2  704.61
#Mann=3,-1,0
  4294.4    0.05       0  5009.6   0.033       0  5013.6    0.05       0
Bank Sta=5009.6,5013.6
Exp/Cntr=0.3,0.1

Type RM Length L Ch R = 1,3000,500,500,500
BEGIN DESCRIPTION:
Unnamed Tr to Walnut Cr 2G 6.0
END DESCRIPTION:
XS GIS Cut Line= 3
      2325879.03      7038260.02      2326229.41      7038463.94
      2326478.99      7038260.01
#Sta/Elev= 30
  4594.6  699.97  4645.4  699.36  4661.2  694.68  4682.7  693.10  4806.0  691.85
  4849.1  689.08  4966.5  687.19  4986.0  684.88  4986.2  684.38  4990.0  684.88
  5030.8  685.43  5045.2  687.86  5059.6  687.91  5066.0  685.93  5073.9  687.97
  5094.7  686.57  5102.6  688.26  5109.1  686.14  5123.5  689.73  5129.9  687.94
  5152.2  690.10  5173.0  687.87  5187.3  692.15  5222.5  691.16  5230.4  694.19
  5236.9  692.83  5244.8  695.20  5251.2  693.53  5265.6  697.49  5322.3  698.24
#Mann=3,-1,0
  4594.6    0.05       0  4986.0   0.033       0  4990.0    0.05       0
Bank Sta=4986,4990
Exp/Cntr=0.3,0.1

Type RM Length L Ch R = 1,2500,390,390,390
BEGIN DESCRIPTION:
Unnamed Tr to Walnut Cr 2G 5.0
END DESCRIPTION:
XS GIS Cut Line= 3
      2325879.04      7038710.02      2326215.86      7038897.96
      2326478.98      7038560.02
#Sta/Elev= 30
  4614.3  695.14  4681.7  695.00  4694.4  693.80  4703.4  692.10  4709.1  690.52
  4717.3  690.20  4887.3  689.15  4900.5  688.76  4923.4  687.67  4930.8  686.73
  4936.5  686.97  4946.3  684.62  4952.5  681.58  4958.2  684.40  4968.5  682.14
  4974.2  684.14  4980.7  680.80  4993.9  680.28  4994.1  679.78  4997.6  679.78
  4997.9  680.28  5014.8  683.23  5029.3  684.15  5079.1  685.39  5108.0  686.64
  5178.6  687.48  5300.7  689.66  5371.3  691.55  5392.1  691.69  5428.3  692.85
#Mann=3,-1,0
  4614.3    0.05       0  4993.9   0.033       0  4997.9    0.05       0
Bank Sta=4993.9,4997.9
Exp/Cntr=0.3,0.1

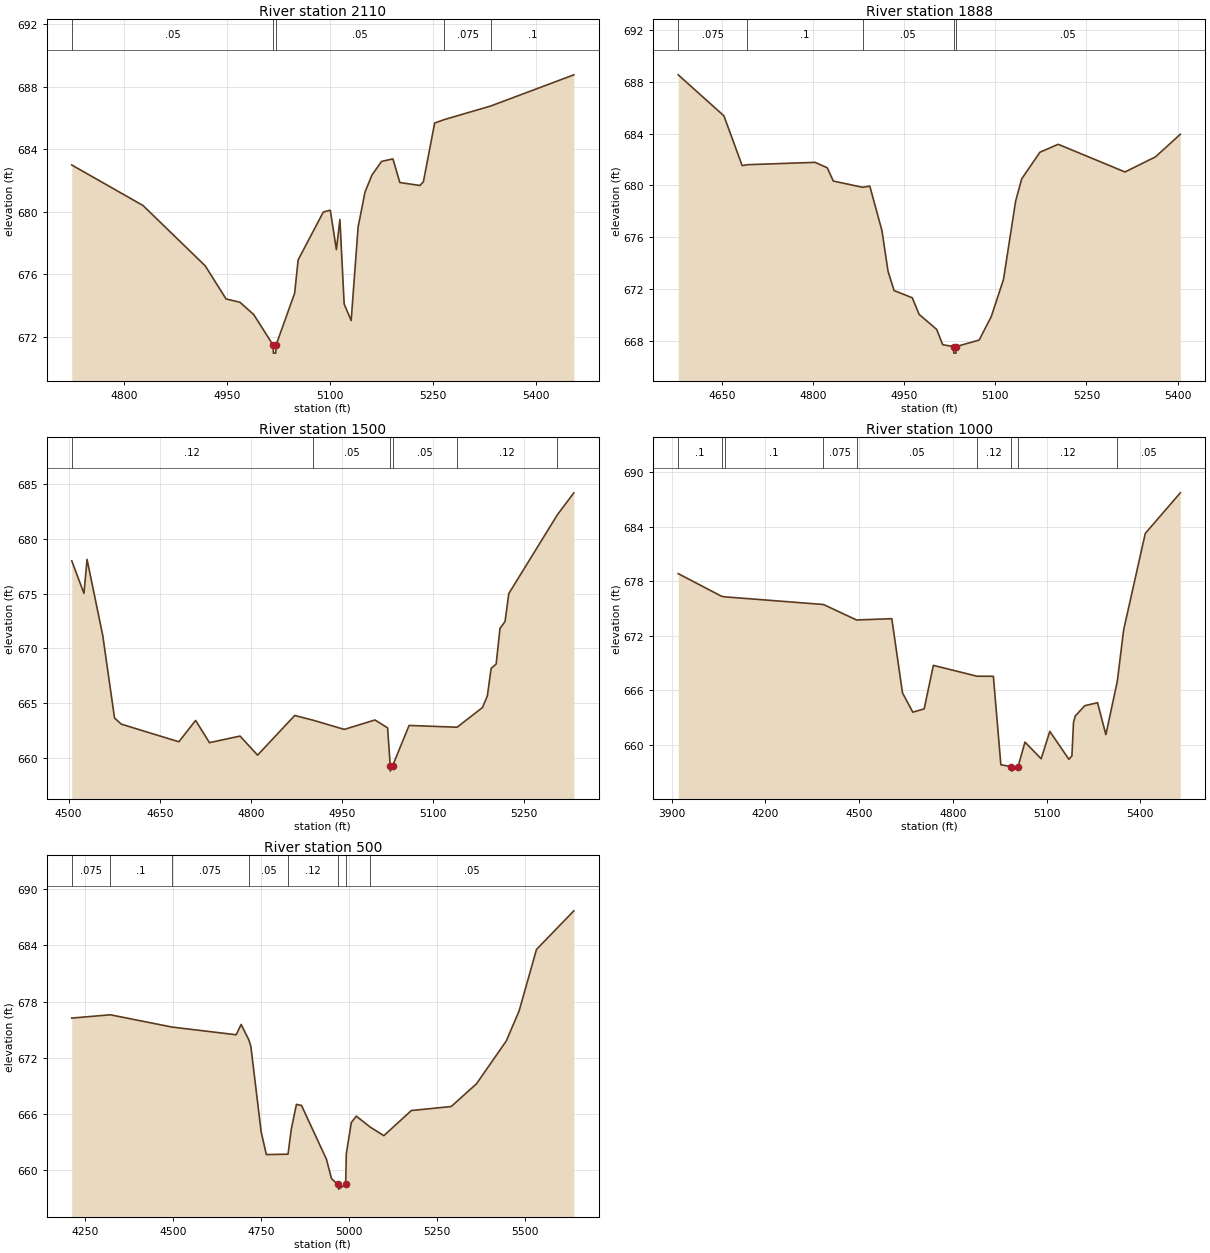
Type RM Length L Ch R = 1,2110,222,222,222
BEGIN DESCRIPTION:
Unnamed Tr to Walnut Cr 2G 4.0
END DESCRIPTION:
XS GIS Cut Line= 3
      2326176.09      7039145.30      2326460.82      7039181.81
      2326898.91      7039108.79
#Sta/Elev= 30
  4724.0  682.99  4827.8  680.40  4918.5  676.54  4948.7  674.43  4968.9  674.22
  4989.1  673.43  5017.4  671.47  5017.6  670.97  5021.1  670.97  5021.4  671.47
  5048.6  674.80  5053.7  676.93  5090.3  679.98  5100.5  680.10  5109.4  677.58
  5114.5  679.51  5120.7  674.11  5130.9  673.05  5141.0  679.02  5151.1  681.27
  5161.3  682.36  5175.3  683.22  5191.7  683.38  5201.8  681.87  5231.1  681.68
  5236.1  681.92  5252.5  685.67  5266.5  685.89  5334.3  686.76  5455.2  688.75
#Mann=5,-1,0
  4724.0    0.05       0  5017.4    0.05       0  5021.4    0.05       0
  5266.5   0.075       0  5334.3     0.1       0
Bank Sta=5017.4,5021.4
Exp/Cntr=0.3,0.1

Type RM Length L Ch R = 1,1888,388,388,388
BEGIN DESCRIPTION:
9998
END DESCRIPTION:
XS GIS Cut Line= 2
      2326153.77      7039373.18      2326979.99      7039334.93
#Sta/Elev= 30
  4577.5  688.52  4652.8  685.36  4682.8  681.53  4691.3  681.60  4803.0  681.78
  4823.0  681.36  4833.0  680.34  4881.2  679.86  4893.1  679.95  4913.1  676.52
  4923.1  673.40  4933.1  671.91  4963.1  671.35  4974.4  670.07  5003.2  668.92
  5013.2  667.74  5031.2  667.59  5031.5  667.09  5035.0  667.09  5035.2  667.59
  5073.3  668.10  5093.3  669.92  5113.3  672.76  5133.3  678.79  5143.3  680.51
  5173.4  682.56  5203.4  683.17  5313.5  681.04  5363.6  682.20  5404.6  683.94
#Mann=5,-1,0
  4577.5   0.075       0  4691.3     0.1       0  4881.2    0.05       0
  5031.2    0.05       0  5035.2    0.05       0
Bank Sta=5031.2,5035.2
Exp/Cntr=0.3,0.1

Type RM Length L Ch R = 1,1500,500,500,500
BEGIN DESCRIPTION:
Unnamed Tr to Walnut Cr 2G 3.0
END DESCRIPTION:
XS GIS Cut Line= 3
      2326279.05      7039709.99      2326763.88      7039610.66
      2327029.00      7039410.00
#Sta/Elev= 30
  4505.1  678.00  4525.2  675.03  4530.3  678.13  4556.1  671.20  4575.6  663.65
  4586.7  663.09  4681.6  661.48  4709.2  663.43  4732.0  661.40  4782.4  662.00
  4811.3  660.26  4872.5  663.88  4902.1  663.46  4954.2  662.61  5004.8  663.47
  5025.6  662.75  5029.9  659.30  5030.1  658.80  5033.9  659.30  5061.0  662.97
  5140.2  662.81  5182.0  664.61  5190.0  665.68  5196.2  668.18  5204.5  668.58
  5210.8  671.83  5219.1  672.46  5225.3  675.01  5305.4  682.21  5332.5  684.21
#Mann=6,-1,0
  4505.1    0.12       0  4902.1    0.05       0  5029.9   0.033       0
  5033.9    0.05       0  5140.2    0.12       0  5305.4    0.05       0
Bank Sta=5029.9,5033.9
Exp/Cntr=0.3,0.1

Type RM Length L Ch R = 1,1000,500,500,500
BEGIN DESCRIPTION:
Unnamed Tr to Walnut Cr 2G 2.0
END DESCRIPTION:
XS GIS Cut Line= 4
      2326492.71      7040764.88      2326859.31      7039947.56
      2327028.80      7039877.98      2327129.00      7039359.98
#Sta/Elev= 30
  3921.0  678.84  4059.8  676.35  4070.2  676.29  4385.6  675.45  4491.6  673.75
  4604.4  673.89  4638.7  665.73  4671.6  663.62  4708.0  663.98  4737.4  668.76
  4877.1  667.57  4929.4  667.56  4953.4  657.84  4986.4  657.64  4988.6  657.14
  5008.5  657.64  5030.5  660.33  5082.3  658.50  5110.0  661.51  5171.1  658.44
  5180.8  658.82  5185.8  662.50  5191.5  663.20  5222.0  664.33  5262.8  664.66
  5289.4  661.15  5326.0  667.01  5346.3  672.67  5415.5  683.26  5527.6  687.72
#Mann=9,-1,0
  3921.0     0.1       0  4059.8   0.075       0  4070.2     0.1       0
  4385.6   0.075       0  4491.6    0.05       0  4877.1    0.12       0
  4986.4    0.07       0  5008.5    0.12       0  5326.0    0.05       0
Bank Sta=4986.4,5008.5
Exp/Cntr=0.3,0.1

Type RM Length L Ch R = 1,500,0,0,0
BEGIN DESCRIPTION:
Unnamed Tr to Walnut Cr 2G 1.0
END DESCRIPTION:
XS GIS Cut Line= 4
      2326908.35      7040790.92      2327250.21      7040315.97
      2327373.14      7040153.65      2327779.01      7039659.98
#Sta/Elev= 30
  4211.2  676.24  4320.9  676.59  4496.6  675.28  4678.7  674.46  4692.9  675.56
  4714.5  673.94  4720.5  673.23  4749.9  664.08  4764.6  661.67  4826.2  661.71
  4835.5  664.38  4850.1  667.03  4864.6  666.91  4935.4  661.18  4949.9  659.10
  4968.0  658.48  4970.2  657.98  4990.1  658.48  4992.0  661.76  5006.3  665.10
  5020.6  665.77  5060.4  664.59  5098.8  663.69  5177.0  666.37  5290.4  666.80
  5362.1  669.22  5446.8  673.79  5483.4  677.00  5532.9  683.57  5639.1  687.69
#Mann=8,-1,0
  4211.2   0.075       0  4320.9     0.1       0  4496.6   0.075       0
  4714.5    0.05       0  4826.2    0.12       0  4968.0    0.07       0
  4990.1    0.12       0  5060.4    0.05       0
Bank Sta=4968,4990.1
Exp/Cntr=0.3,0.1

Chan Stop Cuts=-1