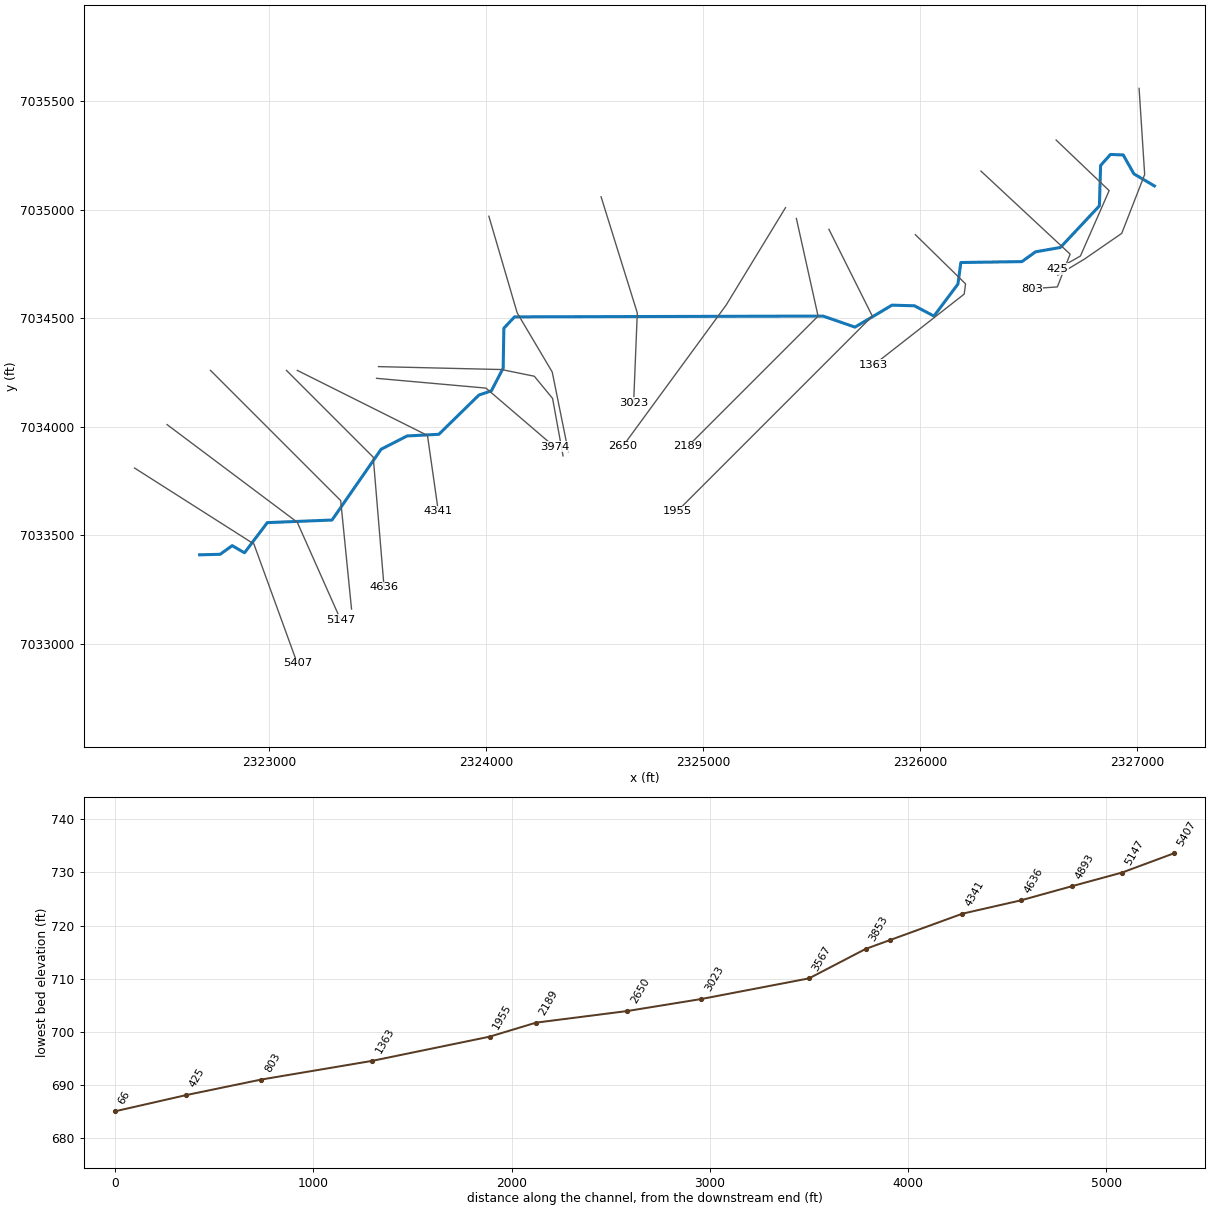
--- Unnamed Tr to Walnut Cr 2H.prj (project) ---

Proj Title=Unnamed Tr to Walnut Cr 2H Base Level Engineering
Current Plan=p01
Default Exp/Contr=0.3,0.1
English Units
Geom File=g01
Flow File=f01
Plan File=p01
BEGIN DESCRIPTION:
Unnamed Tr to Walnut Cr 2H
END DESCRIPTION:

--- Unnamed Tr to Walnut Cr 2H.p01 (plan) ---

Plan Title=Multiple Run
Short Identifier=Multiple
Geom File=g01
Flow File=f01
Subcritical Flow
K Sum by GR= 0
Std Step Tol= 0.01
Critical Tol= 0.01
Num of Std Step Trials= 20
Max Error Tol= 0.3
Flow Tol Ratio= 0.001
Split Flow NTrial= 30
Split Flow Tol= 0.02
Split Flow Ratio= 0.02
Log Output Level= 0
Friction Slope Method= 1
Unsteady Friction Slope Method= 2
Unsteady Bridges Friction Slope Method= 1
Parabolic Critical Depth
Global Vel Dist=  1 , 1 , 1
Global Log Level= 0
CheckData=True
Encroach Param= -1, 0, 0, 0
BEGIN DESCRIPTION:
Multiple Run
END DESCRIPTION:

--- Unnamed Tr to Walnut Cr 2H.f01 (steady flow) ---

Flow Title=Multiple
Number of Profiles=7
Profile Names=10-year,25-year,50-year,1pct_min,100-year,1pct_plu,500-year
River Rch & RM= Unnamed Tr to Wa,Reach-1,5407
     283     367     432     253     506    1010     689
Boundary for River Rch & Prof#=Unnamed Tr to Wa,Reach-1,1
Up Type=0
Dn Type=3
Dn Slope=0.005
Boundary for River Rch & Prof#=Unnamed Tr to Wa,Reach-1,2
Up Type=0
Dn Type=3
Dn Slope=0.005
Boundary for River Rch & Prof#=Unnamed Tr to Wa,Reach-1,3
Up Type=0
Dn Type=3
Dn Slope=0.005
Boundary for River Rch & Prof#=Unnamed Tr to Wa,Reach-1,4
Up Type=0
Dn Type=3
Dn Slope=0.005
Boundary for River Rch & Prof#=Unnamed Tr to Wa,Reach-1,5
Up Type=0
Dn Type=3
Dn Slope=0.005
Boundary for River Rch & Prof#=Unnamed Tr to Wa,Reach-1,6
Up Type=0
Dn Type=3
Dn Slope=0.005
Boundary for River Rch & Prof#=Unnamed Tr to Wa,Reach-1,7
Up Type=0
Dn Type=3
Dn Slope=0.005

--- Unnamed Tr to Walnut Cr 2H.g01 (geometry) ---

Geom Title=Existing Conditions

River Reach=Unnamed Tr to Wa,Reach-1
Reach XY= 30
      2322679.00      7033410.00      2322773.64      7033412.45
      2322829.10      7033452.24      2322885.69      7033419.29
      2322990.83      7033558.37      2323289.12      7033570.34
      2323515.43      7033896.53      2323634.93      7033957.75
      2323781.45      7033965.47      2323966.02      7034146.27
      2324023.41      7034165.61      2324077.81      7034270.48
      2324080.97      7034454.35      2324130.22      7034506.57
      2325551.85      7034510.28      2325699.08      7034459.33
      2325869.72      7034560.55      2325973.50      7034557.60
      2326062.99      7034510.23      2326173.44      7034657.64
      2326186.97      7034757.07      2326468.50      7034761.22
      2326530.60      7034806.14      2326645.75      7034826.46
      2326825.43      7035018.15      2326830.98      7035204.38
      2326876.45      7035255.06      2326935.29      7035252.62
      2326984.52      7035165.47      2327079.00      7035110.00

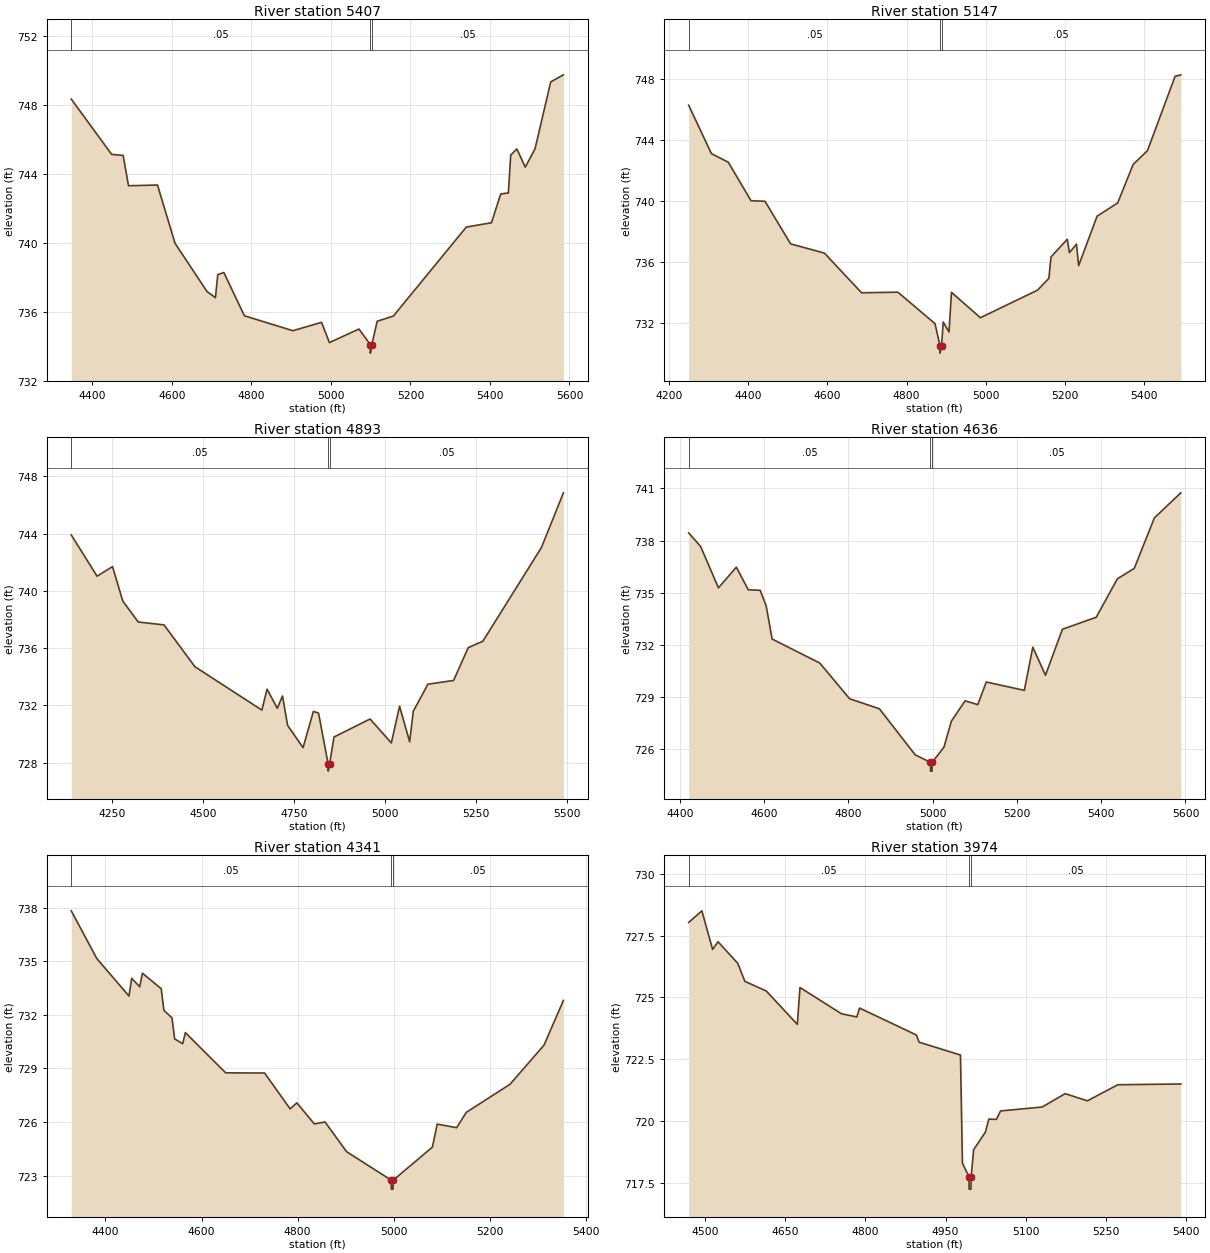
Type RM Length L Ch R = 1,5407,260,260,260
BEGIN DESCRIPTION:
Unnamed Tributary to Walnut Creek 2H 12.0
END DESCRIPTION:
XS GIS Cut Line= 3
      2322378.99      7033810.01      2322929.00      7033460.00
      2323129.01      7032909.97
#Sta/Elev= 30
  4347.5  748.34  4449.1  745.13  4477.9  745.07  4491.4  743.31  4564.3  743.35
  4608.3  739.97  4688.7  737.17  4709.9  736.81  4715.8  738.15  4731.1  738.27
  4782.7  735.76  4904.6  734.89  4976.6  735.38  4996.5  734.20  5070.6  734.99
  5099.2  734.09  5099.4  733.59  5103.2  734.09  5116.5  735.44  5157.1  735.74
  5340.6  740.91  5403.8  741.16  5427.1  742.83  5446.3  742.89  5452.3  745.09
  5467.6  745.45  5488.9  744.39  5513.5  745.46  5552.8  749.34  5584.7  749.75
#Mann=3,-1,0
  4347.5    0.05       0  5099.2    0.05       0  5103.2    0.05       0
Bank Sta=5099.2,5103.2
Exp/Cntr=0.3,0.1

Type RM Length L Ch R = 1,5147,254,254,254
BEGIN DESCRIPTION:
Unnamed Tributary to Walnut Creek 2H 11.0
END DESCRIPTION:
XS GIS Cut Line= 3
      2322528.99      7034010.00      2323129.00      7033560.00
      2323329.02      7033109.95
#Sta/Elev= 30
  4250.0  746.30  4307.3  743.12  4350.0  742.55  4407.3  740.02  4442.7  739.98
  4507.3  737.18  4592.7  736.57  4686.5  733.96  4778.1  734.00  4871.9  731.93
  4884.5  730.49  4884.7  729.99  4888.5  730.49  4892.7  732.04  4907.3  731.38
  4913.5  733.99  4986.5  732.32  5130.6  734.13  5159.4  734.91  5164.8  736.32
  5205.9  737.48  5211.3  736.60  5229.1  737.16  5234.6  735.75  5281.1  739.00
  5333.1  739.87  5372.1  742.40  5408.3  743.31  5478.1  748.20  5492.5  748.30
#Mann=3,-1,0
  4250.0    0.05       0  4884.5    0.05       0  4888.5    0.05       0
Bank Sta=4884.5,4888.5
Exp/Cntr=0.3,0.1

Type RM Length L Ch R = 1,4893,257,257,257
BEGIN DESCRIPTION:
Unnamed Tributary to Walnut Creek 2H 10.0
END DESCRIPTION:
XS GIS Cut Line= 3
      2322728.96      7034260.04      2323329.00      7033660.00
      2323379.00      7033159.97
#Sta/Elev= 30
  4138.6  743.90  4209.4  741.02  4251.8  741.69  4280.1  739.28  4322.5  737.82
  4393.2  737.62  4478.1  734.70  4661.9  731.67  4676.1  733.13  4704.3  731.80
  4718.5  732.66  4732.6  730.60  4775.0  729.05  4803.3  731.58  4817.5  731.46
  4843.8  727.91  4844.0  727.41  4847.8  727.91  4859.9  729.79  4958.9  731.05
  5017.3  729.38  5039.9  731.94  5067.6  729.46  5077.6  731.59  5117.8  733.48
  5188.2  733.74  5228.4  736.03  5268.6  736.48  5429.4  743.02  5489.7  746.84
#Mann=3,-1,0
  4138.6    0.05       0  4843.8    0.05       0  4847.8    0.05       0
Bank Sta=4843.8,4847.8
Exp/Cntr=0.3,0.1

Type RM Length L Ch R = 1,4636,295,295,295
BEGIN DESCRIPTION:
Unnamed Tributary to Walnut Creek 2H 9.0
END DESCRIPTION:
XS GIS Cut Line= 3
      2323078.99      7034260.01      2323479.00      7033860.00
      2323529.00      7033259.98
#Sta/Elev= 30
  4421.1  738.44  4449.4  737.66  4491.8  735.28  4534.2  736.47  4562.5  735.17
  4590.8  735.14  4605.0  734.25  4619.1  732.34  4732.2  730.96  4802.9  728.91
  4873.7  728.33  4958.5  725.69  4994.8  725.25  4995.1  724.75  4998.6  724.75
  4998.8  725.25  5026.9  726.13  5044.5  727.62  5077.1  728.79  5107.2  728.57
  5127.3  729.87  5217.6  729.39  5237.7  731.87  5267.8  730.26  5307.9  732.90
  5388.2  733.59  5438.4  735.80  5478.5  736.40  5526.2  739.30  5588.9  740.74
#Mann=3,-1,0
  4421.1    0.05       0  4994.8   0.033       0  4998.8    0.05       0
Bank Sta=4994.8,4998.8
Exp/Cntr=0.3,0.1

Type RM Length L Ch R = 1,4341,367,367,367
BEGIN DESCRIPTION:
Unnamed Tributary to Walnut Creek 2H 8.0
END DESCRIPTION:
XS GIS Cut Line= 3
      2323129.04      7034259.98      2323729.00      7033960.00
      2323779.00      7033610.03
#Sta/Elev= 30
  4328.9  737.82  4382.0  735.15  4449.0  733.05  4454.6  734.04  4471.4  733.57
  4477.0  734.33  4516.1  733.46  4521.7  732.25  4538.5  731.83  4544.1  730.65
  4560.8  730.38  4566.4  731.00  4650.3  728.75  4731.3  728.74  4784.5  726.73
  4798.4  727.07  4834.8  725.89  4857.1  726.00  4901.8  724.34  4994.9  722.74
  4995.1  722.24  4998.6  722.24  4998.9  722.74  5080.5  724.59  5090.6  725.88
  5131.0  725.68  5151.2  726.54  5242.1  728.11  5312.8  730.30  5353.2  732.80
#Mann=3,-1,0
  4328.9    0.05       0  4994.9   0.033       0  4998.9    0.05       0
Bank Sta=4994.9,4998.9
Exp/Cntr=0.3,0.1

Type RM Length L Ch R = 1,3974,121,121,121
BEGIN DESCRIPTION:
Unnamed Tributary to Walnut Creek 2H 7.0
END DESCRIPTION:
XS GIS Cut Line= 3
      2323494.35      7034223.33      2323998.37      7034178.33
      2324313.37      7033908.33
#Sta/Elev= 30
  4469.2  728.03  4493.9  728.50  4514.0  726.94  4524.1  727.25  4561.0  726.38
  4574.3  725.65  4614.4  725.26  4672.5  723.91  4677.5  725.40  4755.0  724.34
  4783.9  724.21  4788.9  724.57  4895.4  723.48  4900.4  723.19  4977.8  722.67
  4981.5  718.30  4993.8  717.75  4994.0  717.25  4997.5  717.25  4997.8  717.75
  5002.4  718.84  5024.3  719.55  5030.9  720.08  5045.1  720.07  5052.8  720.41
  5130.8  720.57  5173.6  721.11  5215.3  720.82  5272.3  721.47  5390.1  721.50
#Mann=3,-1,0
  4469.2    0.05       0  4993.8    0.05       0  4997.8    0.05       0
Bank Sta=4993.8,4997.8
Exp/Cntr=0.3,0.1

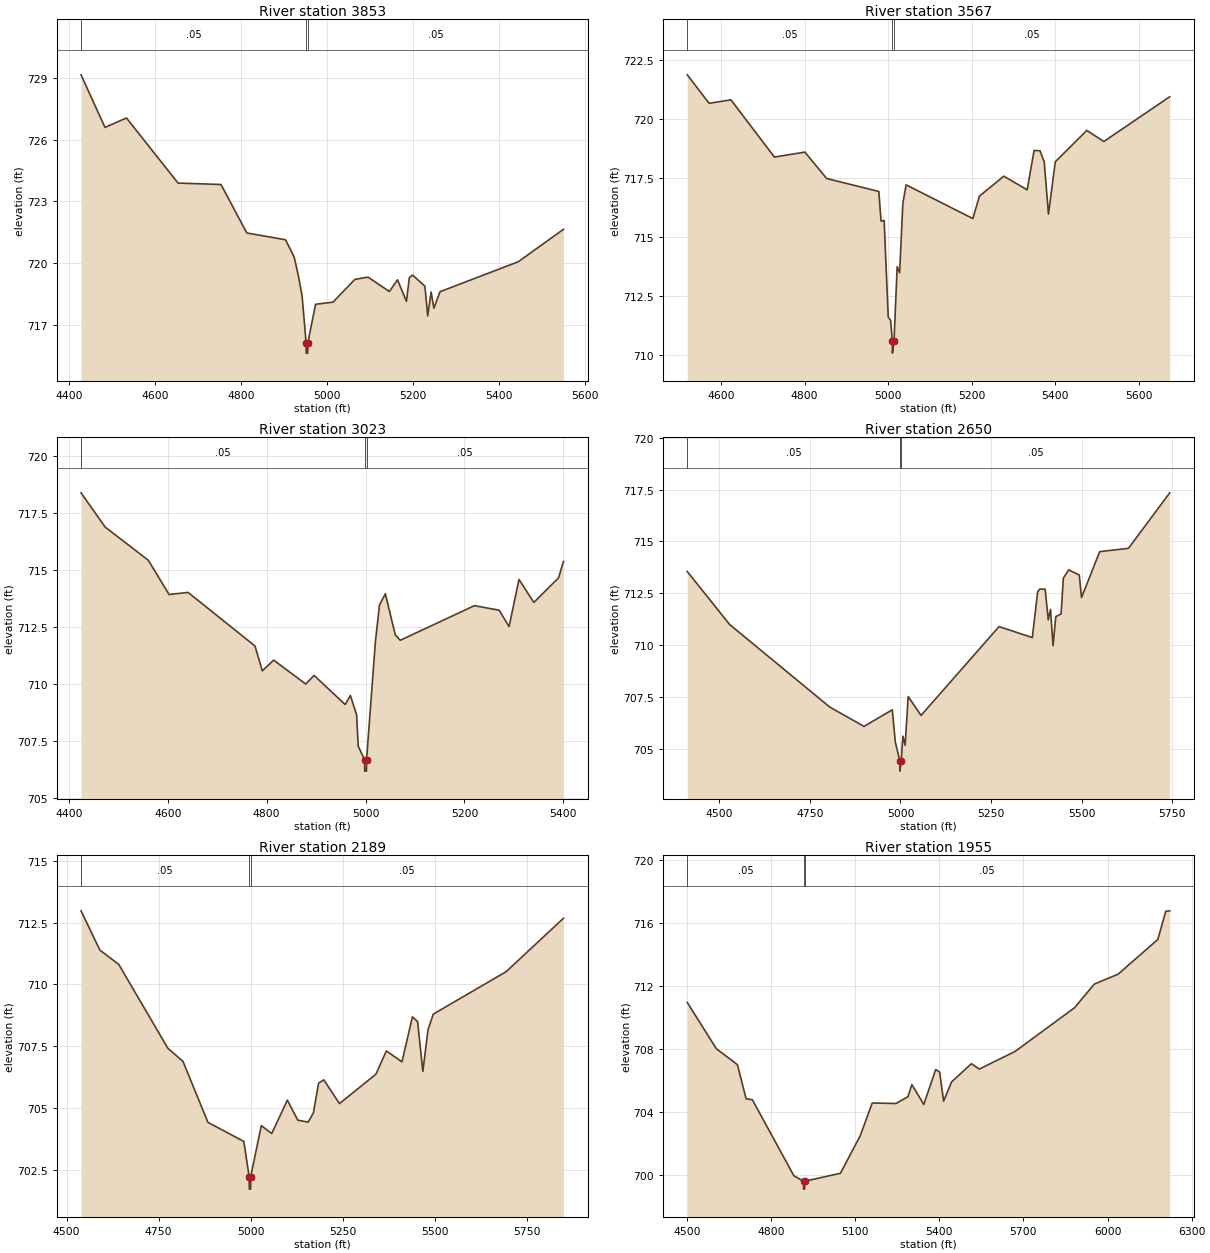
Type RM Length L Ch R = 1,3853,286,286,286
BEGIN DESCRIPTION:
Unnamed Tributary to Walnut Creek 2H 6.0
END DESCRIPTION:
XS GIS Cut Line= 5
      2323503.35      7034277.33      2324070.37      7034263.83
      2324221.38      7034232.94      2324305.48      7034130.65
      2324353.65      7033866.04
#Sta/Elev= 30
  4427.4  729.16  4483.1  726.60  4533.1  727.06  4653.1  723.89  4753.1  723.82
  4813.2  721.46  4903.2  721.13  4923.2  720.30  4933.2  719.38  4941.8  718.39
  4951.2  716.11  4951.4  715.61  4954.9  715.61  4955.2  716.11  4973.2  717.99
  5013.6  718.09  5064.6  719.20  5095.3  719.31  5144.9  718.61  5163.8  719.18
  5184.6  718.13  5191.4  719.29  5199.0  719.41  5227.6  718.87  5234.1  717.42
  5242.0  718.59  5248.5  717.80  5262.8  718.60  5444.9  720.06  5550.1  721.64
#Mann=3,-1,0
  4427.4    0.05       0  4951.2    0.05       0  4955.2    0.05       0
Bank Sta=4951.2,4955.2
Exp/Cntr=0.3,0.1

Type RM Length L Ch R = 1,3567,544,544,544
BEGIN DESCRIPTION:
Unnamed Tributary to Walnut Creek 2H 5.0
END DESCRIPTION:
XS GIS Cut Line= 4
      2324011.88      7034970.31      2324142.37      7034524.83
      2324303.88      7034252.38      2324378.12      7033885.34
#Sta/Elev= 30
  4518.8  721.87  4571.2  720.66  4623.3  720.81  4727.5  718.38  4800.5  718.59
  4852.6  717.47  4977.6  716.92  4982.9  715.66  4990.3  715.69  5000.1  711.59
  5005.9  711.45  5009.9  710.56  5010.1  710.06  5013.9  710.56  5021.5  713.73
  5027.4  713.47  5035.1  716.42  5043.0  717.20  5202.8  715.77  5218.4  716.72
  5276.9  717.57  5332.8  716.99  5349.4  718.66  5363.4  718.65  5373.6  718.18
  5383.8  715.96  5400.2  718.18  5475.6  719.51  5516.4  719.04  5674.2  720.94
#Mann=3,-1,0
  4518.8    0.05       0  5009.9   0.033       0  5013.9    0.05       0
Bank Sta=5009.9,5013.9
Exp/Cntr=0.3,0.1

Type RM Length L Ch R = 1,3023,373,373,373
BEGIN DESCRIPTION:
Unnamed Tributary to Walnut Creek 2H 4.0
END DESCRIPTION:
XS GIS Cut Line= 3
      2324529.01      7035059.98      2324695.88      7034524.83
      2324679.00      7034110.03
#Sta/Elev= 30
  4424.6  718.38  4473.3  716.88  4560.7  715.42  4602.6  713.92  4641.1  714.01
  4776.4  711.66  4791.2  710.57  4814.1  711.04  4879.1  709.99  4895.9  710.37
  4958.8  709.09  4969.3  709.49  4981.9  708.64  4985.1  707.27  4998.0  706.67
  4998.3  706.17  5001.8  706.17  5002.0  706.67  5020.0  711.87  5028.2  713.46
  5040.0  713.95  5060.1  712.15  5070.1  711.91  5220.2  713.43  5270.2  713.23
  5290.2  712.51  5310.3  714.58  5340.3  713.57  5390.3  714.65  5400.3  715.37
#Mann=3,-1,0
  4424.6    0.05       0  4998.0   0.033       0  5002.0    0.05       0
Bank Sta=4998,5002
Exp/Cntr=0.3,0.1

Type RM Length L Ch R = 1,2650,461,461,461
BEGIN DESCRIPTION:
Unnamed Tributary to Walnut Creek 2H 3.0
END DESCRIPTION:
XS GIS Cut Line= 3
      2325378.98      7035009.97      2325105.39      7034560.83
      2324628.98      7033909.97
#Sta/Elev= 30
  4411.1  713.55  4528.2  710.99  4804.2  707.01  4899.1  706.07  4977.3  706.87
  4985.8  705.31  4998.0  704.41  4998.3  703.91  5002.0  704.41  5006.6  705.60
  5012.8  705.16  5021.3  707.51  5056.8  706.60  5272.2  710.89  5364.1  710.36
  5378.8  712.57  5385.0  712.70  5399.6  712.70  5408.1  711.22  5414.3  711.72
  5421.4  709.97  5428.9  711.37  5443.6  711.50  5449.8  713.23  5464.5  713.63
  5493.8  713.38  5500.0  712.29  5550.2  714.51  5629.7  714.67  5743.6  717.35
#Mann=3,-1,0
  4411.1    0.05       0  4998.0   0.033       0  5002.0    0.05       0
Bank Sta=4998,5002
Exp/Cntr=0.3,0.1

Type RM Length L Ch R = 1,2189,234,234,234
BEGIN DESCRIPTION:
Unnamed Tributary to Walnut Creek 2H 2.0
END DESCRIPTION:
XS GIS Cut Line= 3
      2325429.00      7034960.02      2325529.00      7034510.00
      2324929.02      7033910.02
#Sta/Elev= 30
  4539.4  712.98  4590.6  711.39  4641.9  710.81  4775.0  707.42  4816.0  706.89
  4883.9  704.42  4981.2  703.65  4995.8  702.22  4996.1  701.72  4999.6  701.72
  4999.8  702.22  5028.7  704.29  5057.0  703.97  5099.4  705.32  5127.7  704.51
  5156.0  704.43  5170.1  704.81  5184.2  706.01  5198.4  706.14  5240.8  705.18
  5339.8  706.37  5368.1  707.31  5410.5  706.87  5438.8  708.69  5452.9  708.50
  5467.1  706.48  5481.2  708.17  5495.4  708.80  5693.4  710.52  5848.9  712.68
#Mann=3,-1,0
  4539.4    0.05       0  4995.8   0.033       0  4999.8    0.05       0
Bank Sta=4995.8,4999.8
Exp/Cntr=0.3,0.1

Type RM Length L Ch R = 1,1955,592,592,592
BEGIN DESCRIPTION:
Unnamed Tributary to Walnut Creek 2H 1.0
END DESCRIPTION:
XS GIS Cut Line= 3
      2325578.98      7034910.03      2325779.00      7034510.00
      2324879.03      7033610.03
#Sta/Elev= 30
  4501.8  710.96  4605.3  708.02  4680.7  707.00  4711.5  704.83  4733.8  704.77
  4882.0  699.93  4916.3  699.58  4916.6  699.08  4920.1  699.08  4920.3  699.58
  5048.0  700.09  5118.8  702.49  5161.2  704.56  5246.0  704.53  5288.5  704.96
  5302.6  705.73  5345.0  704.47  5387.5  706.69  5401.6  706.53  5415.7  704.68
  5444.0  705.90  5514.7  707.06  5543.0  706.72  5670.3  707.84  5882.4  710.62
  5953.1  712.13  6038.0  712.76  6179.4  714.97  6207.7  716.76  6221.8  716.79
#Mann=3,-1,0
  4501.8    0.05       0  4916.3   0.033       0  4920.3    0.05       0
Bank Sta=4916.3,4920.3
Exp/Cntr=0.3,0.1

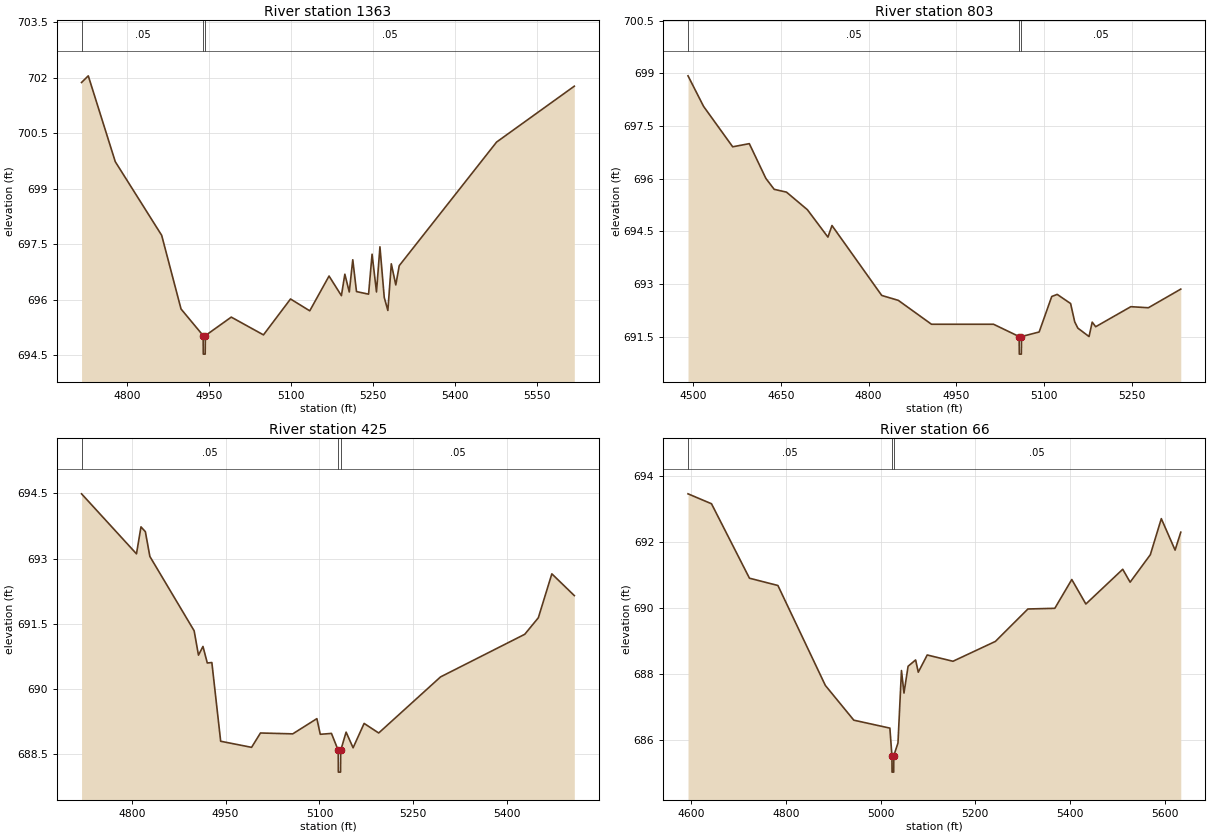
Type RM Length L Ch R = 1,1363,560,560,560
BEGIN DESCRIPTION:
UNT Wal 2H 0.7
END DESCRIPTION:
XS GIS Cut Line= 4
      2325977.14      7034885.47      2326208.65      7034658.68
      2326202.35      7034611.46      2325785.18      7034284.92
#Sta/Elev= 30
  4717.4  701.87  4729.7  702.05  4779.1  699.73  4864.0  697.74  4899.4  695.75
  4939.9  695.03  4940.1  694.53  4943.6  694.53  4943.9  695.03  4991.3  695.53
  5050.2  695.05  5099.7  696.02  5134.9  695.70  5170.2  696.64  5192.8  696.11
  5199.1  696.69  5207.2  696.21  5213.6  697.08  5220.4  696.22  5242.5  696.15
  5248.9  697.23  5257.0  696.21  5263.3  697.43  5271.2  696.06  5277.8  695.71
  5284.1  696.97  5292.3  696.40  5298.6  696.92  5476.7  700.26  5618.9  701.77
#Mann=3,-1,0
  4717.4    0.05       0  4939.9   0.033       0  4943.9    0.05       0
Bank Sta=4939.9,4943.9
Exp/Cntr=0.3,0.1

Type RM Length L Ch R = 1,803,378,378,378
BEGIN DESCRIPTION:
UNT Wal 2H 0.5
END DESCRIPTION:
XS GIS Cut Line= 4
      2326279.53      7035178.33      2326690.52      7034795.68
      2326631.70      7034644.70      2326513.88      7034636.28
#Sta/Elev= 30
  4491.7  698.93  4518.3  698.06  4568.0  696.91  4596.4  697.00  4624.7  696.01
  4638.9  695.70  4659.9  695.62  4695.6  695.12  4730.7  694.34  4737.6  694.67
  4822.6  692.68  4850.9  692.54  4907.6  691.86  5013.6  691.86  5057.3  691.51
  5057.6  691.01  5061.1  691.01  5061.3  691.51  5091.5  691.64  5113.0  692.65
  5122.3  692.71  5145.2  692.45  5152.2  691.93  5157.6  691.75  5176.7  691.51
  5182.1  691.92  5188.1  691.79  5248.1  692.36  5278.1  692.33  5333.4  692.86
#Mann=3,-1,0
  4491.7    0.05       0  5057.3   0.033       0  5061.3    0.05       0
Bank Sta=5057.3,5061.3
Exp/Cntr=0.3,0.1

Type RM Length L Ch R = 1,425,359,359,359
BEGIN DESCRIPTION:
UNT Wal 2H 0.3
END DESCRIPTION:
XS GIS Cut Line= 4
      2326626.05      7035321.39      2326870.36      7035088.32
      2326737.93      7034787.01      2326632.83      7034727.21
#Sta/Elev= 30
  4719.7  694.49  4807.5  693.11  4814.7  693.73  4821.7  693.62  4828.9  693.05
  4899.7  691.34  4906.6  690.78  4913.8  690.98  4920.7  690.60  4928.0  690.61
  4942.1  688.80  4991.5  688.66  5005.7  688.99  5057.3  688.97  5095.9  689.32
  5101.3  688.96  5119.2  688.98  5130.0  688.59  5130.2  688.09  5133.7  688.09
  5134.0  688.59  5142.6  689.01  5153.8  688.65  5171.4  689.21  5194.7  688.99
  5293.6  690.28  5428.2  691.26  5449.9  691.64  5471.5  692.65  5507.4  692.15
#Mann=3,-1,0
  4719.7    0.05       0  5130.0   0.033       0  5134.0    0.05       0
Bank Sta=5130,5134
Exp/Cntr=0.3,0.1

Type RM Length L Ch R = 1,66,0,0,0
BEGIN DESCRIPTION:
UNT Wal 2H 0.1
END DESCRIPTION:
XS GIS Cut Line= 5
      2327008.36      7035559.51      2327034.04      7035162.63
      2326928.42      7034891.41      2326757.48      7034773.46
      2326633.86      7034698.74
#Sta/Elev= 30
  4593.2  693.45  4642.8  693.15  4723.0  690.90  4783.1  690.68  4883.3  687.66
  4943.4  686.61  5019.6  686.37  5023.9  685.54  5024.2  685.04  5027.7  685.04
  5027.9  685.54  5036.7  685.92  5044.1  688.11  5049.4  687.43  5058.1  688.24
  5074.0  688.43  5079.6  688.06  5098.5  688.58  5152.9  688.39  5242.5  688.99
  5311.2  689.97  5368.0  689.99  5403.9  690.86  5433.6  690.12  5511.5  691.17
  5527.1  690.78  5569.8  691.61  5593.0  692.70  5622.1  691.75  5634.1  692.29
#Mann=3,-1,0
  4593.2    0.05       0  5023.9   0.033       0  5027.9    0.05       0
Bank Sta=5023.9,5027.9
Exp/Cntr=0.3,0.1

Chan Stop Cuts=-1