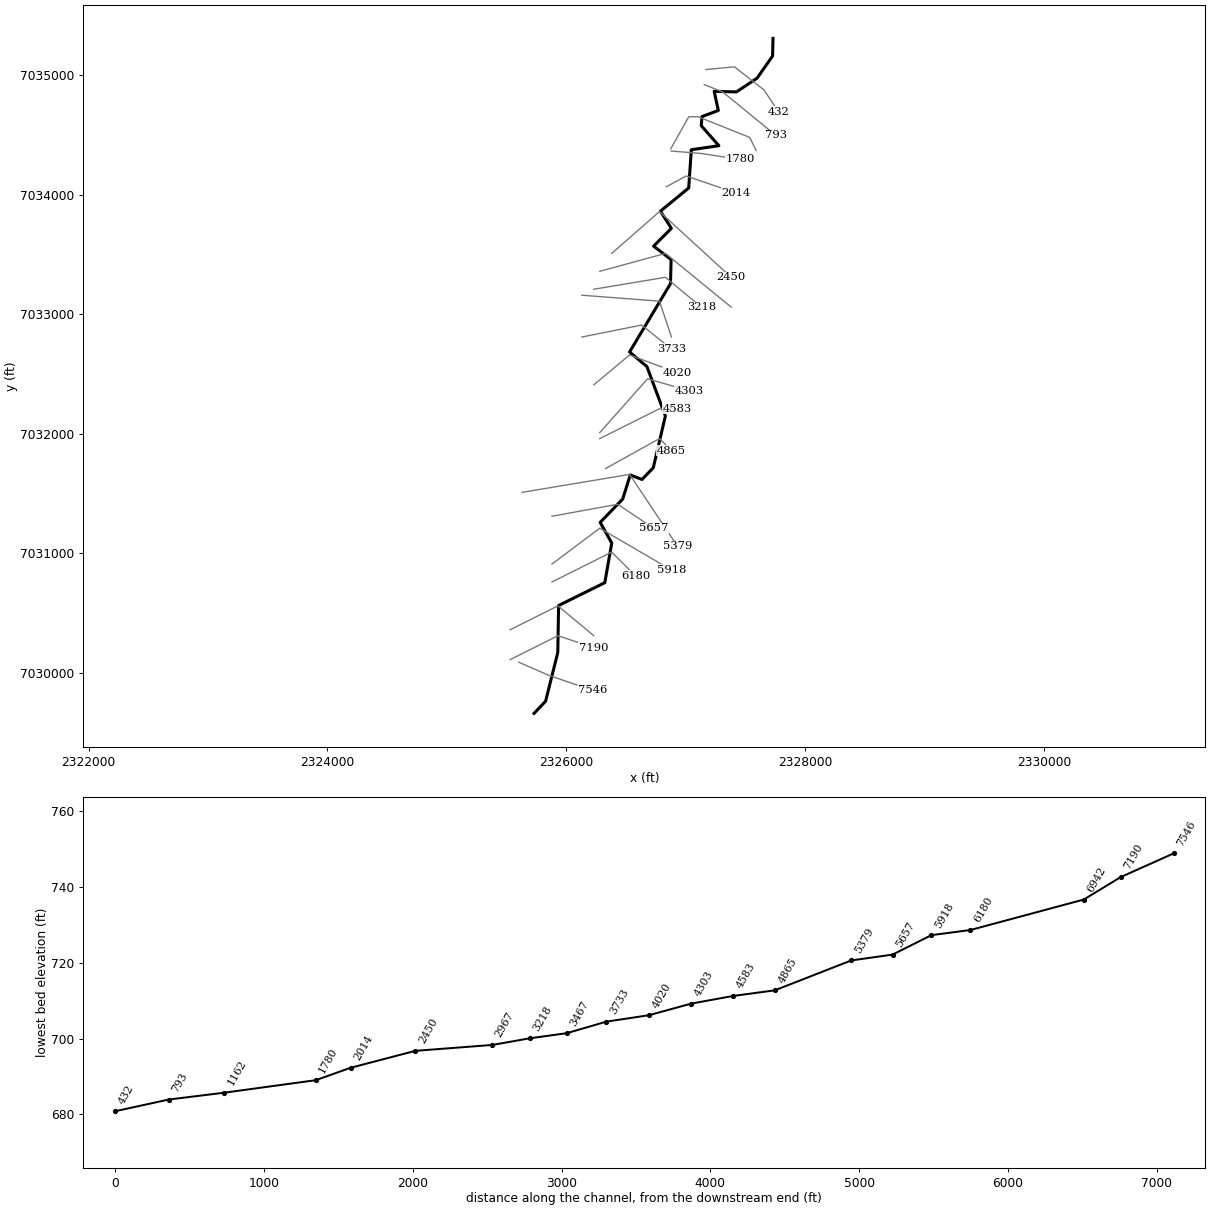
--- Unnamed Tr to Walnut Cr 2J.prj (project) ---

Proj Title=Unnamed Tr to Walnut Cr 2J Base Level Engineering
Current Plan=p01
Default Exp/Contr=0.3,0.1
English Units
Geom File=g01
Flow File=f01
Plan File=p01
BEGIN DESCRIPTION:
Unnamed Tr to Walnut Cr 2J
END DESCRIPTION:

--- Unnamed Tr to Walnut Cr 2J.p01 (plan) ---

Plan Title=Multiple Run
Short Identifier=Multiple
Geom File=g01
Flow File=f01
Subcritical Flow
K Sum by GR= 0
Std Step Tol= 0.01
Critical Tol= 0.01
Num of Std Step Trials= 20
Max Error Tol= 0.3
Flow Tol Ratio= 0.001
Split Flow NTrial= 30
Split Flow Tol= 0.02
Split Flow Ratio= 0.02
Log Output Level= 0
Friction Slope Method= 1
Unsteady Friction Slope Method= 2
Unsteady Bridges Friction Slope Method= 1
Parabolic Critical Depth
Global Vel Dist=  1 , 1 , 1
Global Log Level= 0
CheckData=True
Encroach Param= -1, 0, 0, 0
BEGIN DESCRIPTION:
Multiple Run
END DESCRIPTION:

--- Unnamed Tr to Walnut Cr 2J.f01 (steady flow) ---

Flow Title=Multiple
Number of Profiles=7
Profile Names=10-year,25-year,50-year,1pct_min,100-year,1pct_plu,500-year
River Rch & RM= Unnamed Tr to Wa,Reach-1,7546
     522     708     860     519    1040    2070    1500
River Rch & RM= Unnamed Tr to Wa,Reach-1,1162
     522     707     858     517    1030    2060    1490
Boundary for River Rch & Prof#=Unnamed Tr to Wa,Reach-1,1
Up Type=0
Dn Type=3
Dn Slope=0.005
Boundary for River Rch & Prof#=Unnamed Tr to Wa,Reach-1,2
Up Type=0
Dn Type=3
Dn Slope=0.005
Boundary for River Rch & Prof#=Unnamed Tr to Wa,Reach-1,3
Up Type=0
Dn Type=3
Dn Slope=0.005
Boundary for River Rch & Prof#=Unnamed Tr to Wa,Reach-1,4
Up Type=0
Dn Type=3
Dn Slope=0.005
Boundary for River Rch & Prof#=Unnamed Tr to Wa,Reach-1,5
Up Type=0
Dn Type=3
Dn Slope=0.005
Boundary for River Rch & Prof#=Unnamed Tr to Wa,Reach-1,6
Up Type=0
Dn Type=3
Dn Slope=0.005
Boundary for River Rch & Prof#=Unnamed Tr to Wa,Reach-1,7
Up Type=0
Dn Type=3
Dn Slope=0.005

--- Unnamed Tr to Walnut Cr 2J.g01 (geometry) ---

Geom Title=Existing Conditions

River Reach=Unnamed Tr to Wa,Reach-1
Reach XY= 30
      2325729.00      7029660.00      2325825.52      7029761.44
      2325927.62      7030169.66      2325934.34      7030562.74
      2326321.00      7030753.67      2326379.52      7031085.12
      2326282.46      7031258.50      2326470.86      7031453.94
      2326534.26      7031655.34      2326632.40      7031617.82
      2326726.82      7031715.43      2326828.23      7032149.31
      2326673.58      7032562.67      2326528.47      7032684.88
      2326870.93      7033256.69      2326875.96      7033458.58
      2326729.47      7033570.54      2326878.36      7033719.64
      2326786.83      7033863.27      2327023.30      7034057.46
      2327045.41      7034377.65      2327276.02      7034411.43
      2327128.81      7034578.34      2327133.96      7034654.89
      2327271.32      7034706.30      2327236.64      7034866.55
      2327422.96      7034861.63      2327595.71      7034976.64
      2327725.28      7035161.54      2327729.00      7035310.00

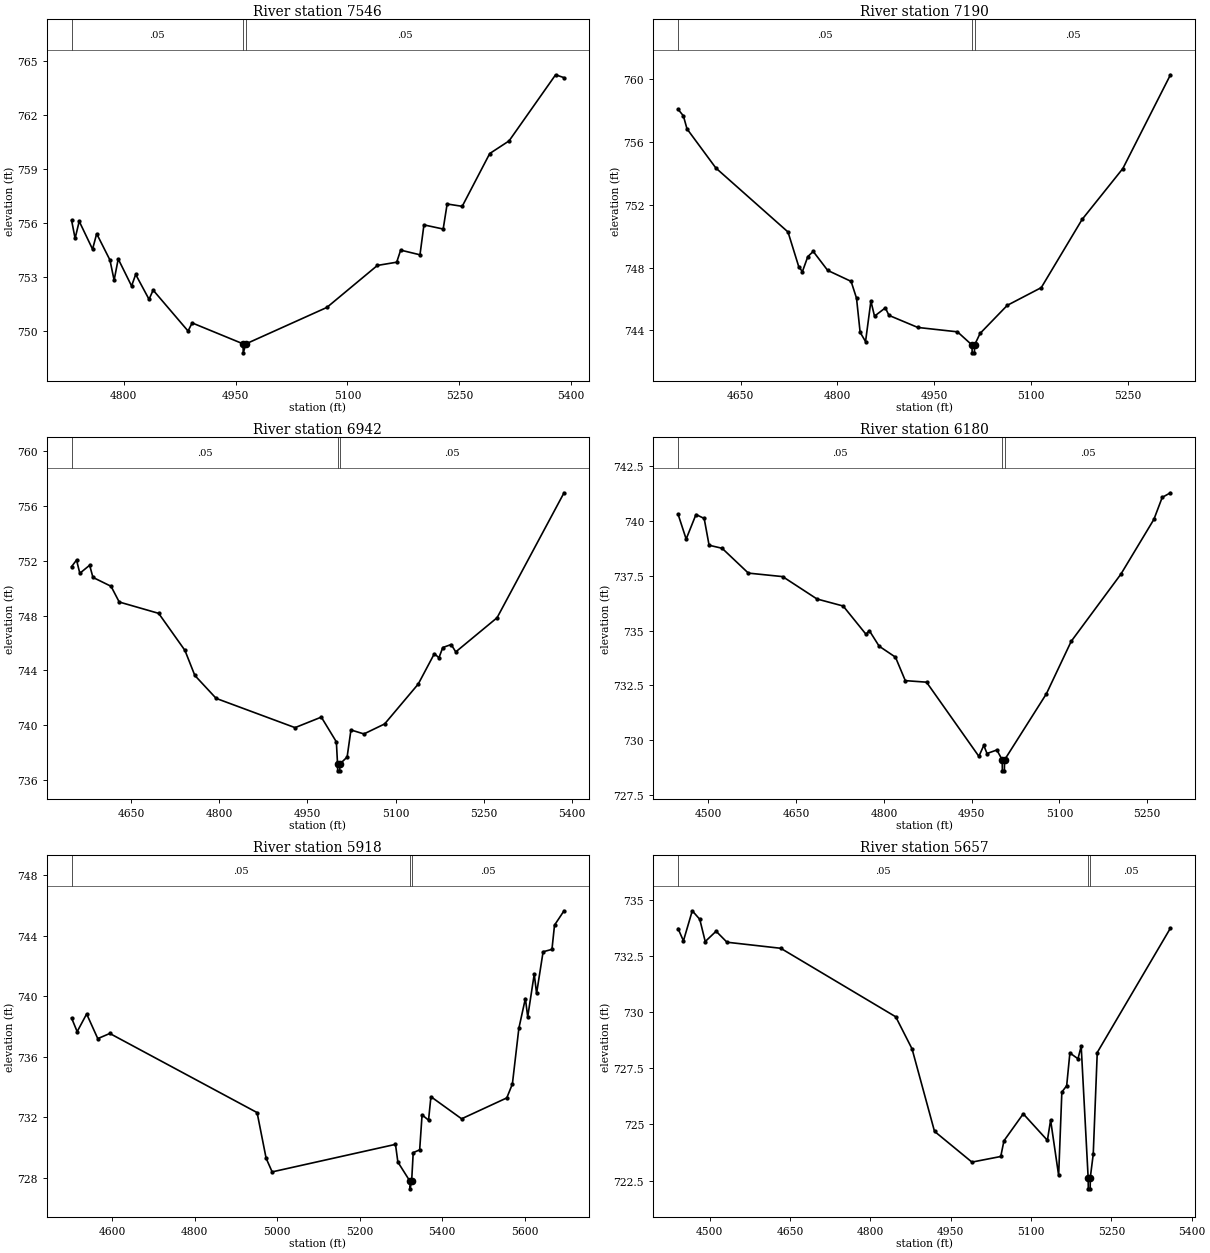
Type RM Length L Ch R = 1,7546,356,356,356
BEGIN DESCRIPTION:
Unnamed Tributary to Walnut Creek 2J 16.0
END DESCRIPTION:
XS GIS Cut Line= 3
      2325601.86      7030087.84      2325850.48      7029979.40
      2326218.04      7029852.47
#Sta/Elev= 30
  4730.2  756.15  4734.9  755.15  4740.4  756.10  4758.3  754.55  4763.8  755.41
  4781.6  753.95  4787.2  752.83  4792.7  754.01  4810.6  752.51  4816.1  753.15
  4834.0  751.77  4839.5  752.28  4886.3  750.01  4891.8  750.46  4960.0  749.30
  4960.3  748.80  4964.0  749.30  5072.4  751.32  5140.1  753.65  5166.0  753.83
  5171.3  754.50  5197.2  754.24  5202.5  755.90  5228.3  755.67  5233.6  757.06
  5253.8  756.93  5290.7  759.86  5316.6  760.56  5379.0  764.23  5390.3  764.07
#Mann=3,-1,0
  4730.2    0.05       0  4960.0    0.05       0  4964.0    0.05       0
Bank Sta=4960,4964
Exp/Cntr=0.3,0.1

Type RM Length L Ch R = 1,7190,248,248,248
BEGIN DESCRIPTION:
Unnamed Tributary to Walnut Creek 2J 15.0
END DESCRIPTION:
XS GIS Cut Line= 3
      2325529.03      7030110.02      2325929.00      7030310.00
      2326228.99      7030210.00
#Sta/Elev= 30
  4552.8  758.10  4561.1  757.68  4566.7  756.85  4611.5  754.35  4723.3  750.27
  4740.0  748.05  4745.6  747.74  4754.0  748.70  4762.4  749.03  4784.8  747.82
  4821.1  747.12  4829.5  746.05  4835.1  743.87  4843.5  743.28  4851.8  745.86
  4857.4  744.90  4874.2  745.43  4879.8  744.95  4924.5  744.18  4986.0  743.90
  5008.5  743.06  5008.8  742.56  5012.3  742.56  5012.5  743.06  5021.1  743.80
  5063.2  745.59  5115.9  746.72  5179.2  751.07  5242.4  754.32  5316.2  760.30
#Mann=3,-1,0
  4552.8    0.05       0  5008.5    0.05       0  5012.5    0.05       0
Bank Sta=5008.5,5012.5
Exp/Cntr=0.3,0.1

Type RM Length L Ch R = 1,6942,762,762,762
BEGIN DESCRIPTION:
Unnamed Tributary to Walnut Creek 2J 14.0
END DESCRIPTION:
XS GIS Cut Line= 3
      2325529.02      7030360.01      2325929.00      7030560.00
      2326229.00      7030310.00
#Sta/Elev= 30
  4548.9  751.58  4557.3  752.06  4562.9  751.09  4579.6  751.68  4585.2  750.79
  4616.0  750.14  4629.9  748.99  4697.0  748.16  4741.7  745.45  4758.5  743.62
  4794.8  741.94  4929.0  739.80  4973.7  740.57  4999.3  738.76  5001.3  737.14
  5001.5  736.64  5005.0  736.64  5005.3  737.14  5017.6  737.65  5024.1  739.63
  5046.2  739.34  5081.4  740.07  5138.6  742.99  5166.0  745.21  5173.8  744.91
  5180.3  745.66  5194.6  745.88  5202.4  745.34  5272.7  747.84  5386.6  756.98
#Mann=3,-1,0
  4548.9    0.05       0  5001.3    0.05       0  5005.3    0.05       0
Bank Sta=5001.3,5005.3
Exp/Cntr=0.3,0.1

Type RM Length L Ch R = 1,6180,262,262,262
BEGIN DESCRIPTION:
Unnamed Tributary to Walnut Creek 2J 13.0
END DESCRIPTION:
XS GIS Cut Line= 3
      2325879.02      7030760.01      2326379.00      7031010.00
      2326578.98      7030810.02
#Sta/Elev= 30
  4448.0  740.31  4461.9  739.17  4478.7  740.29  4492.7  740.11  4501.1  738.89
  4523.4  738.75  4568.2  737.62  4626.9  737.46  4685.6  736.44  4730.3  736.12
  4769.4  734.83  4775.0  735.00  4791.8  734.29  4819.7  733.79  4836.5  732.72
  4872.8  732.65  4962.3  729.27  4970.7  729.77  4976.2  729.40  4993.0  729.56
  5002.2  729.11  5002.4  728.61  5005.9  728.61  5006.2  729.11  5077.7  732.12
  5120.1  734.51  5205.0  737.57  5261.5  740.07  5275.7  741.07  5289.8  741.28
#Mann=3,-1,0
  4448.0    0.05       0  5002.2   0.033       0  5006.2    0.05       0
Bank Sta=5002.2,5006.2
Exp/Cntr=0.3,0.1

Type RM Length L Ch R = 1,5918,261,261,261
BEGIN DESCRIPTION:
Unnamed Tributary to Walnut Creek 2J 12.0
END DESCRIPTION:
XS GIS Cut Line= 3
      2325879.00      7030910.00      2326279.00      7031210.00
      2326878.99      7030860.01
#Sta/Elev= 30
  4501.1  738.55  4514.6  737.65  4537.6  738.82  4564.6  737.19  4593.8  737.53
  4951.1  732.30  4973.0  729.28  4987.6  728.38  5286.8  730.20  5292.6  729.03
  5322.0  727.76  5322.3  727.26  5326.0  727.76  5329.8  729.65  5345.5  729.84
  5351.3  732.15  5367.0  731.80  5372.8  733.35  5447.2  731.89  5556.8  733.27
  5570.4  734.19  5586.1  737.87  5601.9  739.84  5607.6  738.63  5623.4  741.45
  5629.1  740.18  5644.9  742.93  5666.4  743.09  5672.6  744.69  5695.7  745.64
#Mann=3,-1,0
  4501.1    0.05       0  5322.0   0.033       0  5326.0    0.05       0
Bank Sta=5322,5326
Exp/Cntr=0.3,0.1

Type RM Length L Ch R = 1,5657,278,278,278
BEGIN DESCRIPTION:
Unnamed Tributary to Walnut Creek 2J 11.0
END DESCRIPTION:
XS GIS Cut Line= 3
      2325879.03      7031310.01      2326429.00      7031410.00
      2326728.97      7031210.02
#Sta/Elev= 30
  4440.8  733.72  4450.9  733.17  4467.4  734.51  4481.4  734.13  4491.6  733.14
  4511.9  733.60  4532.2  733.11  4632.6  732.84  4847.3  729.79  4877.8  728.36
  4919.7  724.69  4989.6  723.32  5043.4  723.57  5049.4  724.27  5085.4  725.47
  5130.5  724.29  5136.5  725.19  5151.5  722.73  5157.5  726.44  5166.5  726.72
  5172.5  728.18  5187.6  727.92  5193.6  728.48  5206.6  722.63  5206.9  722.13
  5210.4  722.13  5210.6  722.63  5216.1  723.67  5223.6  728.20  5360.3  733.74
#Mann=3,-1,0
  4440.8    0.05       0  5206.6   0.033       0  5210.6    0.05       0
Bank Sta=5206.6,5210.6
Exp/Cntr=0.3,0.1

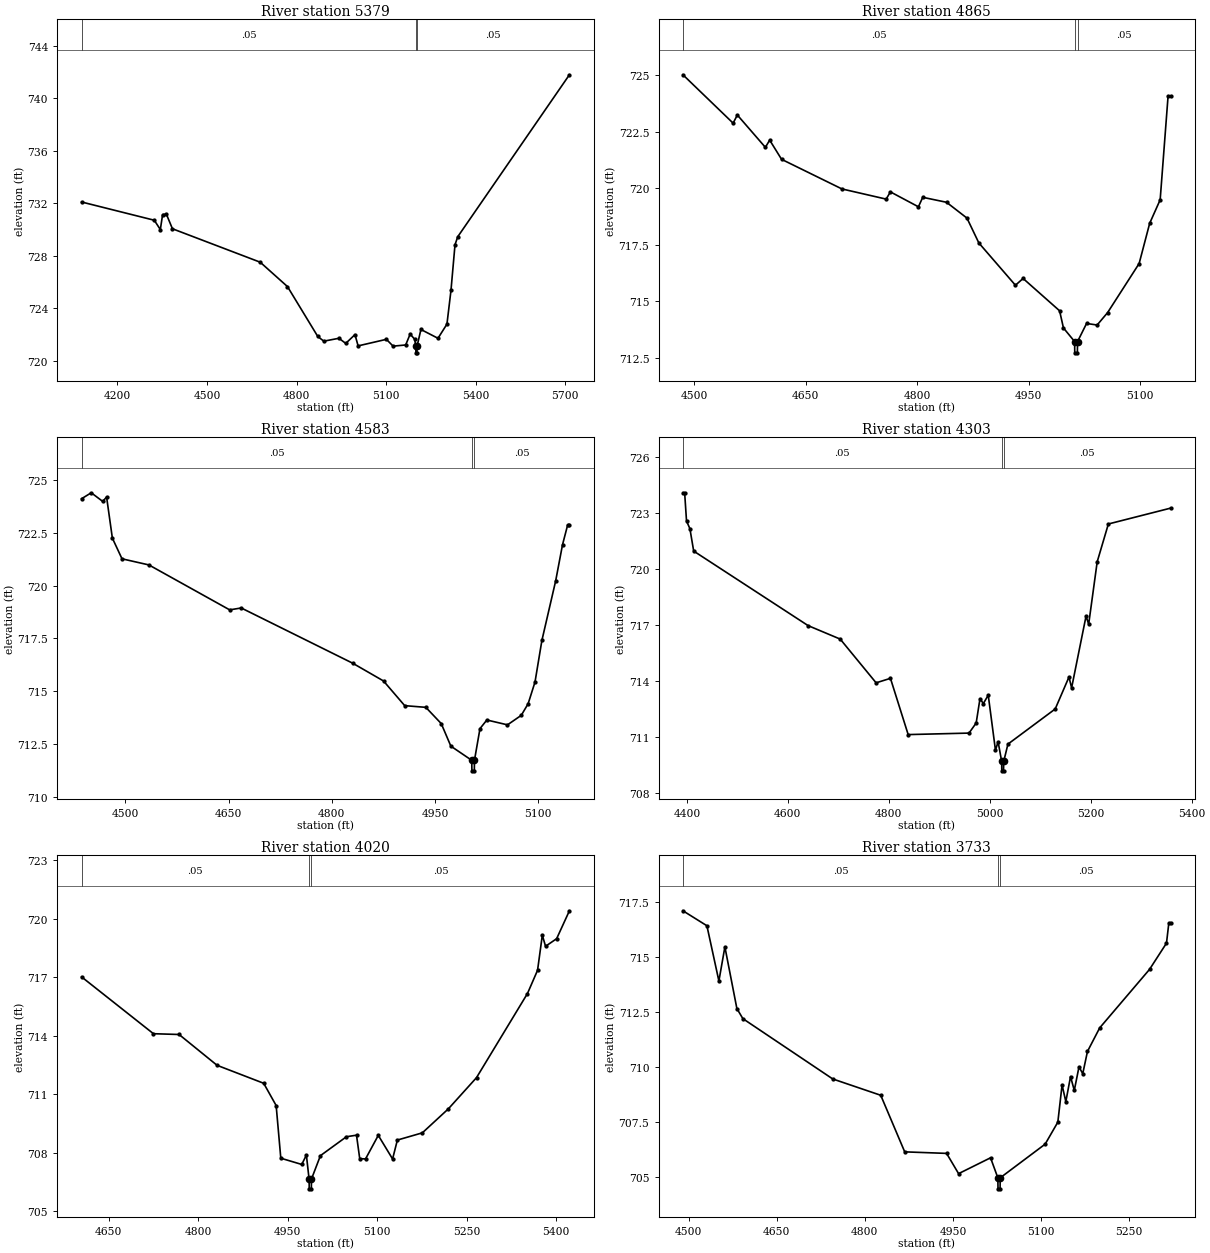
Type RM Length L Ch R = 1,5379,514,514,514
BEGIN DESCRIPTION:
Unnamed Tributary to Walnut Creek 2J 10.0
END DESCRIPTION:
XS GIS Cut Line= 3
      2325628.99      7031510.00      2326529.00      7031660.00
      2326928.98      7031060.03
#Sta/Elev= 30
  4080.1  732.09  4323.4  730.70  4343.7  729.99  4351.3  731.13  4364.0  731.16
  4384.2  730.05  4678.2  727.50  4769.5  725.64  4870.9  721.84  4891.1  721.48
  4941.8  721.70  4964.6  721.31  4995.5  721.98  5006.0  721.12  5100.7  721.62
  5123.2  721.10  5165.3  721.19  5180.3  722.02  5195.3  721.63  5199.3  721.09
  5199.6  720.59  5203.1  720.59  5203.3  721.09  5216.4  722.37  5273.5  721.70
  5303.5  722.78  5317.0  725.35  5330.5  728.83  5339.6  729.44  5713.6  741.79
#Mann=3,-1,0
  4080.1    0.05       0  5199.3   0.033       0  5203.3    0.05       0
Bank Sta=5199.3,5203.3
Exp/Cntr=0.3,0.1

Type RM Length L Ch R = 1,4865,282,282,282
BEGIN DESCRIPTION:
Unnamed Tributary to Walnut Creek 2J 9.0
END DESCRIPTION:
XS GIS Cut Line= 3
      2326329.03      7031710.02      2326779.00      7031960.00
      2326879.02      7031859.98
#Sta/Elev= 30
  4484.8  725.01  4552.3  722.87  4558.0  723.23  4595.7  721.80  4601.5  722.12
  4617.5  721.27  4698.7  719.96  4758.2  719.51  4763.9  719.83  4801.6  719.17
  4807.4  719.59  4839.4  719.37  4866.9  718.67  4882.9  717.57  4932.1  715.70
  4942.4  716.00  4991.5  714.57  4996.7  713.81  5011.7  713.21  5011.9  712.71
  5015.4  712.71  5015.7  713.21  5027.8  714.01  5042.0  713.94  5056.1  714.49
  5098.5  716.66  5112.7  718.44  5126.8  719.48  5137.4  724.05  5141.0  724.05
#Mann=3,-1,0
  4484.8    0.05       0  5011.7   0.033       0  5015.7    0.05       0
Bank Sta=5011.7,5015.7
Exp/Cntr=0.3,0.1

Type RM Length L Ch R = 1,4583,280,280,280
BEGIN DESCRIPTION:
Unnamed Tributary to Walnut Creek 2J 8.0
END DESCRIPTION:
XS GIS Cut Line= 3
      2326279.00      7031960.00      2326779.00      7032210.00
      2326928.98      7032210.00
#Sta/Elev= 30
  4436.3  724.12  4450.3  724.40  4467.0  723.99  4472.6  724.20  4481.0  722.25
  4495.0  721.27  4534.1  720.98  4651.5  718.85  4668.3  718.94  4830.4  716.32
  4875.1  715.48  4905.9  714.31  4936.6  714.23  4959.0  713.46  4973.0  712.39
  5003.3  711.72  5003.6  711.22  5007.1  711.22  5007.3  711.72  5015.3  713.22
  5025.3  713.63  5055.3  713.40  5075.3  713.85  5085.3  714.40  5095.3  715.43
  5105.3  717.40  5125.3  720.22  5135.3  721.94  5142.8  722.88  5145.3  722.88
#Mann=3,-1,0
  4436.3    0.05       0  5003.3   0.033       0  5007.3    0.05       0
Bank Sta=5003.3,5007.3
Exp/Cntr=0.3,0.1

Type RM Length L Ch R = 1,4303,283,283,283
BEGIN DESCRIPTION:
Unnamed Tributary to Walnut Creek 2J 7.0
END DESCRIPTION:
XS GIS Cut Line= 3
      2326278.99      7032009.99      2326679.00      7032460.00
      2327029.00      7032360.00
#Sta/Elev= 30
  4392.3  724.09  4395.7  724.09  4399.4  722.58  4406.1  722.17  4413.6  720.97
  4640.3  716.98  4703.8  716.26  4774.9  713.92  4803.3  714.16  4838.4  711.15
  4958.9  711.23  4973.1  711.77  4980.6  713.07  4987.3  712.81  4997.0  713.26
  5011.3  710.31  5016.5  710.77  5023.6  709.71  5023.8  709.21  5027.3  709.21
  5027.6  709.71  5036.0  710.64  5129.6  712.52  5156.9  714.23  5162.1  713.65
  5190.7  717.49  5195.9  717.06  5212.8  720.40  5234.9  722.42  5358.4  723.27
#Mann=3,-1,0
  4392.3    0.05       0  5023.6   0.033       0  5027.6    0.05       0
Bank Sta=5023.6,5027.6
Exp/Cntr=0.3,0.1

Type RM Length L Ch R = 1,4020,287,287,287
BEGIN DESCRIPTION:
Unnamed Tributary to Walnut Creek 2J 6.0
END DESCRIPTION:
XS GIS Cut Line= 3
      2326229.00      7032410.00      2326529.00      7032660.00
      2326928.99      7032510.00
#Sta/Elev= 30
  4604.6  717.02  4725.0  714.11  4768.0  714.07  4831.7  712.49  4909.8  711.57
  4930.7  710.43  4938.5  707.73  4973.6  707.41  4981.4  707.89  4985.9  706.66
  4986.2  706.16  4989.7  706.16  4989.9  706.66  5004.9  707.86  5048.5  708.83
  5065.4  708.91  5070.8  707.71  5080.5  707.69  5101.9  708.90  5125.9  707.69
  5133.9  708.66  5175.8  709.03  5219.4  710.26  5266.6  711.86  5352.0  716.17
  5368.9  717.36  5376.9  719.16  5382.3  718.59  5400.9  718.98  5422.3  720.41
#Mann=3,-1,0
  4604.6    0.05       0  4985.9   0.033       0  4989.9    0.05       0
Bank Sta=4985.9,4989.9
Exp/Cntr=0.3,0.1

Type RM Length L Ch R = 1,3733,266,266,266
BEGIN DESCRIPTION:
Unnamed Tributary to Walnut Creek 2J 5.0
END DESCRIPTION:
XS GIS Cut Line= 3
      2326128.97      7032809.99      2326629.00      7032910.00
      2326879.01      7032709.99
#Sta/Elev= 30
  4490.5  717.09  4531.3  716.41  4551.7  713.90  4561.9  715.45  4582.3  712.65
  4592.5  712.19  4745.5  709.45  4827.1  708.71  4867.9  706.14  4939.2  706.07
  4959.6  705.15  5014.0  705.87  5026.4  704.96  5026.7  704.46  5030.2  704.46
  5030.4  704.96  5106.9  706.49  5128.5  707.49  5135.7  709.18  5142.1  708.42
  5150.1  709.56  5156.5  708.93  5164.5  710.00  5170.9  709.69  5178.9  710.70
  5199.7  711.77  5284.6  714.43  5313.4  715.62  5317.4  716.54  5320.6  716.54
#Mann=3,-1,0
  4490.5    0.05       0  5026.4   0.033       0  5030.4    0.05       0
Bank Sta=5026.4,5030.4
Exp/Cntr=0.3,0.1

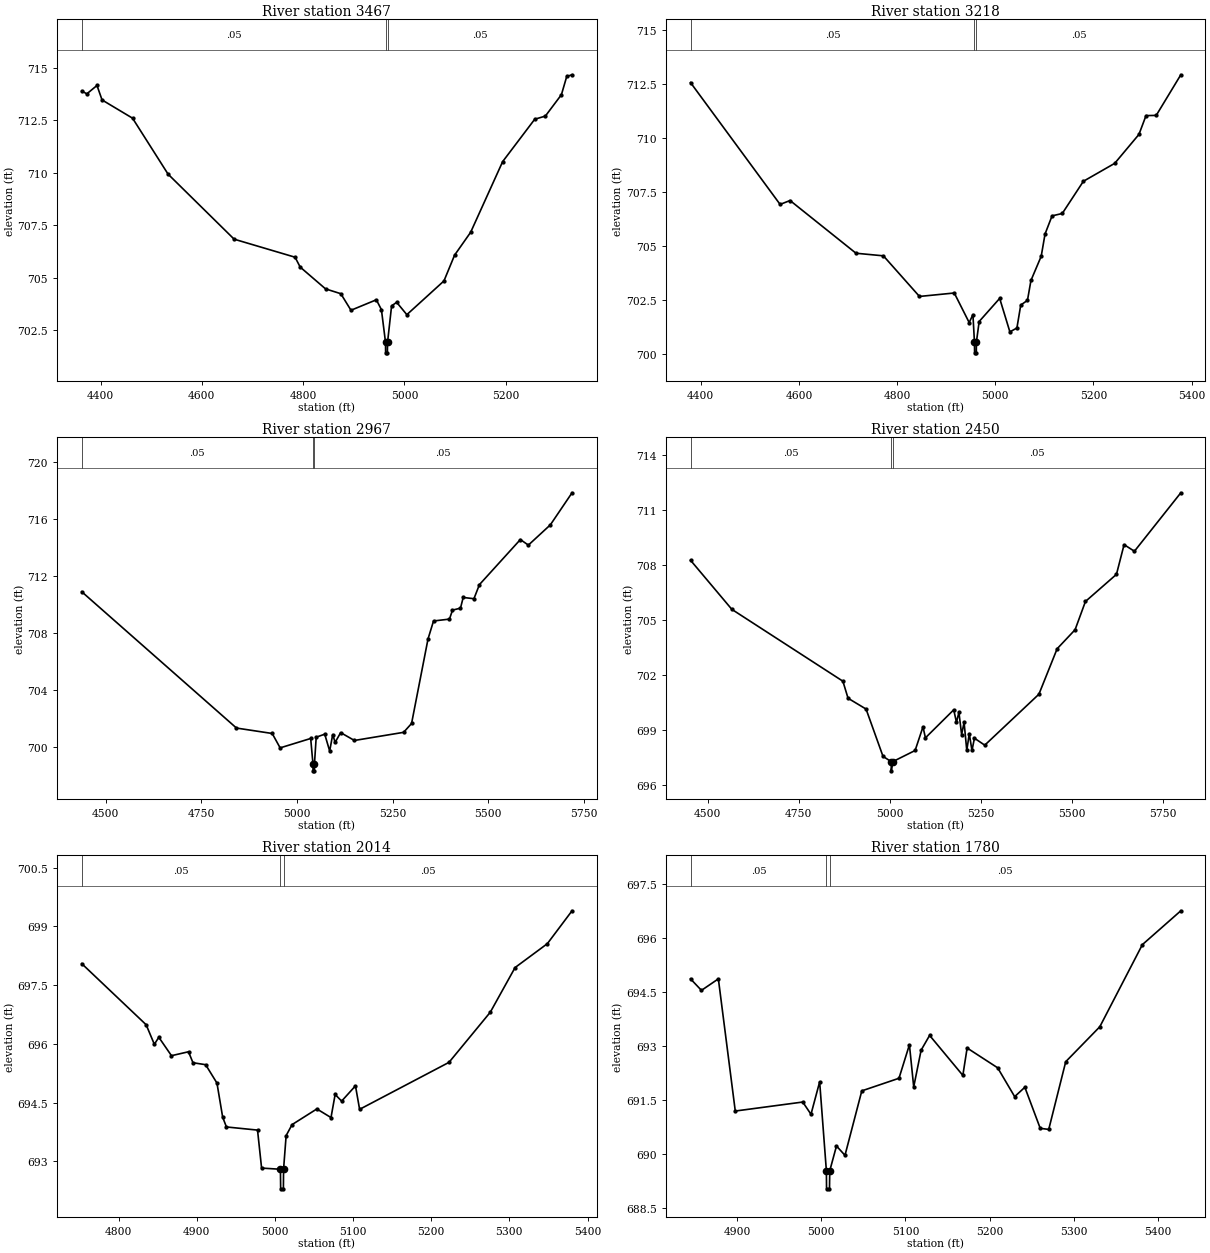
Type RM Length L Ch R = 1,3467,249,249,249
BEGIN DESCRIPTION:
Unnamed Tributary to Walnut Creek 2J 4.0
END DESCRIPTION:
XS GIS Cut Line= 3
      2326129.00      7033160.00      2326779.00      7033110.00
      2326878.98      7032810.05
#Sta/Elev= 30
  4362.9  713.91  4372.9  713.77  4393.0  714.17  4403.0  713.48  4463.2  712.61
  4533.4  709.94  4663.8  706.84  4784.1  705.98  4794.2  705.51  4844.3  704.47
  4874.4  704.24  4894.5  703.45  4944.6  703.95  4954.6  703.48  4962.7  701.92
  4962.9  701.42  4966.4  701.42  4966.7  701.92  4974.7  703.66  4984.7  703.83
  5004.8  703.24  5078.1  704.85  5099.1  706.08  5130.8  707.17  5194.0  710.54
  5257.3  712.56  5278.3  712.71  5310.0  713.73  5320.5  714.60  5331.0  714.68
#Mann=3,-1,0
  4362.9    0.05       0  4962.7   0.033       0  4966.7    0.05       0
Bank Sta=4962.7,4966.7
Exp/Cntr=0.3,0.1

Type RM Length L Ch R = 1,3218,251,251,251
BEGIN DESCRIPTION:
Unnamed Tributary to Walnut Creek 2J 3.0
END DESCRIPTION:
XS GIS Cut Line= 3
      2326228.99      7033210.00      2326829.00      7033310.00
      2327129.00      7033060.00
#Sta/Elev= 30
  4379.1  712.58  4561.6  706.94  4581.9  707.12  4716.2  704.68  4772.0  704.56
  4845.5  702.68  4916.4  702.84  4946.8  701.47  4954.4  701.84  4957.5  700.57
  4957.8  700.07  4961.3  700.07  4961.5  700.57  4967.1  701.52  5008.9  702.59
  5029.7  701.04  5044.0  701.22  5051.8  702.28  5065.5  702.50  5072.6  703.42
  5093.5  704.54  5101.3  705.57  5115.6  706.41  5136.4  706.52  5179.4  708.01
  5243.2  708.84  5292.6  710.18  5307.0  711.05  5327.8  711.06  5377.9  712.94
#Mann=3,-1,0
  4379.1    0.05       0  4957.5   0.033       0  4961.5    0.05       0
Bank Sta=4957.5,4961.5
Exp/Cntr=0.3,0.1

Type RM Length L Ch R = 1,2967,517,517,517
BEGIN DESCRIPTION:
Unnamed Tributary to Walnut Creek 2J 2.0
END DESCRIPTION:
XS GIS Cut Line= 3
      2326279.04      7033360.01      2326829.00      7033510.00
      2327379.01      7033059.99
#Sta/Elev= 30
  4437.9  710.88  4842.1  701.32  4935.4  700.94  4956.1  699.93  5035.9  700.59
  5041.8  698.82  5042.1  698.32  5045.6  698.32  5045.8  698.82  5050.3  700.68
  5072.6  700.89  5085.5  699.71  5093.4  700.86  5099.8  700.32  5114.2  701.00
  5150.1  700.45  5278.6  701.02  5299.4  701.64  5342.4  707.57  5356.8  708.83
  5398.4  708.96  5406.3  709.59  5427.2  709.73  5434.3  710.48  5462.3  710.39
  5476.7  711.38  5583.6  714.54  5604.5  714.15  5661.9  715.57  5718.6  717.82
#Mann=3,-1,0
  4437.9    0.05       0  5041.8   0.033       0  5045.8    0.05       0
Bank Sta=5041.8,5045.8
Exp/Cntr=0.3,0.1

Type RM Length L Ch R = 1,2450,436,436,436
BEGIN DESCRIPTION:
Unnamed Tributary to Walnut Creek 2J 1.0
END DESCRIPTION:
XS GIS Cut Line= 3
      2326379.01      7033510.01      2326779.00      7033860.00
      2327378.97      7033310.03
#Sta/Elev= 30
  4453.0  708.26  4566.4  705.58  4871.1  701.66  4885.3  700.73  4934.7  700.14
  4981.2  697.56  5003.8  697.27  5004.0  696.77  5007.8  697.27  5069.3  697.88
  5090.9  699.17  5097.6  698.57  5175.3  700.10  5182.7  699.42  5189.5  699.96
  5196.9  698.75  5203.7  699.41  5211.1  697.88  5217.9  698.80  5225.3  697.88
  5232.1  698.55  5260.4  698.17  5409.0  700.95  5459.0  703.43  5508.3  704.47
  5536.7  706.01  5621.8  707.49  5642.7  709.11  5671.1  708.75  5798.4  711.94
#Mann=3,-1,0
  4453.0    0.05       0  5003.8   0.033       0  5007.8    0.05       0
Bank Sta=5003.8,5007.8
Exp/Cntr=0.3,0.1

Type RM Length L Ch R = 1,2014,234,234,234
BEGIN DESCRIPTION:
UNT Wal 2J 0.5
END DESCRIPTION:
XS GIS Cut Line= 3
      2326836.99      7034068.16      2327002.32      7034157.91
      2327418.01      7034016.20
#Sta/Elev= 30
  4752.9  698.05  4835.3  696.49  4845.8  695.99  4851.5  696.17  4867.7  695.70
  4889.5  695.80  4895.2  695.52  4911.4  695.47  4925.9  695.00  4933.2  694.13
  4938.0  693.88  4977.8  693.80  4983.0  692.83  5007.1  692.80  5007.4  692.30
  5010.9  692.30  5011.1  692.80  5014.4  693.66  5022.0  693.94  5053.7  694.34
  5071.8  694.12  5077.1  694.71  5085.4  694.54  5103.1  694.93  5108.4  694.33
  5222.8  695.53  5275.6  696.81  5307.3  697.95  5348.6  698.56  5380.2  699.40
#Mann=3,-1,0
  4752.9    0.05       0  5007.1   0.033       0  5011.1    0.05       0
Bank Sta=5007.1,5011.1
Exp/Cntr=0.3,0.1

Type RM Length L Ch R = 1,1780,618,618,618
BEGIN DESCRIPTION:
UNT Wal 2J 0.3
END DESCRIPTION:
XS GIS Cut Line= 3
      2326876.02      7034366.73      2327123.05      7034347.08
      2327454.20      7034296.56
#Sta/Elev= 30
  4844.5  694.86  4857.5  694.54  4877.6  694.86  4897.7  691.19  4977.9  691.44
  4987.7  691.10  4998.0  692.00  5006.0  689.53  5006.2  689.03  5009.7  689.03
  5010.0  689.53  5018.0  690.22  5028.1  689.96  5048.1  691.75  5092.3  692.10
  5104.7  693.03  5109.8  691.86  5118.6  692.88  5128.7  693.29  5168.2  692.18
  5173.3  692.94  5209.6  692.39  5229.8  691.59  5241.9  691.85  5260.2  690.71
  5270.3  690.68  5290.5  692.56  5331.0  693.53  5381.6  695.81  5427.3  696.75
#Mann=3,-1,0
  4844.5    0.05       0  5006.0   0.033       0  5010.0    0.05       0
Bank Sta=5006,5010
Exp/Cntr=0.3,0.1

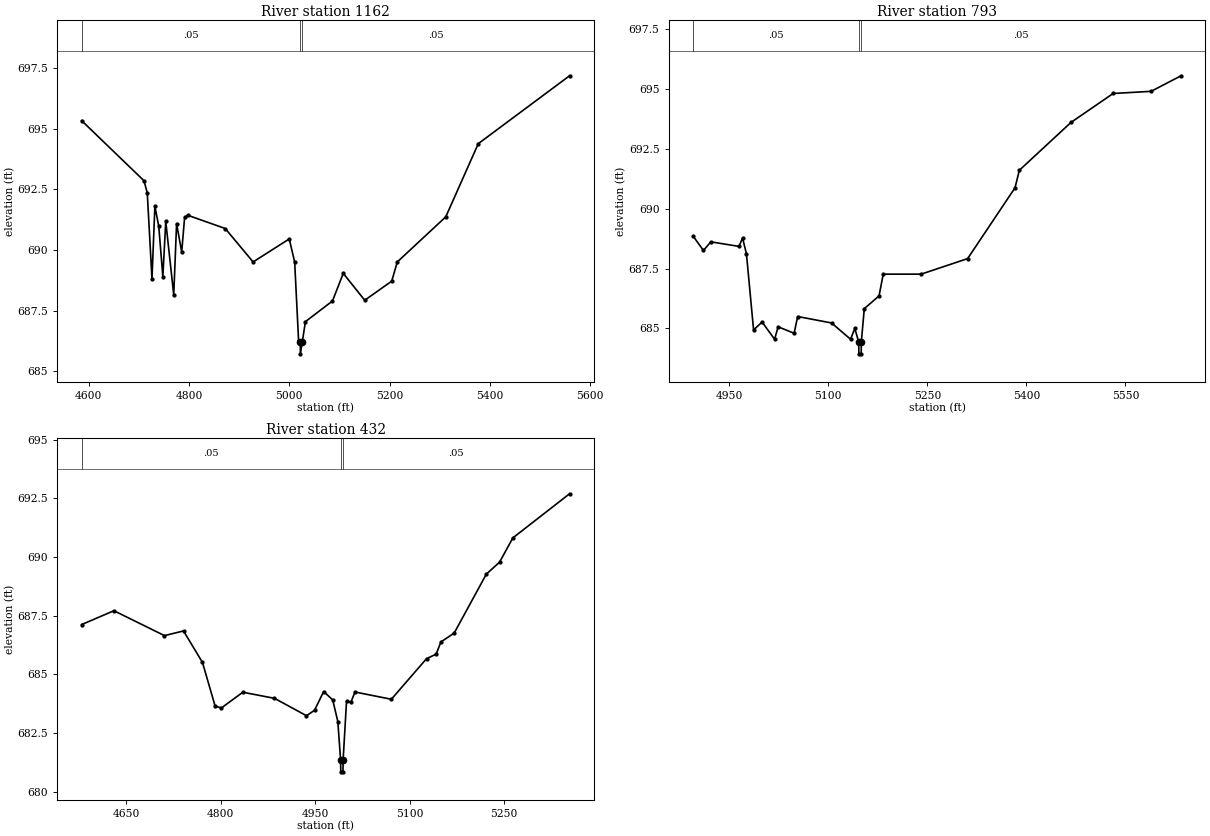
Type RM Length L Ch R = 1,1162,369,369,369
BEGIN DESCRIPTION:
UNT Wal 2J 0.25
END DESCRIPTION:
XS GIS Cut Line= 5
      2326873.46      7034385.87      2327023.65      7034653.24
      2327101.74      7034653.71      2327533.62      7034480.96
      2327588.13      7034370.48
#Sta/Elev= 30
  4585.7  695.34  4710.1  692.86  4716.6  692.36  4726.0  688.81  4731.8  691.81
  4739.5  690.99  4747.7  688.91  4753.5  691.18  4769.4  688.15  4775.1  691.09
  4785.3  689.92  4791.1  691.35  4796.9  691.44  4872.1  690.89  4927.7  689.51
  4999.8  690.46  5010.6  689.50  5018.4  686.27  5021.8  686.22  5022.0  685.72
  5025.8  686.22  5032.1  687.05  5086.0  687.90  5107.5  689.04  5150.3  687.93
  5204.2  688.72  5215.2  689.51  5311.9  691.37  5376.8  694.39  5558.8  697.19
#Mann=3,-1,0
  4585.7    0.05       0  5021.8   0.033       0  5025.8    0.05       0
Bank Sta=5021.8,5025.8
Exp/Cntr=0.3,0.1

Type RM Length L Ch R = 1,793,361,361,361
BEGIN DESCRIPTION:
UNT Wal 2J 0.2
END DESCRIPTION:
XS GIS Cut Line= 3
      2327153.98      7034922.65      2327308.36      7034860.89
      2327752.01      7034498.68
#Sta/Elev= 30
  4895.2  688.86  4910.9  688.26  4922.1  688.62  4964.7  688.43  4970.1  688.78
  4976.0  688.12  4986.8  684.94  4999.7  685.27  5018.6  684.55  5024.0  685.07
  5048.2  684.80  5053.6  685.50  5104.9  685.23  5133.7  684.55  5140.1  685.00
  5146.0  684.44  5146.3  683.94  5149.8  683.94  5150.0  684.44  5154.5  685.83
  5176.8  686.36  5183.2  687.27  5240.6  687.27  5311.0  687.92  5382.8  690.88
  5389.3  691.61  5467.5  693.61  5531.4  694.82  5588.9  694.91  5634.2  695.56
#Mann=3,-1,0
  4895.2    0.05       0  5146.0   0.033       0  5150.0    0.05       0
Bank Sta=5146,5150
Exp/Cntr=0.3,0.1

Type RM Length L Ch R = 1,432,0,0,0
BEGIN DESCRIPTION:
UNT Wal 2J 0.1
END DESCRIPTION:
XS GIS Cut Line= 4
      2327167.95      7035049.01      2327406.64      7035071.48
      2327653.72      7034877.74      2327776.41      7034693.71
#Sta/Elev= 30
  4578.9  687.12  4630.2  687.71  4710.5  686.65  4740.7  686.85  4770.8  685.51
  4790.9  683.65  4800.9  683.57  4834.9  684.24  4885.2  683.98  4936.0  683.24
  4948.8  683.47  4963.3  684.27  4977.7  683.91  4985.8  682.99  4990.2  681.35
  4990.5  680.85  4994.0  680.85  4994.2  681.35  4999.6  683.85  5006.7  683.82
  5013.0  684.25  5070.8  683.94  5126.7  685.67  5141.9  685.86  5149.5  686.38
  5170.6  686.76  5221.7  689.27  5242.7  689.78  5263.7  690.81  5353.8  692.69
#Mann=3,-1,0
  4578.9    0.05       0  4990.2   0.033       0  4994.2    0.05       0
Bank Sta=4990.2,4994.2
Exp/Cntr=0.3,0.1

Chan Stop Cuts=-1