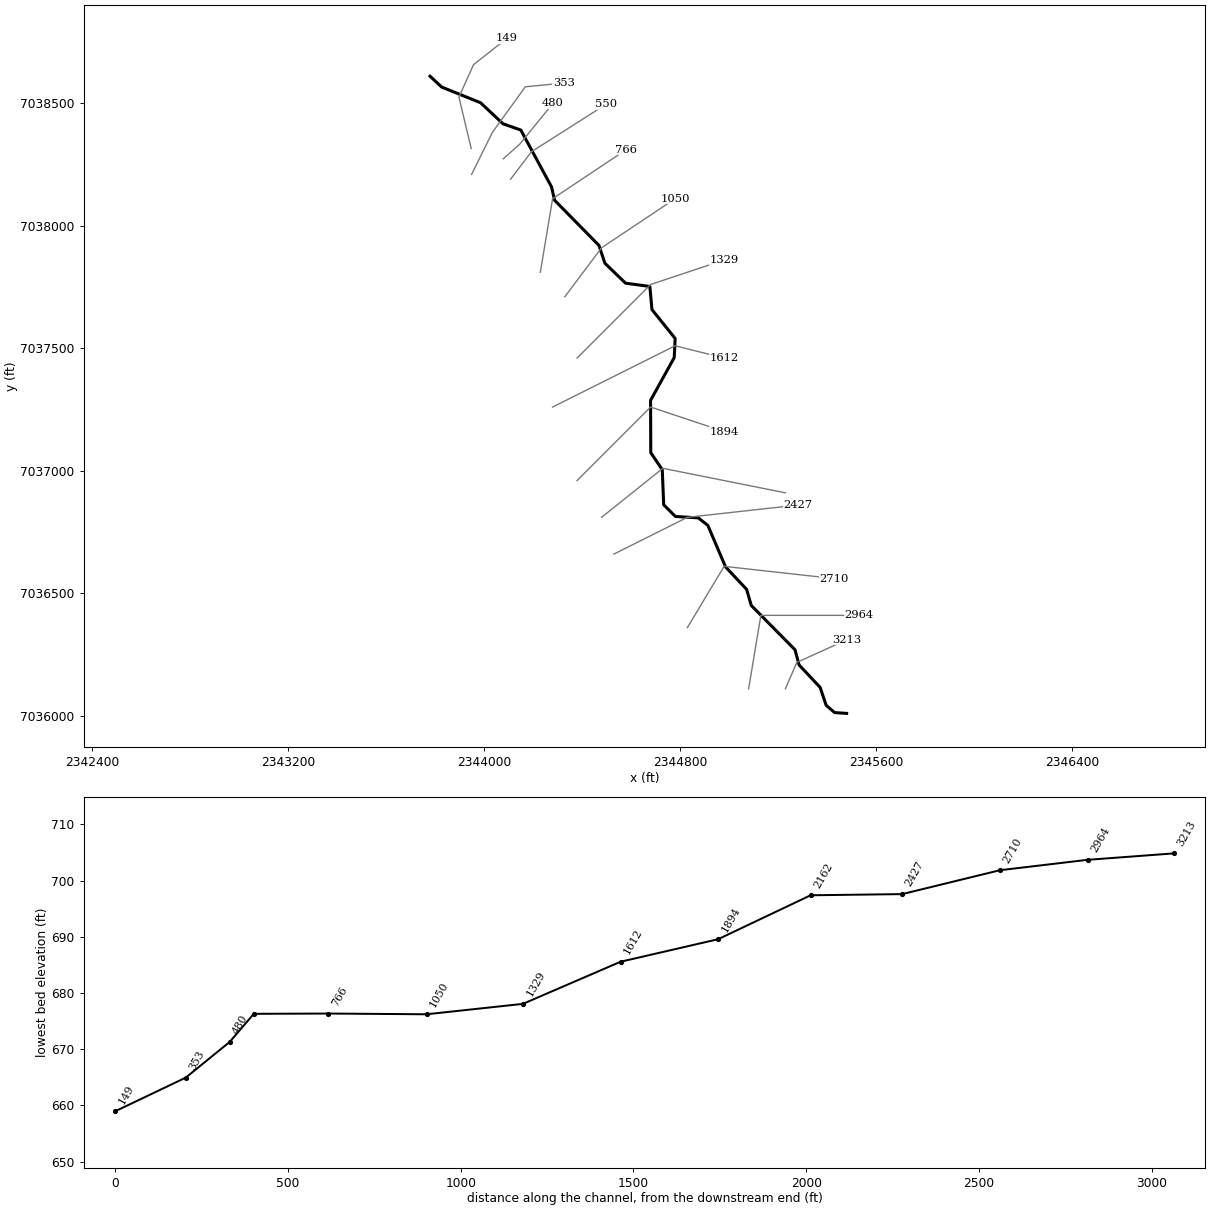
--- Unnamed Tr to Walnut Cr 2K.prj (project) ---

Proj Title=Unnamed Tr to Walnut Cr 2K Base Level Engineering
Current Plan=p01
Default Exp/Contr=0.3,0.1
English Units
Geom File=g01
Flow File=f01
Plan File=p01
BEGIN DESCRIPTION:
Unnamed Tr to Walnut Cr 2K
END DESCRIPTION:

--- Unnamed Tr to Walnut Cr 2K.p01 (plan) ---

Plan Title=Multiple Run
Short Identifier=Multiple
Geom File=g01
Flow File=f01
Subcritical Flow
K Sum by GR= 0
Std Step Tol= 0.01
Critical Tol= 0.01
Num of Std Step Trials= 20
Max Error Tol= 0.3
Flow Tol Ratio= 0.001
Split Flow NTrial= 30
Split Flow Tol= 0.02
Split Flow Ratio= 0.02
Log Output Level= 0
Friction Slope Method= 1
Unsteady Friction Slope Method= 2
Unsteady Bridges Friction Slope Method= 1
Parabolic Critical Depth
Global Vel Dist=  1 , 1 , 1
Global Log Level= 0
CheckData=True
Encroach Param= -1, 0, 0, 0
BEGIN DESCRIPTION:
Multiple Run
END DESCRIPTION:

--- Unnamed Tr to Walnut Cr 2K.f01 (steady flow) ---

Flow Title=Multiple
Number of Profiles=7
Profile Names=10-year,25-year,50-year,1pct_min,100-year,1pct_plu,500-year
River Rch & RM= Unnamed Tr to Wa,Reach-1,3213
     289     378     448     265     528    1050     731
Boundary for River Rch & Prof#=Unnamed Tr to Wa,Reach-1,1
Up Type=0
Dn Type=3
Dn Slope=0.005
Boundary for River Rch & Prof#=Unnamed Tr to Wa,Reach-1,2
Up Type=0
Dn Type=3
Dn Slope=0.005
Boundary for River Rch & Prof#=Unnamed Tr to Wa,Reach-1,3
Up Type=0
Dn Type=3
Dn Slope=0.005
Boundary for River Rch & Prof#=Unnamed Tr to Wa,Reach-1,4
Up Type=0
Dn Type=3
Dn Slope=0.005
Boundary for River Rch & Prof#=Unnamed Tr to Wa,Reach-1,5
Up Type=0
Dn Type=3
Dn Slope=0.005
Boundary for River Rch & Prof#=Unnamed Tr to Wa,Reach-1,6
Up Type=0
Dn Type=3
Dn Slope=0.005
Boundary for River Rch & Prof#=Unnamed Tr to Wa,Reach-1,7
Up Type=0
Dn Type=3
Dn Slope=0.005

--- Unnamed Tr to Walnut Cr 2K.g01 (geometry) ---

Geom Title=Existing Conditions

River Reach=Unnamed Tr to Wa,Reach-1
Reach XY= 30
      2345479.00      7036010.00      2345430.03      7036013.14
      2345395.38      7036042.97      2345370.83      7036116.03
      2345284.87      7036207.72      2345268.22      7036269.68
      2345089.78      7036450.32      2345070.82      7036516.04
      2344984.85      7036607.71      2344912.55      7036777.13
      2344873.70      7036807.81      2344780.25      7036813.51
      2344732.44      7036861.23      2344726.61      7037004.47
      2344679.68      7037073.92      2344678.89      7037287.32
      2344775.33      7037461.59      2344779.21      7037539.95
      2344684.57      7037657.64      2344675.97      7037751.99
      2344576.62      7037765.55      2344492.62      7037846.76
      2344468.22      7037919.68      2344287.14      7038103.94
      2344274.81      7038158.26      2344149.48      7038390.37
      2344076.74      7038415.88      2343985.05      7038501.84
      2343826.64      7038565.67      2343779.00      7038610.00

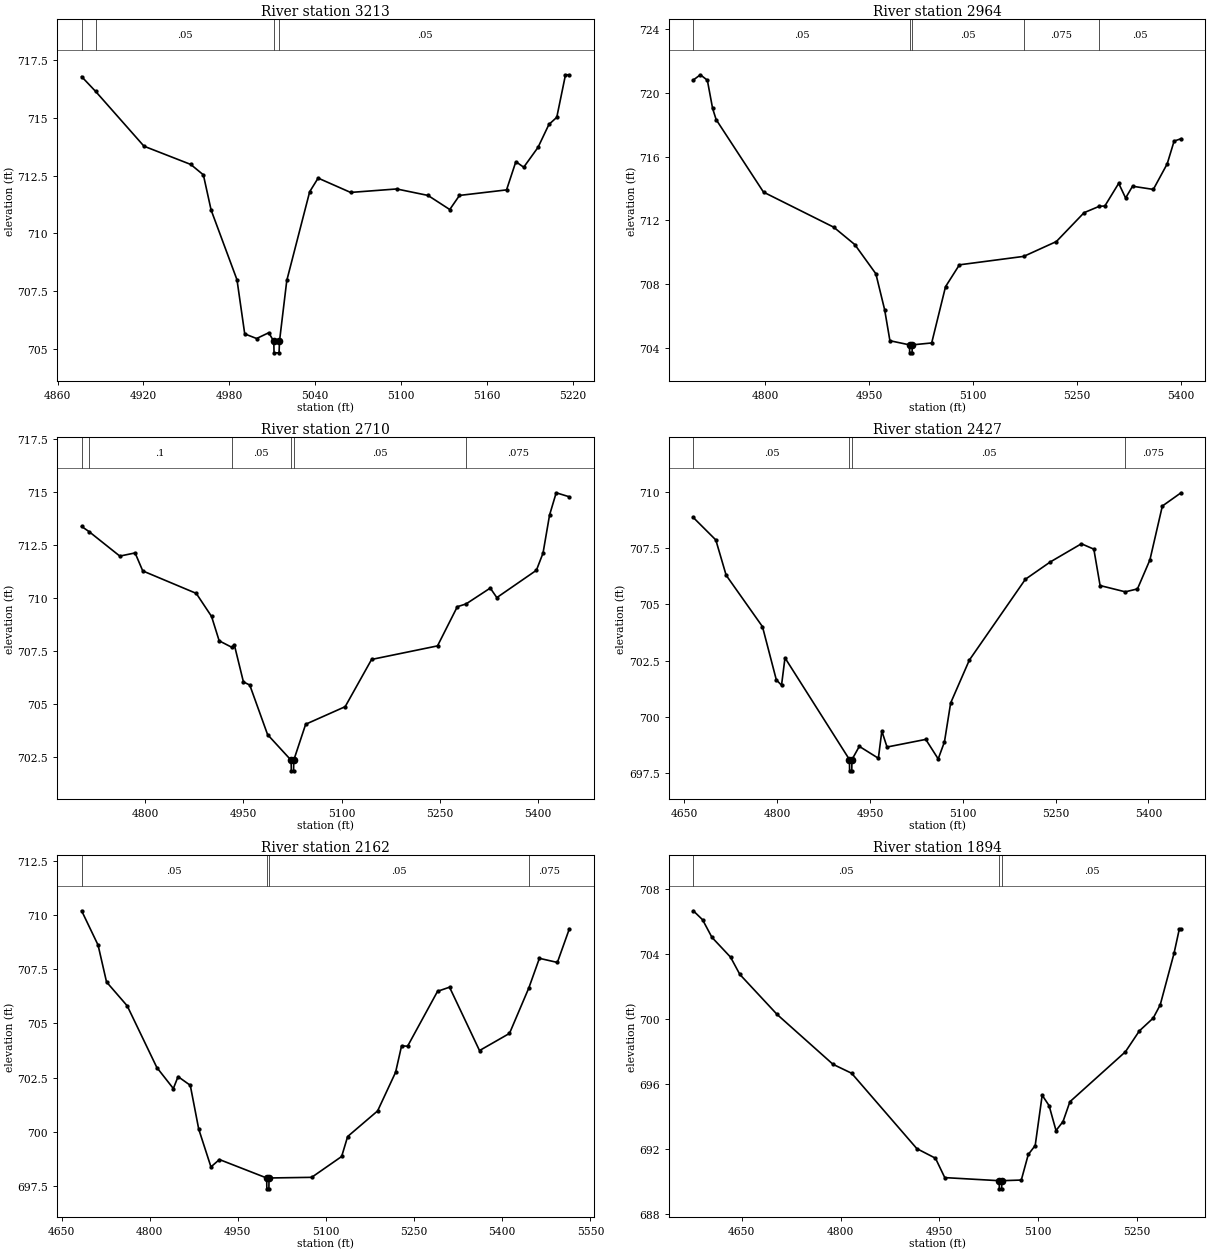
Type RM Length L Ch R = 1,3213,249,249,249
BEGIN DESCRIPTION:
Unnamed Tributary to Walnut Creek 2K 12.0
END DESCRIPTION:
XS GIS Cut Line= 3
      2345228.99      7036109.97      2345275.58      7036218.00
      2345478.99      7036310.00
#Sta/Elev= 30
  4876.8  716.78  4886.6  716.14  4920.4  713.77  4953.1  712.98  4961.9  712.53
  4967.3  711.01  4985.4  707.99  4990.8  705.65  4999.1  705.45  5007.6  705.70
  5011.1  705.33  5011.3  704.83  5014.8  704.83  5015.1  705.33  5020.2  707.96
  5036.2  711.80  5042.1  712.39  5064.8  711.77  5097.0  711.92  5118.9  711.64
  5134.1  711.03  5140.9  711.64  5173.8  711.88  5180.3  713.10  5185.8  712.86
  5195.8  713.72  5203.4  714.71  5208.9  715.02  5215.0  716.86  5217.7  716.86
#Mann=4,-1,0
  4876.8   0.075       0  4886.6    0.05       0  5011.1    0.05       0
  5015.1    0.05       0
Bank Sta=5011.1,5015.1
Exp/Cntr=0.3,0.1

Type RM Length L Ch R = 1,2964,254,254,254
BEGIN DESCRIPTION:
Unnamed Tributary to Walnut Creek 2K 11.0
END DESCRIPTION:
XS GIS Cut Line= 3
      2345079.00      7036109.98      2345129.00      7036410.00
      2345529.04      7036410.00
#Sta/Elev= 30
  4696.1  720.80  4706.3  721.13  4716.4  720.79  4724.0  719.02  4729.1  718.32
  4797.5  713.77  4898.9  711.57  4929.3  710.48  4959.7  708.65  4972.4  706.39
  4980.0  704.45  5008.3  704.19  5008.5  703.69  5012.0  703.69  5012.3  704.19
  5040.3  704.31  5060.3  707.84  5080.3  709.21  5173.2  709.74  5220.3  710.67
  5260.3  712.48  5282.2  712.88  5290.3  712.90  5310.3  714.32  5320.3  713.40
  5330.3  714.14  5360.3  713.94  5380.3  715.54  5390.3  716.97  5400.3  717.12
#Mann=5,-1,0
  4696.1    0.05       0  5008.3    0.05       0  5012.3    0.05       0
  5173.2   0.075       0  5282.2    0.05       0
Bank Sta=5008.3,5012.3
Exp/Cntr=0.3,0.1

Type RM Length L Ch R = 1,2710,283,283,283
BEGIN DESCRIPTION:
Unnamed Tributary to Walnut Creek 2K 10.0
END DESCRIPTION:
XS GIS Cut Line= 3
      2344829.00      7036359.99      2344979.00      7036610.00
      2345428.97      7036560.00
#Sta/Elev= 30
  4703.4  713.38  4714.6  713.14  4761.7  711.98  4785.0  712.13  4796.7  711.28
  4878.3  710.22  4901.7  709.13  4913.3  707.98  4932.2  707.68  4936.6  707.77
  4950.3  706.04  4960.0  705.89  4987.2  703.55  5023.1  702.34  5023.4  701.84
  5026.9  701.84  5027.1  702.34  5045.3  704.04  5105.6  704.87  5145.9  707.10
  5246.5  707.74  5276.7  709.59  5290.0  709.72  5327.0  710.47  5337.0  710.02
  5397.4  711.31  5407.5  712.12  5417.5  713.92  5427.6  714.97  5447.7  714.78
#Mann=6,-1,0
  4703.4   0.075       0  4714.6     0.1       0  4932.2    0.05       0
  5023.1    0.05       0  5027.1    0.05       0  5290.0   0.075       0
Bank Sta=5023.1,5027.1
Exp/Cntr=0.3,0.1

Type RM Length L Ch R = 1,2427,265,265,265
BEGIN DESCRIPTION:
Unnamed Tributary to Walnut Creek 2K 9.0
END DESCRIPTION:
XS GIS Cut Line= 3
      2344528.98      7036659.99      2344829.00      7036810.00
      2345279.00      7036860.00
#Sta/Elev= 30
  4664.6  708.87  4701.0  707.87  4717.7  706.30  4776.4  704.01  4798.8  701.64
  4807.2  701.40  4812.8  702.62  4917.0  698.09  4917.2  697.59  4920.7  697.59
  4921.0  698.09  4932.9  698.68  4963.7  698.15  4969.3  699.36  4977.7  698.65
  5040.3  698.99  5060.4  698.12  5070.5  698.88  5080.5  700.61  5110.7  702.52
  5201.3  706.12  5241.5  706.89  5291.8  707.70  5311.9  707.46  5322.0  705.84
  5362.7  705.56  5382.4  705.69  5402.5  706.98  5422.6  709.38  5452.8  709.97
#Mann=4,-1,0
  4664.6    0.05       0  4917.0   0.033       0  4921.0    0.05       0
  5362.7   0.075       0
Bank Sta=4917,4921
Exp/Cntr=0.3,0.1

Type RM Length L Ch R = 1,2162,268,268,268
BEGIN DESCRIPTION:
Unnamed Tributary to Walnut Creek 2K 8.0
END DESCRIPTION:
XS GIS Cut Line= 3
      2344479.02      7036810.01      2344729.00      7037010.00
      2345228.96      7036910.01
#Sta/Elev= 30
  4684.2  710.19  4712.2  708.61  4726.6  706.91  4761.8  705.81  4812.2  702.97
  4840.3  702.00  4848.3  702.55  4869.1  702.15  4883.5  700.13  4904.3  698.39
  4918.7  698.73  4999.1  697.88  4999.4  697.38  5002.9  697.38  5003.1  697.88
  5075.7  697.91  5126.7  698.87  5136.9  699.79  5187.9  700.97  5218.5  702.75
  5228.7  703.97  5238.9  703.95  5289.9  706.48  5310.3  706.67  5361.3  703.75
  5412.3  704.54  5445.3  706.64  5463.2  708.00  5493.8  707.81  5514.2  709.36
#Mann=4,-1,0
  4684.2    0.05       0  4999.1   0.033       0  5003.1    0.05       0
  5445.3   0.075       0
Bank Sta=4999.1,5003.1
Exp/Cntr=0.3,0.1

Type RM Length L Ch R = 1,1894,282,282,282
BEGIN DESCRIPTION:
Unnamed Tributary to Walnut Creek 2K 7.0
END DESCRIPTION:
XS GIS Cut Line= 3
      2344379.01      7036960.01      2344679.00      7037260.00
      2344979.02      7037159.99
#Sta/Elev= 30
  4576.3  706.64  4590.4  706.09  4604.6  705.01  4632.9  703.79  4647.0  702.73
  4703.6  700.27  4788.4  697.21  4816.7  696.66  4915.7  692.03  4944.0  691.44
  4958.1  690.25  5040.7  690.06  5041.0  689.56  5044.5  689.56  5044.7  690.06
  5074.3  690.10  5084.9  691.67  5095.4  692.22  5106.0  695.31  5116.5  694.67
  5127.0  693.14  5137.6  693.69  5148.1  694.91  5232.4  697.98  5253.5  699.26
  5274.6  700.05  5285.2  700.86  5306.2  704.03  5314.1  705.50  5316.8  705.50
#Mann=3,-1,0
  4576.3    0.05       0  5040.7   0.033       0  5044.7    0.05       0
Bank Sta=5040.7,5044.7
Exp/Cntr=0.3,0.1

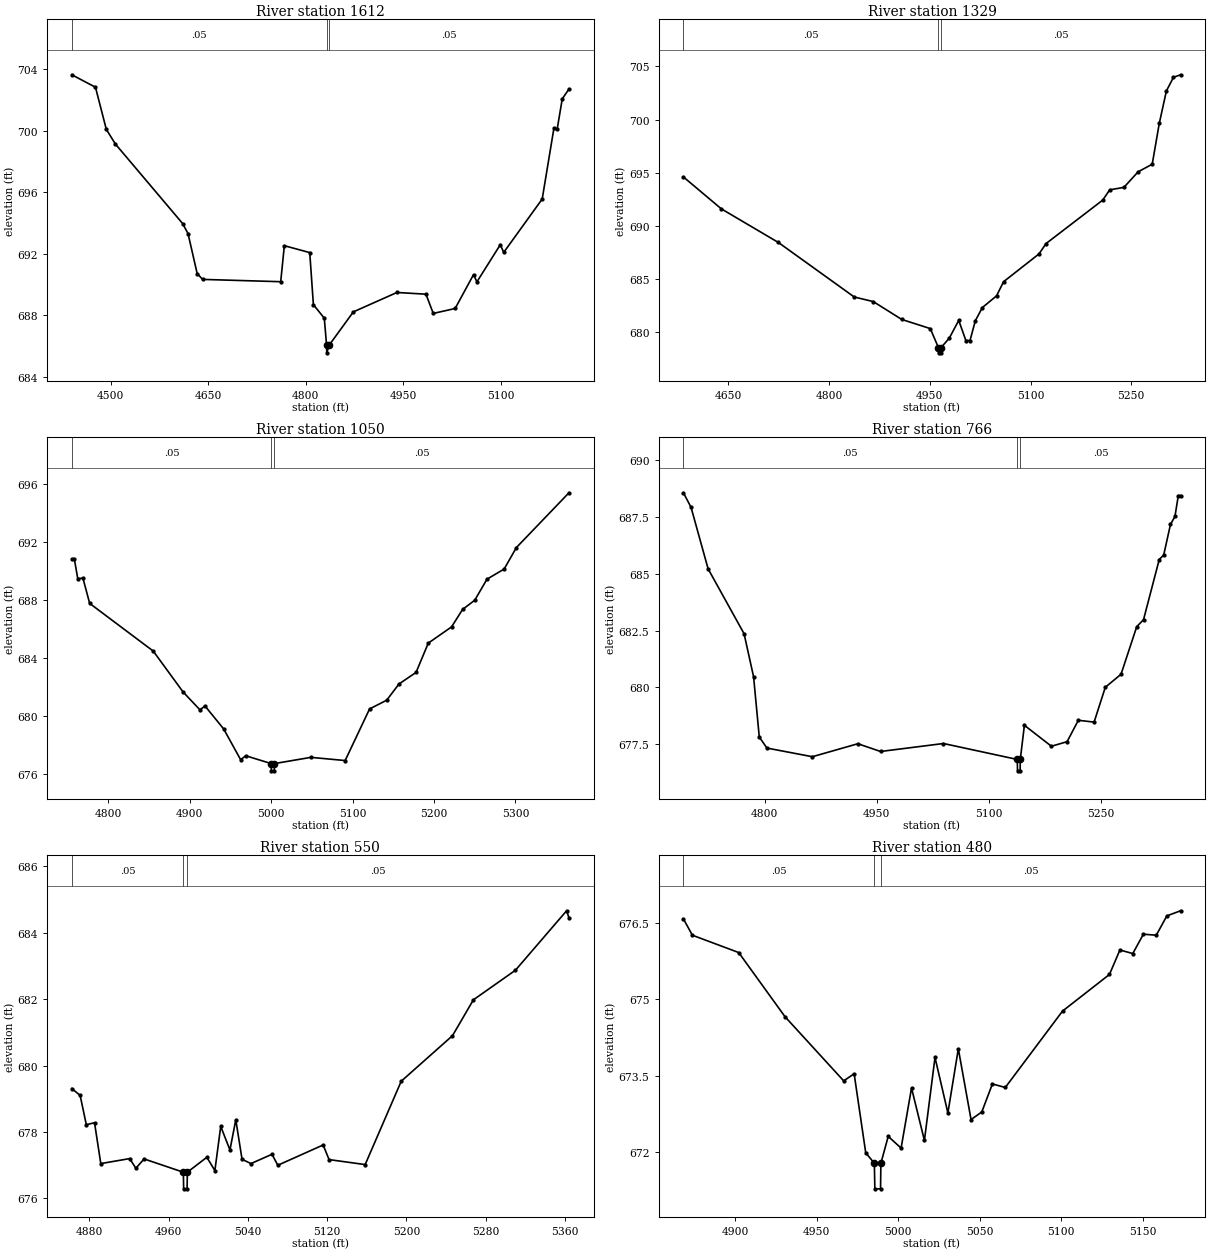
Type RM Length L Ch R = 1,1612,283,283,283
BEGIN DESCRIPTION:
Unnamed Tributary to Walnut Creek 2K 6.0
END DESCRIPTION:
XS GIS Cut Line= 3
      2344278.97      7037259.98      2344779.00      7037510.00
      2344978.99      7037460.00
#Sta/Elev= 30
  4440.1  703.62  4476.5  702.81  4493.2  700.07  4507.2  699.12  4610.6  693.96
  4619.0  693.30  4633.0  690.71  4641.4  690.33  4761.6  690.18  4767.2  692.52
  4806.3  692.07  4811.9  688.69  4828.7  687.81  4832.2  686.06  4832.5  685.56
  4836.2  686.06  4873.4  688.22  4940.5  689.48  4985.2  689.37  4996.4  688.12
  5030.1  688.44  5058.4  690.64  5063.6  690.17  5099.7  692.59  5104.8  692.08
  5164.1  695.55  5182.1  700.14  5187.3  700.13  5195.0  702.06  5205.3  702.69
#Mann=3,-1,0
  4440.1    0.05       0  4832.2   0.033       0  4836.2    0.05       0
Bank Sta=4832.2,4836.2
Exp/Cntr=0.3,0.1

Type RM Length L Ch R = 1,1329,279,279,279
BEGIN DESCRIPTION:
Unnamed Tributary to Walnut Creek 2K 5.0
END DESCRIPTION:
XS GIS Cut Line= 3
      2344379.02      7037460.02      2344679.00      7037760.00
      2344979.04      7037860.01
#Sta/Elev= 30
  4583.0  694.60  4639.5  691.60  4724.4  688.44  4837.5  683.31  4865.8  682.88
  4908.2  681.20  4950.7  680.34  4962.8  678.56  4963.1  678.06  4966.6  678.06
  4966.8  678.56  4978.9  679.43  4993.1  681.11  5003.7  679.22  5009.9  679.22
  5017.8  681.08  5028.3  682.32  5049.4  683.42  5059.9  684.75  5112.6  687.36
  5123.2  688.34  5207.5  692.42  5218.0  693.39  5239.1  693.62  5260.2  695.08
  5281.3  695.80  5291.8  699.64  5302.4  702.69  5312.9  703.97  5323.5  704.21
#Mann=3,-1,0
  4583.0    0.05       0  4962.8   0.033       0  4966.8    0.05       0
Bank Sta=4962.8,4966.8
Exp/Cntr=0.3,0.1

Type RM Length L Ch R = 1,1050,284,284,284
BEGIN DESCRIPTION:
Unnamed Tributary to Walnut Creek 2K 4.0
END DESCRIPTION:
XS GIS Cut Line= 3
      2344328.99      7037709.98      2344479.00      7037910.00
      2344779.02      7038110.01
#Sta/Elev= 30
  4755.2  690.81  4758.3  690.81  4762.5  689.46  4768.8  689.51  4777.1  687.76
  4855.2  684.47  4891.7  681.66  4912.5  680.42  4918.8  680.68  4941.7  679.10
  4962.5  676.98  4968.8  677.25  5000.1  676.71  5000.3  676.21  5003.8  676.21
  5004.1  676.71  5048.8  677.14  5090.9  676.92  5120.9  680.48  5141.9  681.08
  5157.0  682.20  5178.0  683.00  5193.0  685.02  5221.6  686.14  5235.1  687.34
  5250.1  687.98  5265.1  689.43  5286.2  690.13  5301.2  691.61  5365.8  695.39
#Mann=3,-1,0
  4755.2    0.05       0  5000.1   0.033       0  5004.1    0.05       0
Bank Sta=5000.1,5004.1
Exp/Cntr=0.3,0.1

Type RM Length L Ch R = 1,766,216,216,216
BEGIN DESCRIPTION:
Unnamed Tributary to Walnut Creek 2K 3.0
END DESCRIPTION:
XS GIS Cut Line= 3
      2344228.99      7037809.96      2344279.00      7038110.00
      2344578.97      7038309.98
#Sta/Elev= 30
  4691.4  688.55  4701.6  687.91  4724.4  685.21  4772.5  682.36  4785.2  680.47
  4792.8  677.83  4803.0  677.34  4863.8  676.96  4924.6  677.53  4955.0  677.19
  5039.1  677.54  5137.8  676.84  5138.1  676.34  5141.6  676.34  5141.8  676.84
  5147.3  678.34  5183.4  677.42  5204.4  677.62  5219.4  678.56  5240.5  678.48
  5255.5  680.01  5276.5  680.58  5297.5  682.67  5306.6  682.98  5327.6  685.62
  5333.6  685.82  5342.6  687.16  5348.6  687.51  5353.1  688.43  5356.1  688.43
#Mann=3,-1,0
  4691.4    0.05       0  5137.8   0.033       0  5141.8    0.05       0
Bank Sta=5137.8,5141.8
Exp/Cntr=0.3,0.1

Type RM Length L Ch R = 1,550,70,70,70
BEGIN DESCRIPTION:
Unnamed Tributary to Walnut Creek 2K 2.0
END DESCRIPTION:
XS GIS Cut Line= 3
      2344107.80      7038189.83      2344192.63      7038301.80
      2344497.37      7038495.38
#Sta/Elev= 30
  4862.4  679.31  4870.8  679.10  4877.0  678.22  4885.3  678.28  4891.6  677.05
  4920.7  677.20  4927.0  676.91  4935.3  677.19  4974.9  676.79  4975.2  676.29
  4978.7  676.29  4978.9  676.79  4998.6  677.24  5006.7  676.84  5012.6  678.17
  5021.9  677.46  5027.8  678.37  5034.1  677.18  5043.1  677.05  5064.3  677.33
  5070.2  677.00  5115.9  677.61  5121.9  677.17  5158.3  677.02  5194.7  679.53
  5246.4  680.90  5267.5  681.98  5309.9  682.87  5361.5  684.66  5363.9  684.45
#Mann=3,-1,0
  4862.4    0.05       0  4974.9   0.033       0  4978.9    0.05       0
Bank Sta=4974.9,4978.9
Exp/Cntr=0.3,0.1

Type RM Length L Ch R = 1,480,127,127,127
BEGIN DESCRIPTION:
Unnamed Tributary to Walnut Creek 2K 1.0
END DESCRIPTION:
XS GIS Cut Line= 3
      2344078.00      7038273.09      2344144.62      7038332.53
      2344280.95      7038499.58
#Sta/Elev= 30
  4868.2  676.58  4873.7  676.26  4902.1  675.92  4930.5  674.66  4966.5  673.40
  4972.9  673.54  4980.0  671.99  4985.3  671.78  4985.6  671.28  4989.1  671.28
  4989.3  671.78  4993.8  672.31  5001.7  672.08  5008.1  673.26  5016.0  672.23
  5022.5  673.86  5030.4  672.77  5036.8  674.03  5044.6  672.64  5051.2  672.79
  5057.7  673.34  5065.6  673.27  5100.7  674.77  5129.5  675.49  5135.9  675.97
  5143.8  675.90  5150.3  676.28  5158.2  676.26  5164.7  676.64  5173.1  676.74
#Mann=3,-1,0
  4868.2    0.05       0  4985.3   0.033       0  4989.3    0.05       0
Bank Sta=4985.3,4989.3
Exp/Cntr=0.3,0.1

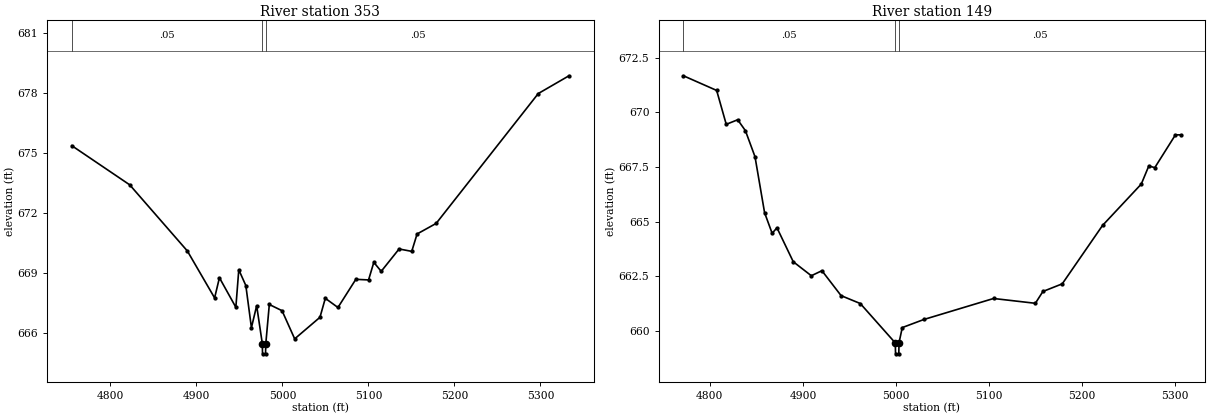
Type RM Length L Ch R = 1,353,204,204,204
BEGIN DESCRIPTION:
Unnamed Tributary to Walnut Creek 2K 0.5
END DESCRIPTION:
XS GIS Cut Line= 4
      2343948.74      7038209.63      2344033.23      7038380.54
      2344167.66      7038566.82      2344324.54      7038582.13
#Sta/Elev= 30
  4755.2  675.36  4822.5  673.40  4889.5  670.09  4921.2  667.74  4926.8  668.75
  4945.9  667.27  4949.3  669.15  4957.5  668.36  4964.0  666.25  4970.1  667.35
  4976.7  665.44  4976.9  664.94  4980.4  664.94  4980.7  665.44  4984.8  667.41
  4999.6  667.10  5014.3  665.69  5043.7  666.77  5049.9  667.72  5064.6  667.26
  5085.4  668.67  5100.2  668.64  5106.3  669.52  5114.9  669.07  5135.7  670.19
  5150.4  670.07  5156.6  670.94  5178.8  671.47  5297.5  677.97  5333.2  678.86
#Mann=3,-1,0
  4755.2    0.05       0  4976.7    0.04       0  4980.7    0.05       0
Bank Sta=4976.7,4980.7
Exp/Cntr=0.3,0.1

Type RM Length L Ch R = 1,149,0,0,0
BEGIN DESCRIPTION:
Unnamed Tributary to Walnut Creek 2K 0.2
END DESCRIPTION:
XS GIS Cut Line= 4
      2343946.82      7038315.23      2343896.88      7038524.57
      2343956.41      7038657.08      2344092.73      7038764.60
#Sta/Elev= 30
  4771.6  671.67  4807.3  671.00  4817.6  669.45  4829.9  669.66  4838.2  669.16
  4848.5  667.97  4858.8  665.41  4866.9  664.47  4872.1  664.72  4889.6  663.17
  4909.0  662.53  4920.4  662.76  4941.0  661.62  4961.6  661.26  4999.2  659.46
  4999.5  658.96  5003.0  658.96  5003.2  659.46  5006.7  660.16  5029.9  660.53
  5104.8  661.49  5149.7  661.27  5157.8  661.81  5178.6  662.16  5221.9  664.83
  5263.5  666.72  5271.6  667.55  5278.0  667.47  5300.2  668.97  5305.7  668.97
#Mann=3,-1,0
  4771.6    0.05       0  4999.2    0.04       0  5003.2    0.05       0
Bank Sta=4999.2,5003.2
Exp/Cntr=0.3,0.1

Chan Stop Cuts=-1