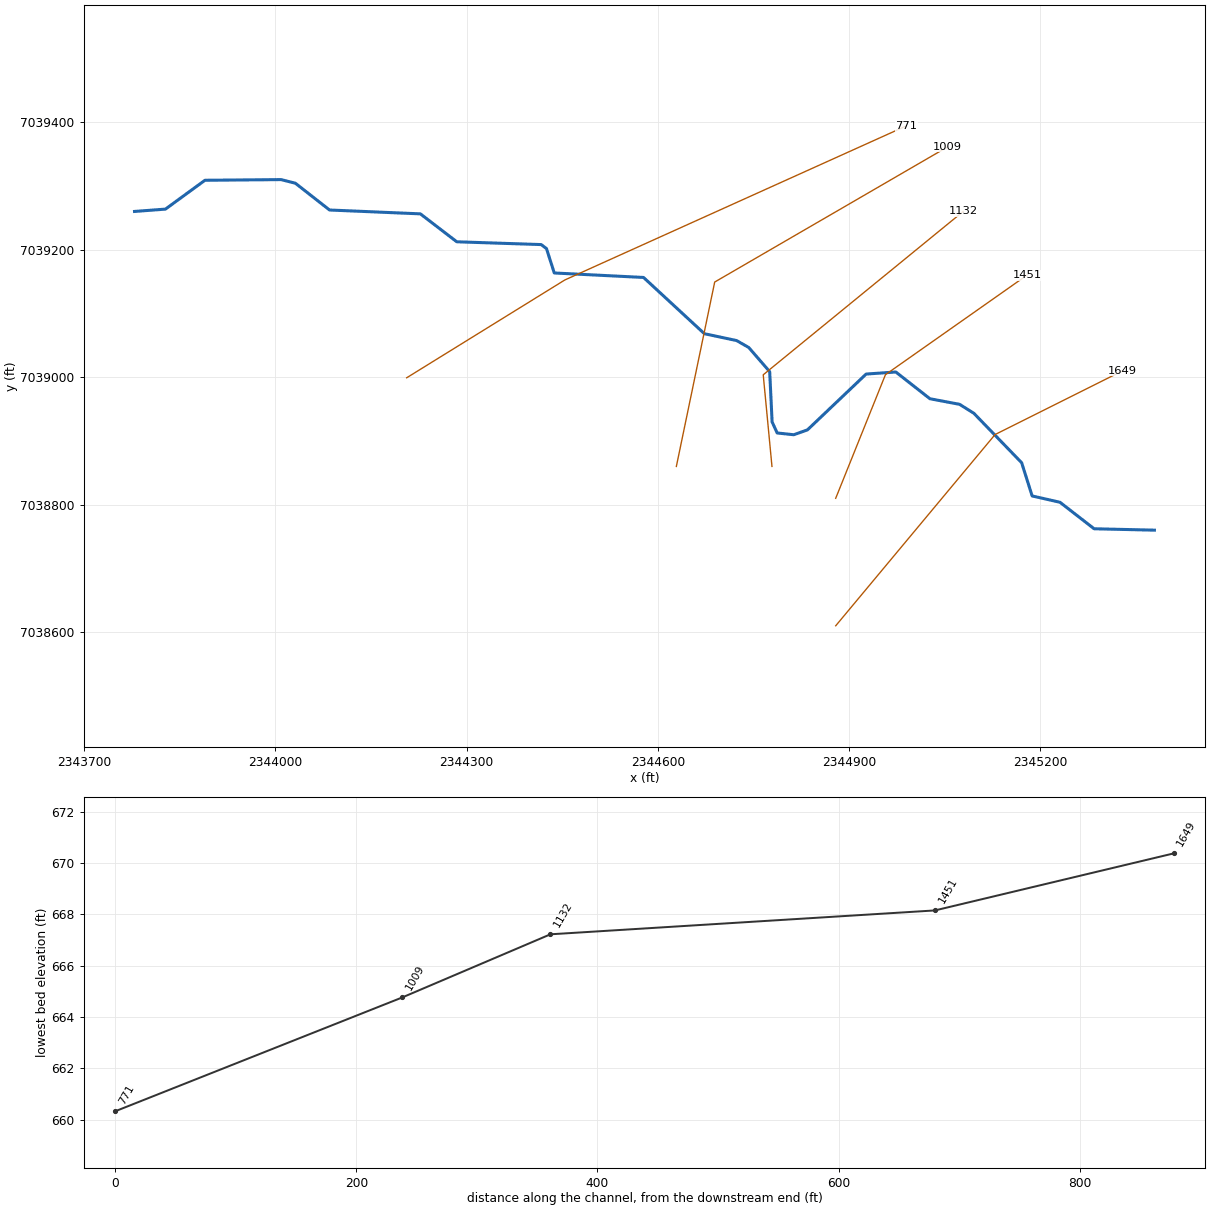
--- Unnamed Tr to Walnut Cr 2L.prj (project) ---

Proj Title=Unnamed Tr to Walnut Cr 2L Base Level Engineering
Current Plan=p01
Default Exp/Contr=0.3,0.1
English Units
Geom File=g01
Flow File=f01
Plan File=p01
BEGIN DESCRIPTION:
Unnamed Tr to Walnut Cr 2L
END DESCRIPTION:

--- Unnamed Tr to Walnut Cr 2L.p01 (plan) ---

Plan Title=Multiple Run
Short Identifier=Multiple
Geom File=g01
Flow File=f01
Subcritical Flow
K Sum by GR= 0
Std Step Tol= 0.01
Critical Tol= 0.01
Num of Std Step Trials= 20
Max Error Tol= 0.3
Flow Tol Ratio= 0.001
Split Flow NTrial= 30
Split Flow Tol= 0.02
Split Flow Ratio= 0.02
Log Output Level= 0
Friction Slope Method= 1
Unsteady Friction Slope Method= 2
Unsteady Bridges Friction Slope Method= 1
Parabolic Critical Depth
Global Vel Dist=  1 , 1 , 1
Global Log Level= 0
CheckData=True
Encroach Param= -1, 0, 0, 0
BEGIN DESCRIPTION:
Multiple Run
END DESCRIPTION:

--- Unnamed Tr to Walnut Cr 2L.f01 (steady flow) ---

Flow Title=Multiple
Number of Profiles=7
Profile Names=10-year,25-year,50-year,1pct_min,100-year,1pct_plu,500-year
River Rch & RM= Unnamed Tr to Wa,Reach-1,1649
     400     528     629     373     744    1480    1040
Boundary for River Rch & Prof#=Unnamed Tr to Wa,Reach-1,1
Up Type=0
Dn Type=3
Dn Slope=0.005
Boundary for River Rch & Prof#=Unnamed Tr to Wa,Reach-1,2
Up Type=0
Dn Type=3
Dn Slope=0.005
Boundary for River Rch & Prof#=Unnamed Tr to Wa,Reach-1,3
Up Type=0
Dn Type=3
Dn Slope=0.005
Boundary for River Rch & Prof#=Unnamed Tr to Wa,Reach-1,4
Up Type=0
Dn Type=3
Dn Slope=0.005
Boundary for River Rch & Prof#=Unnamed Tr to Wa,Reach-1,5
Up Type=0
Dn Type=3
Dn Slope=0.005
Boundary for River Rch & Prof#=Unnamed Tr to Wa,Reach-1,6
Up Type=0
Dn Type=3
Dn Slope=0.005
Boundary for River Rch & Prof#=Unnamed Tr to Wa,Reach-1,7
Up Type=0
Dn Type=3
Dn Slope=0.005

--- Unnamed Tr to Walnut Cr 2L.g01 (geometry) ---

Geom Title=Existing Conditions

River Reach=Unnamed Tr to Wa,Reach-1
Reach XY= 30
      2345379.00      7038760.00      2345284.43      7038762.18
      2345230.84      7038803.75      2345187.19      7038813.67
      2345170.72      7038865.77      2345095.71      7038943.37
      2345073.38      7038957.40      2345026.81      7038966.18
      2344973.28      7039008.12      2344926.71      7039004.90
      2344834.70      7038917.34      2344813.16      7038909.70
      2344787.17      7038912.46      2344779.22      7038929.77
      2344775.44      7039008.63      2344742.62      7039046.53
      2344723.57      7039057.44      2344672.98      7039068.19
      2344577.52      7039156.44      2344437.47      7039163.47
      2344425.26      7039201.71      2344417.03      7039208.02
      2344284.54      7039212.39      2344227.43      7039256.21
      2344084.94      7039262.27      2344031.33      7039304.26
      2344008.96      7039309.95      2343889.47      7039308.90
      2343827.49      7039263.65      2343779.00      7039260.00

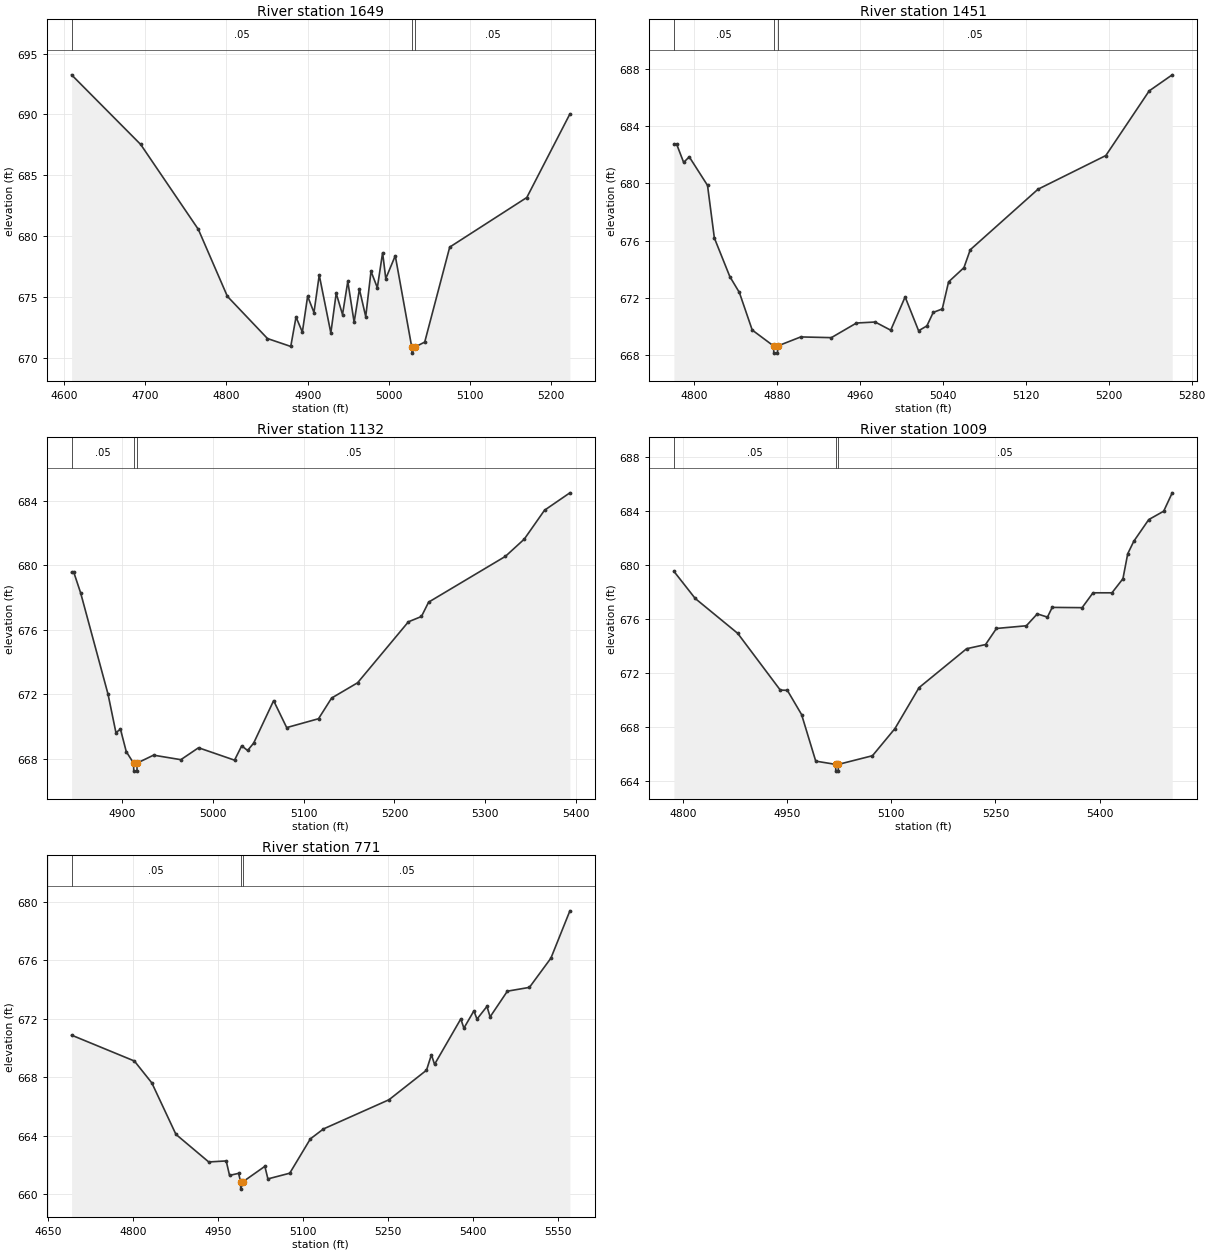
Type RM Length L Ch R = 1,1649,198,198,198
BEGIN DESCRIPTION:
Unnamed Tributary to Walnut Creek 2L 5.0
END DESCRIPTION:
XS GIS Cut Line= 3
      2344879.02      7038610.02      2345129.00      7038910.00
      2345329.00      7039010.00
#Sta/Elev= 30
  4609.1  693.26  4694.3  687.53  4765.3  680.55  4801.1  675.04  4850.5  671.57
  4879.2  670.92  4885.7  673.34  4893.5  672.10  4900.0  675.05  4907.8  673.71
  4914.3  676.79  4928.6  672.03  4935.2  675.29  4943.0  673.54  4949.5  676.27
  4957.3  672.91  4963.8  675.63  4971.6  673.37  4978.1  677.10  4985.9  675.75
  4992.4  678.63  4996.3  676.50  5008.0  678.38  5028.3  670.87  5028.6  670.37
  5032.3  670.87  5044.3  671.28  5075.1  679.09  5170.1  683.17  5223.2  690.04
#Mann=3,-1,0
  4609.1    0.05       0  5028.3    0.04       0  5032.3    0.05       0
Bank Sta=5028.3,5032.3
Exp/Cntr=0.3,0.1

Type RM Length L Ch R = 1,1451,319,319,319
BEGIN DESCRIPTION:
Unnamed Tributary to Walnut Creek 2L 4.0
END DESCRIPTION:
XS GIS Cut Line= 3
      2344878.99      7038809.99      2344957.02      7039003.90
      2345179.01      7039160.00
#Sta/Elev= 30
  4780.8  682.71  4783.5  682.71  4790.2  681.45  4795.6  681.84  4813.2  679.85
  4819.8  676.18  4834.7  673.49  4843.9  672.38  4856.3  669.76  4876.9  668.65
  4877.1  668.15  4880.6  668.15  4880.9  668.65  4903.1  669.28  4932.6  669.23
  4956.8  670.25  4974.8  670.32  4989.8  669.75  5003.7  672.07  5016.7  669.71
  5024.7  670.05  5030.8  670.99  5039.5  671.23  5045.6  673.12  5060.4  674.11
  5066.5  675.36  5131.8  679.58  5197.2  681.93  5239.0  686.44  5261.2  687.56
#Mann=3,-1,0
  4780.8    0.05       0  4876.9    0.04       0  4880.9    0.05       0
Bank Sta=4876.9,4880.9
Exp/Cntr=0.3,0.1

Type RM Length L Ch R = 1,1132,123,123,123
BEGIN DESCRIPTION:
Unnamed Tributary to Walnut Creek 2L 3.0
END DESCRIPTION:
XS GIS Cut Line= 3
      2344779.00      7038860.00      2344765.29      7039003.74
      2345079.03      7039260.02
#Sta/Elev= 30
  4844.0  679.54  4846.5  679.54  4854.0  678.27  4884.2  671.99  4892.9  669.61
  4897.9  669.82  4904.3  668.43  4912.3  667.72  4912.6  667.22  4916.1  667.22
  4916.3  667.72  4934.4  668.21  4964.5  667.93  4984.0  668.67  5023.7  667.90
  5031.6  668.79  5038.1  668.50  5044.8  668.96  5066.8  671.59  5081.2  669.92
  5116.3  670.47  5130.7  671.75  5159.4  672.70  5215.4  676.48  5229.8  676.81
  5237.7  677.70  5322.4  680.54  5343.2  681.61  5365.5  683.40  5393.5  684.48
#Mann=3,-1,0
  4844.0    0.05       0  4912.3   0.033       0  4916.3    0.05       0
Bank Sta=4912.3,4916.3
Exp/Cntr=0.3,0.1

Type RM Length L Ch R = 1,1009,238,238,238
BEGIN DESCRIPTION:
Unnamed Tributary to Walnut Creek 2L 2.0
END DESCRIPTION:
XS GIS Cut Line= 3
      2344629.00      7038859.98      2344689.16      7039149.24
      2345054.45      7039361.24
#Sta/Elev= 30
  4786.9  679.55  4817.6  677.54  4878.8  674.96  4940.1  670.76  4950.3  670.74
  4970.8  668.95  4991.2  665.50  5019.8  665.26  5020.1  664.76  5023.6  664.76
  5023.8  665.26  5072.9  665.90  5105.3  667.91  5140.0  670.94  5208.5  673.82
  5235.8  674.13  5251.5  675.32  5294.6  675.52  5310.3  676.40  5325.0  676.16
  5331.8  676.88  5374.9  676.86  5390.6  677.96  5417.9  677.96  5433.7  679.00
  5440.6  680.85  5449.4  681.78  5470.9  683.38  5492.4  684.00  5504.7  685.36
#Mann=3,-1,0
  4786.9    0.05       0  5019.8    0.04       0  5023.8    0.05       0
Bank Sta=5019.8,5023.8
Exp/Cntr=0.3,0.1

Type RM Length L Ch R = 1,771,0,0,0
BEGIN DESCRIPTION:
Unnamed Tributary to Walnut Creek 2L 1.0
END DESCRIPTION:
XS GIS Cut Line= 3
      2344205.98      7038999.07      2344454.08      7039152.51
      2344989.58      7039394.13
#Sta/Elev= 30
  4691.2  670.87  4802.0  669.10  4832.8  667.60  4875.3  664.08  4933.2  662.19
  4964.0  662.26  4969.9  661.27  4985.9  661.41  4989.4  660.83  4989.6  660.33
  4993.4  660.83  5032.2  661.89  5037.6  661.03  5076.1  661.42  5112.5  663.77
  5135.6  664.45  5251.3  666.45  5317.4  668.47  5326.1  669.53  5331.6  668.87
  5377.9  671.98  5383.4  671.35  5401.0  672.53  5406.5  671.97  5424.1  672.84
  5429.6  672.12  5460.1  673.88  5499.0  674.14  5536.9  676.14  5570.4  679.38
#Mann=3,-1,0
  4691.2    0.05       0  4989.4   0.033       0  4993.4    0.05       0
Bank Sta=4989.4,4993.4
Exp/Cntr=0.3,0.1

Chan Stop Cuts=-1