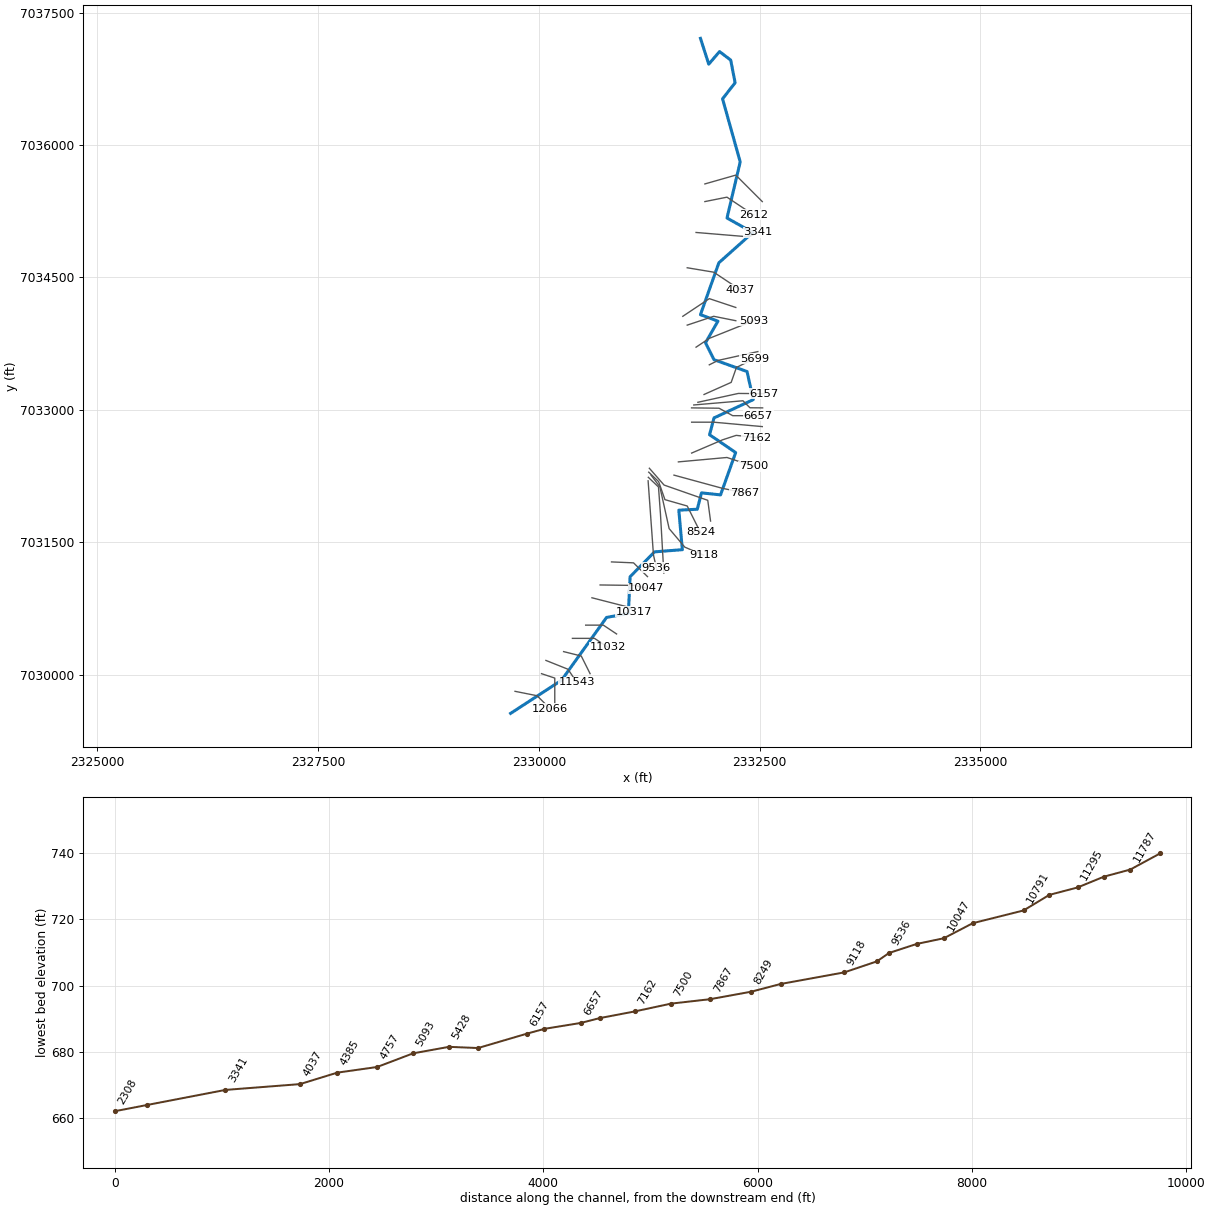
--- Unnamed Tr to Walnut Cr 2M.prj (project) ---

Proj Title=Unnamed Tr to Walnut Cr 2M Base Level Engineering
Current Plan=p01
Default Exp/Contr=0.3,0.1
English Units
Geom File=g01
Flow File=f01
Plan File=p01
BEGIN DESCRIPTION:
Unnamed Tr to Walnut Cr 2M
END DESCRIPTION:

--- Unnamed Tr to Walnut Cr 2M.p01 (plan) ---

Plan Title=Multiple Run
Short Identifier=Multiple
Geom File=g01
Flow File=f01
Subcritical Flow
K Sum by GR= 0
Std Step Tol= 0.01
Critical Tol= 0.01
Num of Std Step Trials= 20
Max Error Tol= 0.3
Flow Tol Ratio= 0.001
Split Flow NTrial= 30
Split Flow Tol= 0.02
Split Flow Ratio= 0.02
Log Output Level= 0
Friction Slope Method= 1
Unsteady Friction Slope Method= 2
Unsteady Bridges Friction Slope Method= 1
Parabolic Critical Depth
Global Vel Dist=  1 , 1 , 1
Global Log Level= 0
CheckData=True
Encroach Param= -1, 0, 0, 0
BEGIN DESCRIPTION:
Multiple Run
END DESCRIPTION:

--- Unnamed Tr to Walnut Cr 2M.f01 (steady flow) ---

Flow Title=Multiple
Number of Profiles=7
Profile Names=10-year,25-year,50-year,1pct_min,100-year,1pct_plu,500-year
River Rch & RM= Unnamed Tr to Wa,Reach-1,12066
     412     551     664     397     793    1580    1130
River Rch & RM= Unnamed Tr to Wa,Reach-1,10317
     617     846    1040     629    1260    2500    1840
River Rch & RM= Unnamed Tr to Wa,Reach-1,7867
     660     905    1110     672    1340    2670    1960
River Rch & RM= Unnamed Tr to Wa,Reach-1,1799
     862    1200    1480     908    1810    3610    2700
Boundary for River Rch & Prof#=Unnamed Tr to Wa,Reach-1,1
Up Type=0
Dn Type=3
Dn Slope=0.005
Boundary for River Rch & Prof#=Unnamed Tr to Wa,Reach-1,2
Up Type=0
Dn Type=3
Dn Slope=0.005
Boundary for River Rch & Prof#=Unnamed Tr to Wa,Reach-1,3
Up Type=0
Dn Type=3
Dn Slope=0.005
Boundary for River Rch & Prof#=Unnamed Tr to Wa,Reach-1,4
Up Type=0
Dn Type=3
Dn Slope=0.005
Boundary for River Rch & Prof#=Unnamed Tr to Wa,Reach-1,5
Up Type=0
Dn Type=3
Dn Slope=0.005
Boundary for River Rch & Prof#=Unnamed Tr to Wa,Reach-1,6
Up Type=0
Dn Type=3
Dn Slope=0.005
Boundary for River Rch & Prof#=Unnamed Tr to Wa,Reach-1,7
Up Type=0
Dn Type=3
Dn Slope=0.005

--- Unnamed Tr to Walnut Cr 2M.g01 (geometry) ---

Geom Title=Existing Conditions

River Reach=Unnamed Tr to Wa,Reach-1
Reach XY= 30
      2329679.00      7029560.00      2330255.98      7029935.65
      2330765.29      7030647.02      2331012.37      7030693.28
      2331032.12      7031108.38      2331308.80      7031390.39
      2331623.59      7031415.11      2331583.97      7031862.59
      2331792.81      7031873.36      2331840.67      7032058.97
      2332056.34      7032035.95      2332227.51      7032515.85
      2331931.66      7032717.86      2331982.61      7032908.52
      2332426.83      7033115.43      2332356.27      7033434.13
      2331982.35      7033568.06      2331886.08      7033760.02
      2332026.93      7034004.75      2331828.67      7034078.50
      2332037.13      7034666.08      2332421.72      7035009.90
      2332129.48      7035173.69      2332279.00      7035810.00
      2332079.02      7036524.38      2332221.39      7036706.67
      2332171.21      7036963.44      2332044.79      7037059.93
      2331922.69      7036917.34      2331829.00      7037210.00

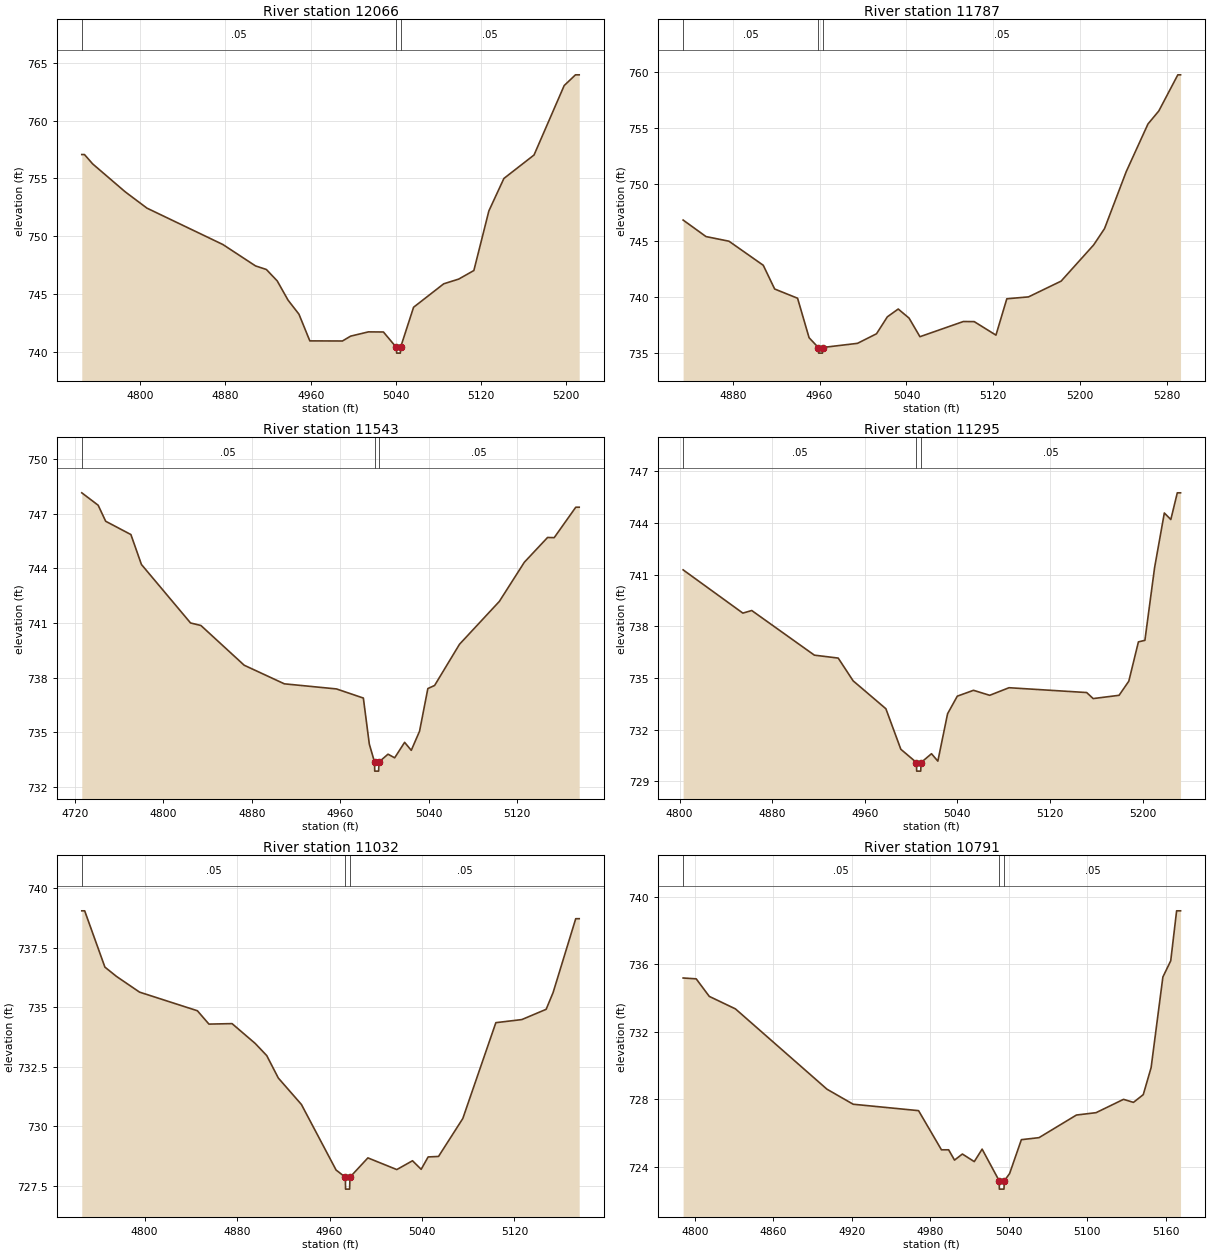
Type RM Length L Ch R = 1,12066,279,279,279
BEGIN DESCRIPTION:
Unnamed Tributary to Walnut Creek 2M 29.0
END DESCRIPTION:
XS GIS Cut Line= 3
      2329729.03      7029809.99      2329979.00      7029760.00
      2330128.97      7029610.03
#Sta/Elev= 30
  4745.1  757.07  4747.6  757.07  4755.3  756.26  4785.9  753.84  4806.3  752.43
  4877.6  749.28  4908.2  747.43  4918.4  747.12  4928.6  746.13  4938.8  744.46
  4949.0  743.25  4959.2  740.94  4989.8  740.93  4997.5  741.35  5014.2  741.72
  5028.3  741.71  5040.4  740.38  5040.7  739.88  5044.2  739.88  5044.4  740.38
  5056.6  743.85  5084.9  745.88  5099.0  746.29  5113.2  747.03  5127.3  752.19
  5141.4  755.00  5169.7  757.03  5198.0  763.04  5208.6  763.97  5212.1  763.97
#Mann=3,-1,0
  4745.1    0.05       0  5040.4    0.04       0  5044.4    0.05       0
Bank Sta=5040.4,5044.4
Exp/Cntr=0.3,0.1

Type RM Length L Ch R = 1,11787,244,244,244
BEGIN DESCRIPTION:
Unnamed Tributary to Walnut Creek 2M 28.0
END DESCRIPTION:
XS GIS Cut Line= 3
      2330028.98      7030010.01      2330179.00      7029960.00
      2330179.00      7029660.03
#Sta/Elev= 30
  4834.3  746.83  4855.4  745.36  4876.5  744.95  4908.1  742.81  4918.6  740.70
  4939.7  739.88  4950.3  736.37  4958.8  735.50  4959.1  735.00  4962.6  735.00
  4962.8  735.50  4994.9  735.87  5012.4  736.72  5022.4  738.23  5032.4  738.92
  5042.4  738.11  5052.4  736.46  5092.4  737.81  5102.4  737.80  5122.4  736.60
  5132.4  739.83  5152.4  740.00  5182.4  741.40  5212.4  744.62  5222.4  746.07
  5242.4  751.14  5262.4  755.37  5272.4  756.53  5289.9  759.74  5292.4  759.74
#Mann=3,-1,0
  4834.3    0.05       0  4958.8   0.033       0  4962.8    0.05       0
Bank Sta=4958.8,4962.8
Exp/Cntr=0.3,0.1

Type RM Length L Ch R = 1,11543,248,248,248
BEGIN DESCRIPTION:
Unnamed Tributary to Walnut Creek 2M 27.0
END DESCRIPTION:
XS GIS Cut Line= 3
      2330078.98      7030160.01      2330329.00      7030060.00
      2330429.03      7029909.96
#Sta/Elev= 30
  4726.4  748.15  4741.2  747.47  4748.0  746.59  4770.8  745.86  4780.3  744.22
  4824.7  741.01  4834.1  740.87  4873.2  738.69  4909.5  737.67  4956.6  737.39
  4980.9  736.89  4986.3  734.36  4991.0  733.38  4991.2  732.88  4994.7  732.88
  4995.0  733.38  5003.2  733.81  5009.2  733.61  5018.2  734.46  5024.2  734.02
  5031.7  735.07  5039.2  737.41  5045.3  737.58  5067.8  739.84  5103.8  742.19
  5126.4  744.34  5147.4  745.70  5153.4  745.69  5172.9  747.36  5176.0  747.36
#Mann=3,-1,0
  4726.4    0.05       0  4991.0    0.04       0  4995.0    0.05       0
Bank Sta=4991,4995
Exp/Cntr=0.3,0.1

Type RM Length L Ch R = 1,11295,263,263,263
BEGIN DESCRIPTION:
Unnamed Tributary to Walnut Creek 2M 26.0
END DESCRIPTION:
XS GIS Cut Line= 3
      2330278.99      7030260.00      2330479.00      7030210.00
      2330579.01      7030009.98
#Sta/Elev= 30
  4803.0  741.28  4854.6  738.77  4862.3  738.92  4916.4  736.33  4937.0  736.16
  4949.9  734.84  4978.2  733.22  4991.1  730.87  5004.6  730.10  5004.8  729.60
  5008.3  729.60  5008.6  730.10  5017.6  730.61  5023.1  730.18  5031.5  732.93
  5039.9  733.95  5053.9  734.29  5067.9  734.00  5084.6  734.44  5151.7  734.16
  5157.3  733.81  5179.7  734.00  5188.1  734.82  5196.4  737.10  5202.0  737.19
  5210.4  741.42  5218.8  744.58  5224.4  744.20  5230.0  745.75  5232.8  745.75
#Mann=3,-1,0
  4803.0    0.05       0  5004.6    0.04       0  5008.6    0.05       0
Bank Sta=5004.6,5008.6
Exp/Cntr=0.3,0.1

Type RM Length L Ch R = 1,11032,241,241,241
BEGIN DESCRIPTION:
Unnamed Tributary to Walnut Creek 2M 25.0
END DESCRIPTION:
XS GIS Cut Line= 3
      2330379.01      7030410.00      2330629.00      7030410.00
      2330779.02      7030309.98
#Sta/Elev= 30
  4745.7  739.04  4748.2  739.04  4765.7  736.68  4775.7  736.29  4795.7  735.63
  4845.7  734.85  4855.7  734.29  4875.7  734.31  4895.7  733.48  4905.7  732.97
  4915.7  732.03  4935.7  730.92  4965.7  728.17  4973.7  727.87  4973.9  727.37
  4977.4  727.37  4977.7  727.87  4993.2  728.68  5018.2  728.19  5031.8  728.56
  5039.3  728.20  5045.3  728.72  5054.3  728.74  5075.3  730.33  5103.9  734.35
  5126.4  734.48  5147.4  734.91  5153.4  735.61  5173.0  738.71  5176.0  738.71
#Mann=3,-1,0
  4745.7    0.05       0  4973.7   0.033       0  4977.7    0.05       0
Bank Sta=4973.7,4977.7
Exp/Cntr=0.3,0.1

Type RM Length L Ch R = 1,10791,474,474,474
BEGIN DESCRIPTION:
Unnamed Tributary to Walnut Creek 2M 24.0
END DESCRIPTION:
XS GIS Cut Line= 3
      2330528.97      7030560.00      2330729.00      7030560.00
      2330879.00      7030460.00
#Sta/Elev= 30
  4791.1  735.18  4801.1  735.13  4811.1  734.09  4831.1  733.35  4901.1  728.59
  4921.1  727.70  4971.1  727.32  4988.6  725.00  4994.1  725.00  4998.6  724.39
  5004.6  724.75  5013.7  724.30  5019.7  725.04  5032.7  723.17  5032.9  722.67
  5036.4  722.67  5036.7  723.17  5040.7  723.59  5049.7  725.60  5063.2  725.72
  5091.8  727.06  5106.8  727.20  5127.8  727.99  5135.4  727.81  5142.9  728.27
  5148.9  729.87  5157.9  735.24  5163.9  736.20  5168.4  739.16  5171.4  739.16
#Mann=3,-1,0
  4791.1    0.05       0  5032.7   0.033       0  5036.7    0.05       0
Bank Sta=5032.7,5036.7
Exp/Cntr=0.3,0.1

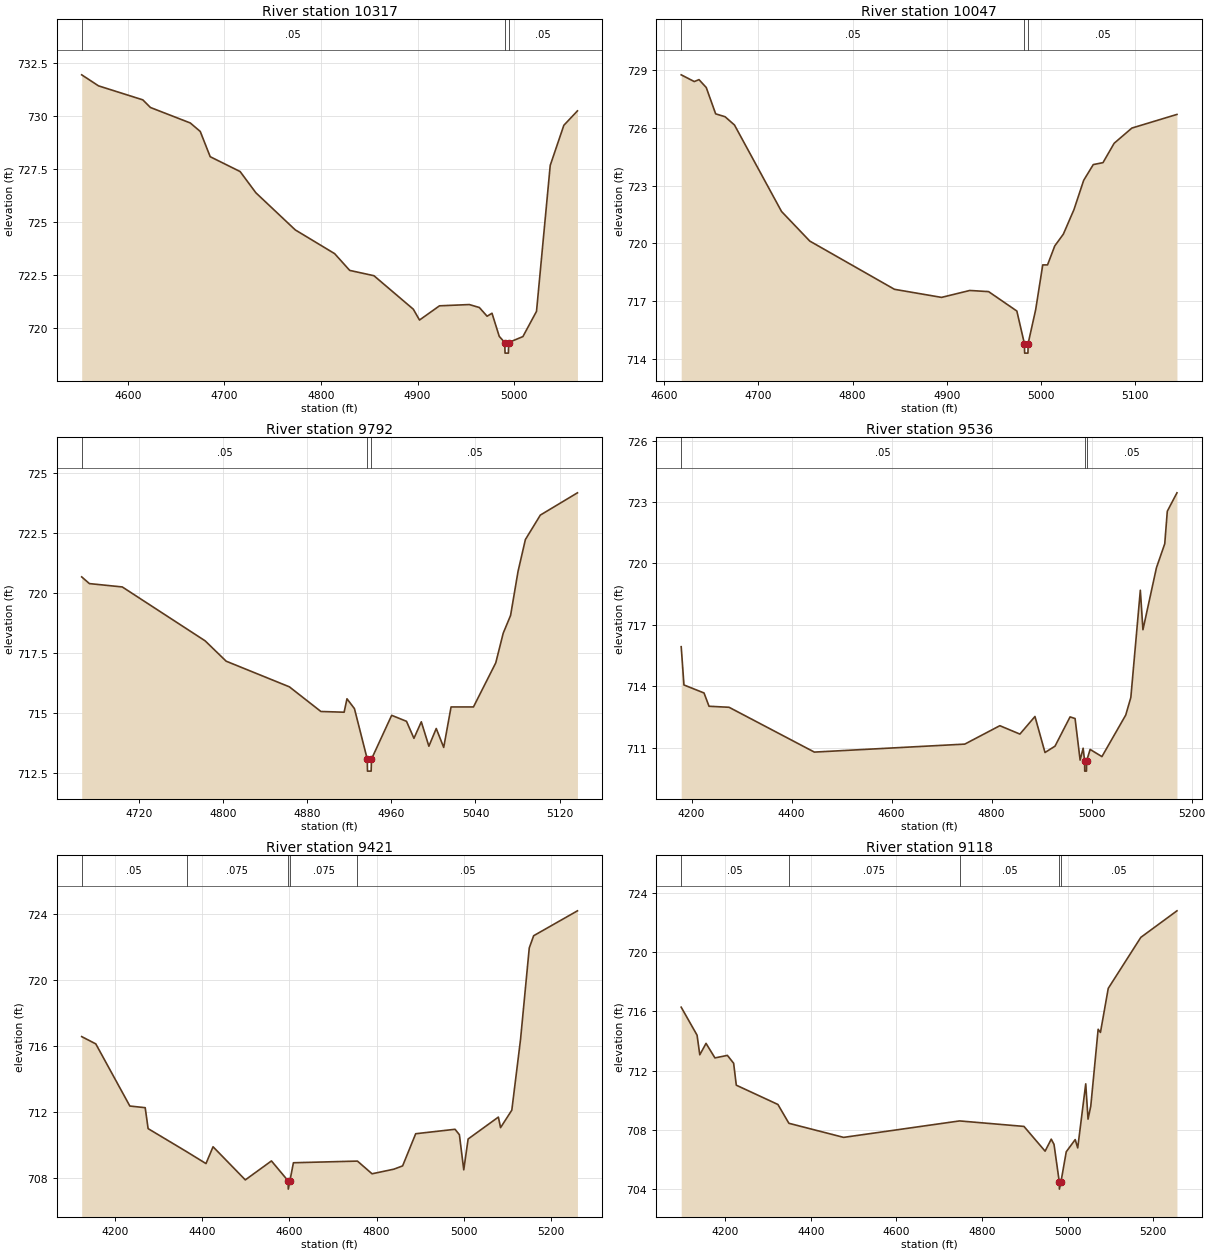
Type RM Length L Ch R = 1,10317,270,270,270
BEGIN DESCRIPTION:
Unnamed Tributary to Walnut Creek 2M 23.0
END DESCRIPTION:
XS GIS Cut Line= 3
      2330600.07      7030870.07      2331029.00      7030760.00
      2331078.98      7030710.02
#Sta/Elev= 30
  4552.1  731.95  4569.5  731.43  4615.4  730.77  4623.3  730.41  4664.6  729.68
  4674.9  729.28  4685.2  728.09  4716.2  727.39  4732.5  726.39  4773.3  724.64
  4814.1  723.52  4829.7  722.73  4854.8  722.48  4895.6  720.90  4902.0  720.39
  4922.7  721.06  4953.6  721.12  4964.0  720.98  4972.0  720.57  4977.1  720.71
  4984.6  719.62  4990.3  719.33  4990.6  718.83  4994.1  718.83  4994.3  719.33
  5009.1  719.61  5023.2  720.80  5037.4  727.68  5051.5  729.57  5065.6  730.25
#Mann=3,-1,0
  4552.1    0.05       0  4990.3   0.033       0  4994.3    0.05       0
Bank Sta=4990.3,4994.3
Exp/Cntr=0.3,0.1

Type RM Length L Ch R = 1,10047,255,255,255
BEGIN DESCRIPTION:
Unnamed Tributary to Walnut Creek 2M 22.0
END DESCRIPTION:
XS GIS Cut Line= 3
      2330692.41      7031015.22      2331079.00      7031010.00
      2331215.81      7030979.97
#Sta/Elev= 30
  4618.0  728.77  4631.9  728.42  4636.9  728.52  4644.6  728.11  4654.6  726.74
  4664.6  726.59  4674.6  726.16  4724.6  721.66  4754.6  720.12  4844.6  717.61
  4894.6  717.19  4924.6  717.55  4944.6  717.49  4974.6  716.48  4982.6  714.79
  4982.9  714.29  4986.4  714.29  4986.6  714.79  4994.6  716.55  5002.1  718.88
  5007.2  718.88  5014.9  719.87  5024.0  720.48  5035.3  721.76  5045.6  723.28
  5055.8  724.10  5066.1  724.20  5078.0  725.21  5096.8  726.00  5144.7  726.71
#Mann=3,-1,0
  4618.0    0.05       0  4982.6   0.033       0  4986.6    0.05       0
Bank Sta=4982.6,4986.6
Exp/Cntr=0.3,0.1

Type RM Length L Ch R = 1,9792,256,256,256
BEGIN DESCRIPTION:
Unnamed Tributary to Walnut Creek 2M 21.0
END DESCRIPTION:
XS GIS Cut Line= 3
      2330821.68      7031276.47      2331071.09      7031265.91
      2331228.97      7031110.03
#Sta/Elev= 30
  4665.5  720.67  4672.8  720.39  4704.1  720.25  4782.9  718.00  4802.9  717.15
  4863.0  716.08  4893.0  715.05  4915.1  715.02  4917.8  715.58  4924.9  715.17
  4937.1  713.06  4937.3  712.56  4940.8  712.56  4941.1  713.06  4960.3  714.89
  4974.4  714.64  4981.5  713.93  4988.5  714.62  4995.7  713.60  5002.7  714.34
  5009.8  713.55  5016.8  715.24  5038.1  715.24  5059.3  717.08  5066.4  718.32
  5073.4  719.06  5080.5  720.90  5087.5  722.23  5101.7  723.25  5137.0  724.18
#Mann=3,-1,0
  4665.5    0.05       0  4937.1   0.033       0  4941.1    0.05       0
Bank Sta=4937.1,4941.1
Exp/Cntr=0.3,0.1

Type RM Length L Ch R = 1,9536,115,115,115
BEGIN DESCRIPTION:
Unnamed Tributary to Walnut Creek 2M 20.0
END DESCRIPTION:
XS GIS Cut Line= 3
      2331236.08      7032195.49      2331296.64      7031356.45
      2331329.00      7031210.01
#Sta/Elev= 30
  4179.3  715.93  4184.8  714.06  4224.9  713.67  4234.9  713.02  4275.0  712.97
  4445.5  710.78  4746.3  711.17  4816.4  712.07  4856.5  711.66  4886.6  712.52
  4906.7  710.76  4926.7  711.07  4956.8  712.50  4966.8  712.42  4976.9  710.39
  4982.9  710.97  4985.9  710.35  4986.1  709.85  4989.6  709.85  4989.9  710.35
  4996.9  710.91  5020.5  710.56  5068.1  712.59  5078.3  713.45  5097.3  718.69
  5102.5  716.76  5129.5  719.79  5146.1  720.96  5151.2  722.55  5170.5  723.45
#Mann=3,-1,0
  4179.3    0.05       0  4985.9   0.033       0  4989.9    0.05       0
Bank Sta=4985.9,4989.9
Exp/Cntr=0.3,0.1

Type RM Length L Ch R = 1,9421,303,303,303
BEGIN DESCRIPTION:
UNT Wal 2M 19.5
END DESCRIPTION:
XS GIS Cut Line= 4
      2331238.41      7032235.21      2331353.57      7032125.71
      2331375.57      7031824.04      2331414.10      7031149.72
#Sta/Elev= 30
  4123.9  716.55  4156.2  716.11  4234.3  712.34  4269.5  712.24  4276.2  710.97
  4364.6  709.57  4408.9  708.85  4425.1  709.87  4499.1  707.86  4559.0  709.01
  4597.3  707.80  4597.6  707.30  4601.3  707.80  4609.4  708.90  4756.2  709.00
  4789.7  708.23  4839.7  708.51  4859.8  708.71  4889.8  710.66  4980.0  710.93
  4990.0  710.60  5000.0  708.47  5010.0  710.34  5079.4  711.67  5084.4  711.03
  5110.2  712.09  5130.2  716.38  5150.2  721.93  5160.3  722.67  5260.7  724.18
#Mann=5,-1,0
  4123.9    0.05       0  4364.6   0.075       0  4597.3    0.05       0
  4601.3   0.075       0  4756.2    0.05       0
Bank Sta=4597.3,4601.3
Exp/Cntr=0.3,0.1

Type RM Length L Ch R = 1,9118,594,594,594
BEGIN DESCRIPTION:
Unnamed Tributary to Walnut Creek 2M 19.0
END DESCRIPTION:
XS GIS Cut Line= 5
      2331268.79      7032260.85      2331369.15      7032127.82
      2331474.20      7031653.93      2331651.62      7031443.82
      2331864.00      7031352.80
#Sta/Elev= 30
  4097.3  716.27  4134.4  714.38  4140.7  713.06  4155.3  713.83  4176.1  712.85
  4205.2  713.02  4219.8  712.49  4226.0  711.01  4323.2  709.71  4348.9  708.44
  4476.8  707.49  4747.6  708.60  4898.0  708.23  4947.4  706.56  4961.7  707.37
  4968.2  707.02  4980.5  704.50  4980.8  704.00  4984.5  704.50  4996.8  706.52
  5017.7  707.34  5023.6  706.78  5042.3  711.10  5047.7  708.72  5054.1  709.60
  5071.3  714.78  5076.7  714.57  5094.9  717.54  5171.0  720.98  5255.4  722.77
#Mann=5,-1,0
  4097.3    0.05       0  4348.9   0.075       0  4747.6    0.05       0
  4980.5   0.033       0  4984.5    0.05       0
Bank Sta=4980.5,4984.5
Exp/Cntr=0.3,0.1

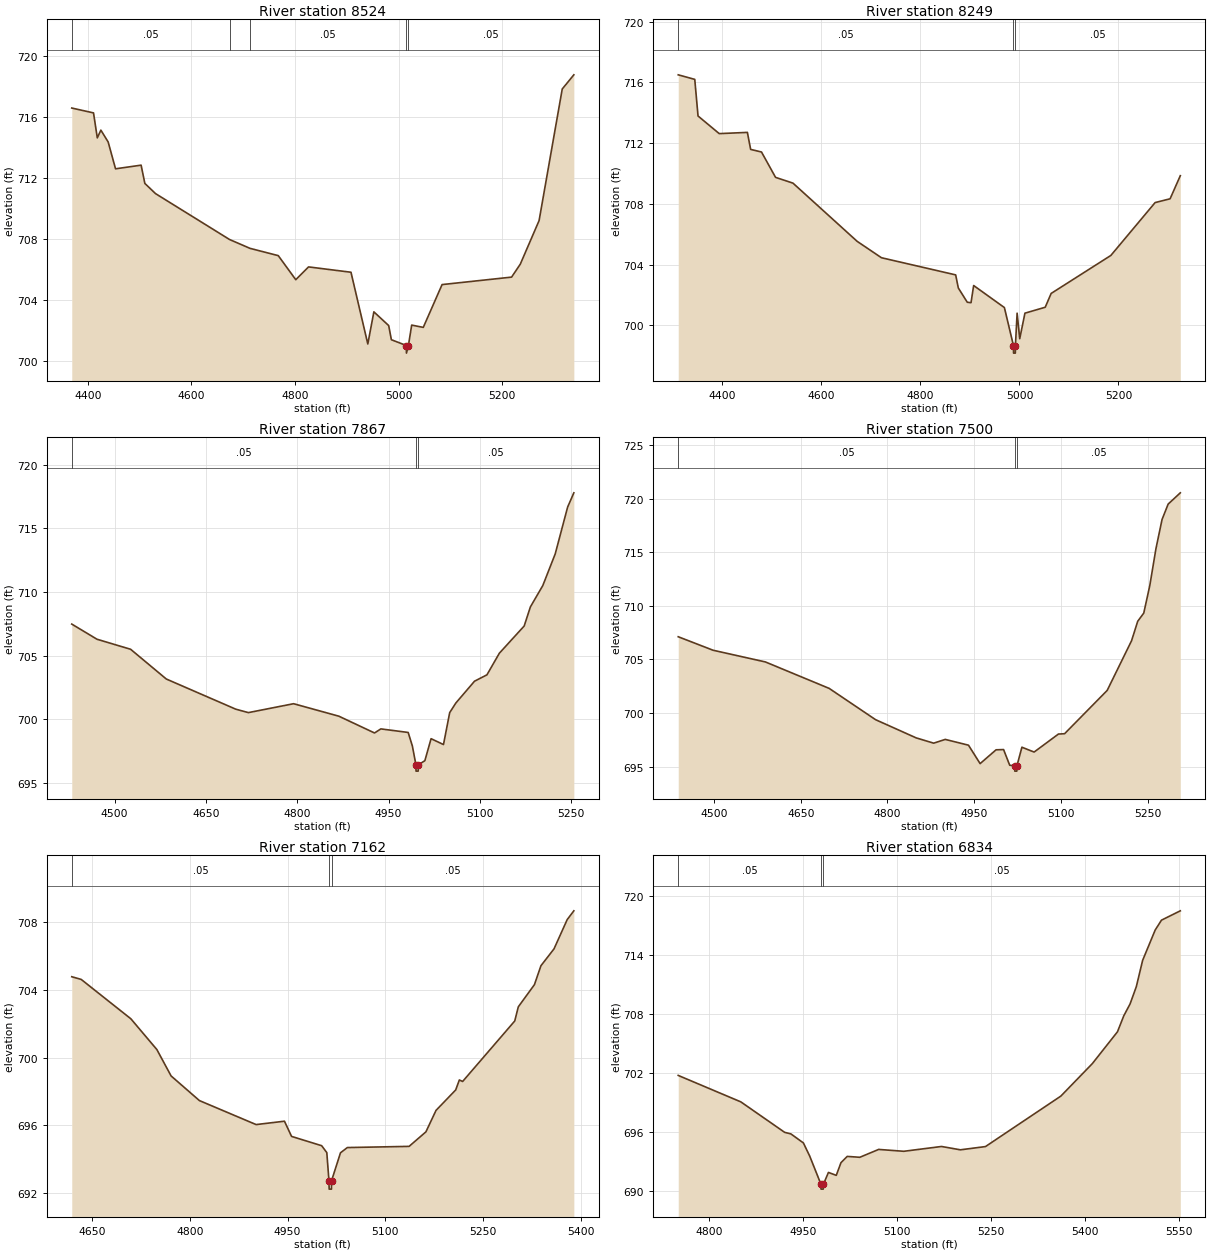
Type RM Length L Ch R = 1,8524,275,275,275
BEGIN DESCRIPTION:
Unnamed Tributary to Walnut Creek 2M 18.0
END DESCRIPTION:
XS GIS Cut Line= 5
      2331243.10      7032293.55      2331355.28      7032186.23
      2331426.57      7031982.12      2331679.00      7031910.00
      2331829.00      7031609.99
#Sta/Elev= 30
  4369.0  716.59  4411.0  716.27  4418.3  714.63  4425.2  715.14  4439.3  714.36
  4453.5  712.60  4502.9  712.84  4510.1  711.64  4530.8  710.97  4673.6  707.96
  4713.0  707.38  4767.7  706.90  4801.5  705.32  4826.2  706.16  4908.1  705.81
  4940.6  701.10  4952.3  703.21  4980.9  702.31  4986.1  701.38  5015.0  701.00
  5015.2  700.50  5019.0  701.00  5025.3  702.34  5047.7  702.19  5084.0  705.00
  5218.2  705.49  5235.0  706.34  5271.3  709.20  5316.0  717.84  5338.4  718.77
#Mann=5,-1,0
  4369.0    0.05       0  4673.6   0.075       0  4713.0    0.05       0
  5015.0    0.04       0  5019.0    0.05       0
Bank Sta=5015,5019
Exp/Cntr=0.3,0.1

Type RM Length L Ch R = 1,8249,382,382,382
BEGIN DESCRIPTION:
Unnamed Tributary to Walnut Creek 2M 17.0
END DESCRIPTION:
XS GIS Cut Line= 4
      2331250.08      7032337.94      2331416.90      7032147.37
      2331911.58      7031974.46      2331943.25      7031739.59
#Sta/Elev= 30
  4310.6  716.49  4344.0  716.19  4350.6  713.78  4393.4  712.62  4450.3  712.70
  4456.9  711.58  4478.8  711.41  4507.2  709.74  4542.4  709.36  4672.0  705.53
  4721.1  704.45  4871.1  703.32  4876.4  702.46  4894.5  701.52  4902.1  701.49
  4907.4  702.62  4969.5  701.17  4987.8  698.67  4988.1  698.17  4991.6  698.17
  4991.8  698.67  4995.2  700.80  5000.5  699.12  5011.0  700.80  5052.0  701.19
  5064.0  702.10  5184.6  704.60  5274.0  708.08  5304.3  708.33  5324.9  709.85
#Mann=3,-1,0
  4310.6    0.05       0  4987.8    0.04       0  4991.8    0.05       0
Bank Sta=4987.8,4991.8
Exp/Cntr=0.3,0.1

Type RM Length L Ch R = 1,7867,367,367,367
BEGIN DESCRIPTION:
Unnamed Tributary to Walnut Creek 2M 16.0
END DESCRIPTION:
XS GIS Cut Line= 3
      2331529.04      7032259.99      2332079.00      7032110.00
      2332329.00      7032060.00
#Sta/Elev= 30
  4429.5  707.48  4470.9  706.29  4526.2  705.50  4584.9  703.16  4699.0  700.79
  4719.7  700.52  4794.0  701.22  4868.3  700.24  4927.0  698.92  4937.4  699.24
  4982.3  698.96  4989.2  697.89  4995.0  696.42  4995.2  695.92  4998.7  695.92
  4999.0  696.42  5009.7  696.74  5019.9  698.47  5040.3  698.01  5050.5  700.52
  5060.7  701.28  5091.3  702.99  5111.7  703.49  5132.1  705.19  5172.9  707.33
  5183.1  708.83  5203.5  710.51  5223.9  713.00  5244.3  716.68  5254.5  717.80
#Mann=3,-1,0
  4429.5    0.05       0  4995.0   0.033       0  4999.0    0.05       0
Bank Sta=4995,4999
Exp/Cntr=0.3,0.1

Type RM Length L Ch R = 1,7500,338,338,338
BEGIN DESCRIPTION:
Unnamed Tributary to Walnut Creek 2M 15.0
END DESCRIPTION:
XS GIS Cut Line= 3
      2331578.96      7032410.00      2332129.00      7032460.00
      2332428.97      7032360.01
#Sta/Elev= 30
  4438.1  707.11  4498.4  705.85  4588.8  704.76  4699.2  702.29  4779.5  699.37
  4849.8  697.67  4880.0  697.18  4900.0  697.53  4940.2  696.99  4960.3  695.27
  4987.9  696.56  5000.9  696.58  5011.5  695.12  5020.0  695.07  5020.3  694.57
  5023.8  694.57  5024.0  695.07  5032.6  696.80  5053.7  696.35  5095.8  698.03
  5106.4  698.06  5180.1  702.10  5222.3  706.74  5232.9  708.55  5243.4  709.32
  5253.9  711.91  5264.5  715.34  5275.0  718.05  5285.6  719.49  5306.6  720.54
#Mann=3,-1,0
  4438.1    0.05       0  5020.0   0.033       0  5024.0    0.05       0
Bank Sta=5020,5024
Exp/Cntr=0.3,0.1

Type RM Length L Ch R = 1,7162,328,328,328
BEGIN DESCRIPTION:
Unnamed Tributary to Walnut Creek 2M 14.0
END DESCRIPTION:
XS GIS Cut Line= 4
      2331728.96      7032509.98      2332079.00      7032660.00
      2332233.53      7032710.72      2332459.17      7032685.65
#Sta/Elev= 30
  4618.9  704.79  4633.4  704.63  4709.6  702.30  4749.5  700.48  4771.3  698.92
  4814.8  697.46  4901.8  696.04  4945.3  696.24  4956.2  695.34  5002.4  694.79
  5010.3  694.38  5013.6  692.72  5013.9  692.22  5017.4  692.22  5017.6  692.72
  5031.3  694.37  5041.8  694.68  5136.6  694.75  5162.4  695.61  5177.9  696.88
  5208.1  698.09  5213.7  698.68  5218.7  698.59  5298.7  702.17  5304.2  703.01
  5328.9  704.32  5338.9  705.44  5359.0  706.44  5379.2  708.17  5389.4  708.69
#Mann=3,-1,0
  4618.9    0.05       0  5013.6    0.04       0  5017.6    0.05       0
Bank Sta=5013.6,5017.6
Exp/Cntr=0.3,0.1

Type RM Length L Ch R = 1,6834,177,177,177
BEGIN DESCRIPTION:
Unnamed Tributary to Walnut Creek 2M 13.0
END DESCRIPTION:
XS GIS Cut Line= 3
      2331729.04      7032860.00      2331979.00      7032860.00
      2332528.97      7032810.00
#Sta/Elev= 30
  4750.1  701.77  4850.1  699.08  4920.1  695.98  4930.1  695.82  4950.1  694.90
  4960.1  693.57  4978.1  690.70  4978.3  690.20  4981.8  690.20  4982.1  690.70
  4990.1  691.90  5002.6  691.60  5010.1  692.89  5020.1  693.53  5040.2  693.44
  5070.3  694.24  5110.5  694.05  5170.8  694.54  5200.9  694.20  5241.0  694.53
  5361.5  699.67  5411.7  702.97  5451.9  706.21  5462.0  707.84  5472.0  709.04
  5482.0  710.80  5492.1  713.48  5512.2  716.57  5522.2  717.57  5552.3  718.52
#Mann=3,-1,0
  4750.1    0.05       0  4978.1   0.033       0  4982.1    0.05       0
Bank Sta=4978.1,4982.1
Exp/Cntr=0.3,0.1

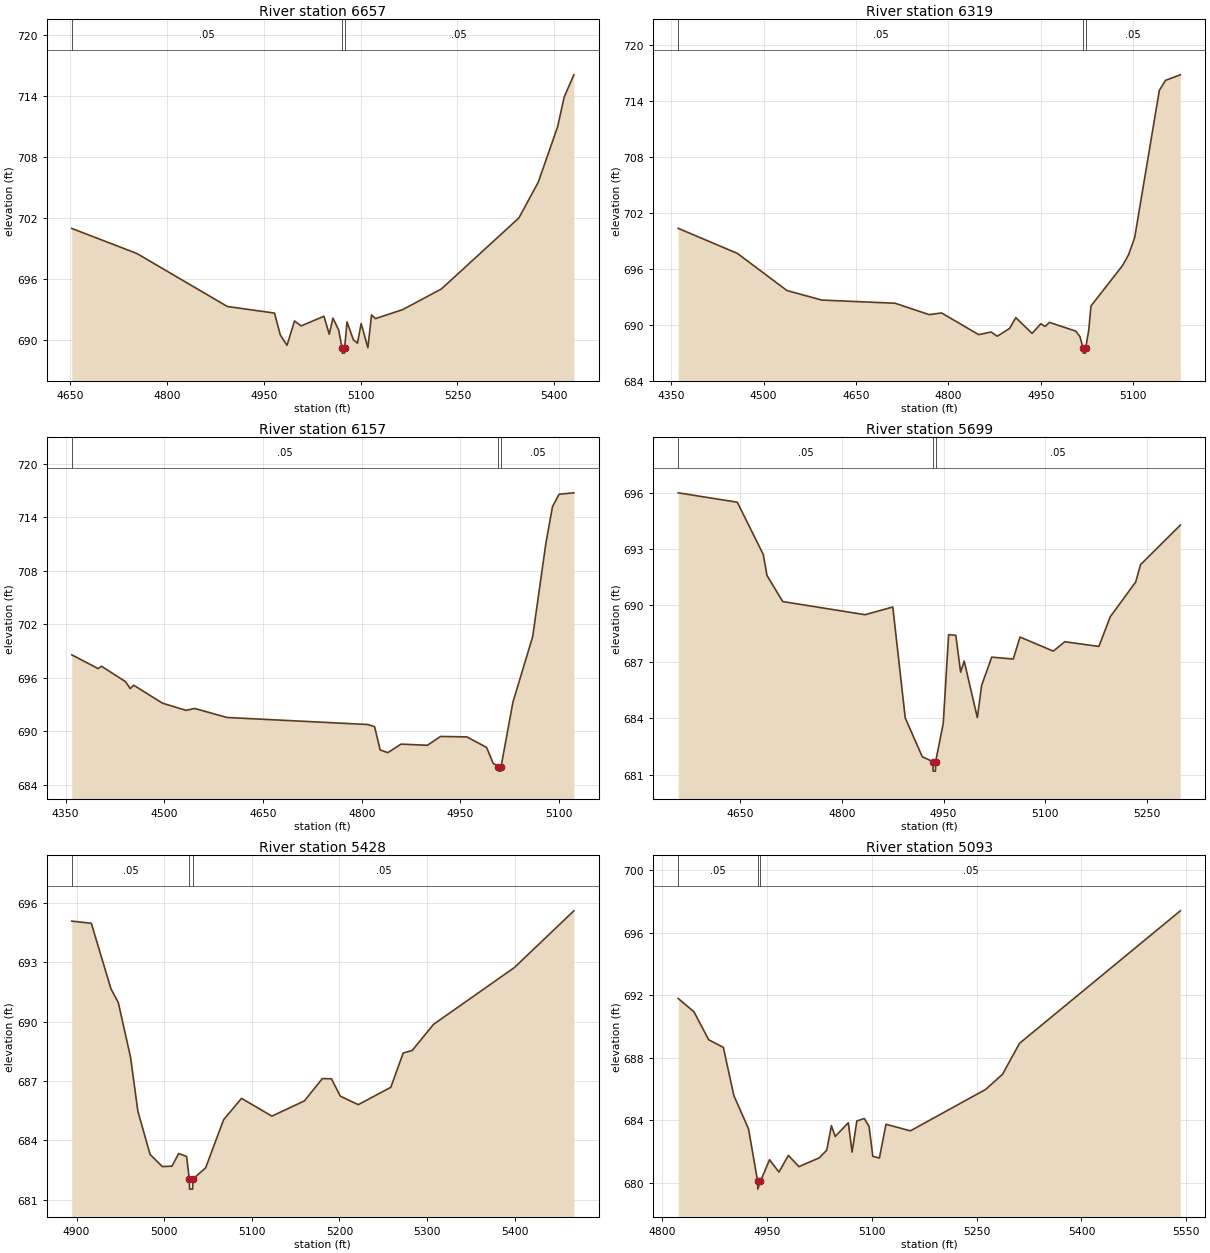
Type RM Length L Ch R = 1,6657,338,338,338
BEGIN DESCRIPTION:
2M 12.7
END DESCRIPTION:
XS GIS Cut Line= 4
      2331728.14      7033022.11      2332039.57      7033018.15
      2332193.94      7032933.71      2332484.13      7032933.71
#Sta/Elev= 30
  4652.6  700.98  4753.5  698.52  4893.5  693.32  4966.6  692.67  4975.6  690.52
  4986.0  689.51  4997.6  691.90  5007.8  691.41  5043.2  692.36  5051.4  690.59
  5057.1  692.18  5066.0  691.01  5071.2  689.24  5071.5  688.74  5075.0  688.74
  5075.2  689.24  5078.9  691.81  5088.8  690.05  5095.1  689.72  5100.8  691.64
  5111.2  689.27  5116.9  692.49  5123.0  692.13  5165.1  693.01  5225.1  695.04
  5345.1  702.01  5375.1  705.52  5405.1  710.97  5415.1  713.85  5430.2  716.06
#Mann=3,-1,0
  4652.6    0.05       0  5071.2   0.033       0  5075.2    0.05       0
Bank Sta=5071.2,5075.2
Exp/Cntr=0.3,0.1

Type RM Length L Ch R = 1,6319,162,162,162
BEGIN DESCRIPTION:
2M 12.6
END DESCRIPTION:
XS GIS Cut Line= 4
      2331753.25      7033055.10      2332310.06      7033102.60
      2332389.22      7033023.43      2332533.03      7033022.11
#Sta/Elev= 30
  4361.6  700.33  4457.7  697.64  4538.0  693.67  4594.5  692.65  4713.5  692.31
  4768.8  691.09  4788.9  691.27  4849.1  688.95  4869.2  689.23  4879.2  688.78
  4899.3  689.62  4909.3  690.77  4935.7  689.08  4949.8  690.11  4956.9  689.83
  4963.9  690.26  5006.4  689.33  5013.4  688.74  5018.5  687.47  5018.8  686.97
  5022.3  686.97  5022.5  687.47  5027.6  689.41  5031.3  692.02  5082.2  696.32
  5092.2  697.49  5102.2  699.35  5142.2  715.10  5152.2  716.17  5176.2  716.76
#Mann=3,-1,0
  4361.6    0.05       0  5018.5   0.033       0  5022.5    0.05       0
Bank Sta=5018.5,5022.5
Exp/Cntr=0.3,0.1

Type RM Length L Ch R = 1,6157,458,458,458
BEGIN DESCRIPTION:
2M 12.5
END DESCRIPTION:
XS GIS Cut Line= 3
      2331799.41      7033085.44      2332257.28      7033185.72
      2332551.55      7033183.08
#Sta/Elev= 30
  4359.3  698.58  4399.3  697.04  4404.5  697.30  4440.8  695.58  4448.3  694.79
  4453.4  695.17  4497.3  693.15  4532.9  692.35  4546.2  692.56  4595.2  691.55
  4809.3  690.76  4819.5  690.52  4828.0  687.90  4839.7  687.61  4859.7  688.56
  4899.7  688.43  4919.7  689.42  4959.7  689.37  4989.7  688.19  4999.7  686.41
  5007.7  686.03  5008.0  685.53  5011.5  685.53  5011.7  686.03  5029.7  693.26
  5059.8  700.64  5079.8  711.10  5089.8  715.19  5099.8  716.60  5122.3  716.76
#Mann=3,-1,0
  4359.3    0.05       0  5007.7   0.033       0  5011.7    0.05       0
Bank Sta=5007.7,5011.7
Exp/Cntr=0.3,0.1

Type RM Length L Ch R = 1,5699,271,271,271
BEGIN DESCRIPTION:
Unnamed Tributary to Walnut Creek 2M 12.0
END DESCRIPTION:
XS GIS Cut Line= 4
      2331869.38      7033173.86      2332176.79      7033311.07
      2332236.17      7033479.96      2332438.06      7033580.25
#Sta/Elev= 30
  4558.3  696.00  4645.5  695.50  4683.8  692.72  4689.3  691.60  4712.5  690.21
  4834.1  689.51  4875.0  689.92  4893.4  684.01  4918.5  681.95  4934.2  681.68
  4934.5  681.18  4938.0  681.18  4938.2  681.68  4949.5  683.73  4957.4  688.45
  4968.0  688.41  4975.1  686.45  4980.4  687.04  4999.8  684.03  5006.1  685.74
  5021.0  687.25  5052.8  687.15  5062.8  688.32  5112.0  687.57  5128.8  688.07
  5179.2  687.82  5196.0  689.40  5233.5  691.25  5240.8  692.18  5299.4  694.28
#Mann=3,-1,0
  4558.3    0.05       0  4934.2   0.033       0  4938.2    0.05       0
Bank Sta=4934.2,4938.2
Exp/Cntr=0.3,0.1

Type RM Length L Ch R = 1,5428,335,335,335
BEGIN DESCRIPTION:
Unnamed Tributary to Walnut Creek 2M 11.0
END DESCRIPTION:
XS GIS Cut Line= 3
      2331929.02      7033510.01      2332029.00      7033560.00
      2332479.04      7033660.01
#Sta/Elev= 30
  4894.6  695.09  4916.9  694.98  4939.3  691.67  4947.7  690.97  4961.7  688.20
  4970.0  685.48  4984.0  683.29  4998.0  682.68  5008.9  682.70  5016.6  683.34
  5025.6  683.19  5028.7  682.04  5029.0  681.54  5032.5  681.54  5032.7  682.04
  5047.4  682.62  5067.8  685.05  5088.3  686.13  5122.9  685.23  5160.0  686.00
  5180.5  687.13  5190.8  687.12  5201.0  686.24  5221.5  685.81  5258.6  686.69
  5272.7  688.42  5283.0  688.55  5307.3  689.87  5399.5  692.74  5467.4  695.61
#Mann=3,-1,0
  4894.6    0.05       0  5028.7   0.033       0  5032.7    0.05       0
Bank Sta=5028.7,5032.7
Exp/Cntr=0.3,0.1

Type RM Length L Ch R = 1,5093,336,336,336
BEGIN DESCRIPTION:
Unnamed Tributary to Walnut Creek 2M 10.0
END DESCRIPTION:
XS GIS Cut Line= 3
      2331779.01      7033710.00      2331929.00      7033810.00
      2332429.01      7034010.00
#Sta/Elev= 30
  4822.7  691.78  4845.2  690.93  4866.3  689.14  4887.3  688.65  4902.3  685.57
  4923.3  683.44  4936.4  680.08  4936.6  679.58  4940.4  680.08  4953.4  681.46
  4966.9  680.67  4980.4  681.74  4995.5  681.02  5024.5  681.58  5035.3  682.07
  5042.0  683.64  5047.4  682.95  5066.2  683.83  5071.6  681.95  5078.4  683.94
  5089.1  684.10  5095.9  683.59  5101.3  681.68  5110.7  681.57  5120.1  683.73
  5155.1  683.31  5262.8  685.96  5287.0  686.93  5311.3  688.91  5541.5  697.39
#Mann=3,-1,0
  4822.7    0.05       0  4936.4   0.033       0  4940.4    0.05       0
Bank Sta=4936.4,4940.4
Exp/Cntr=0.3,0.1

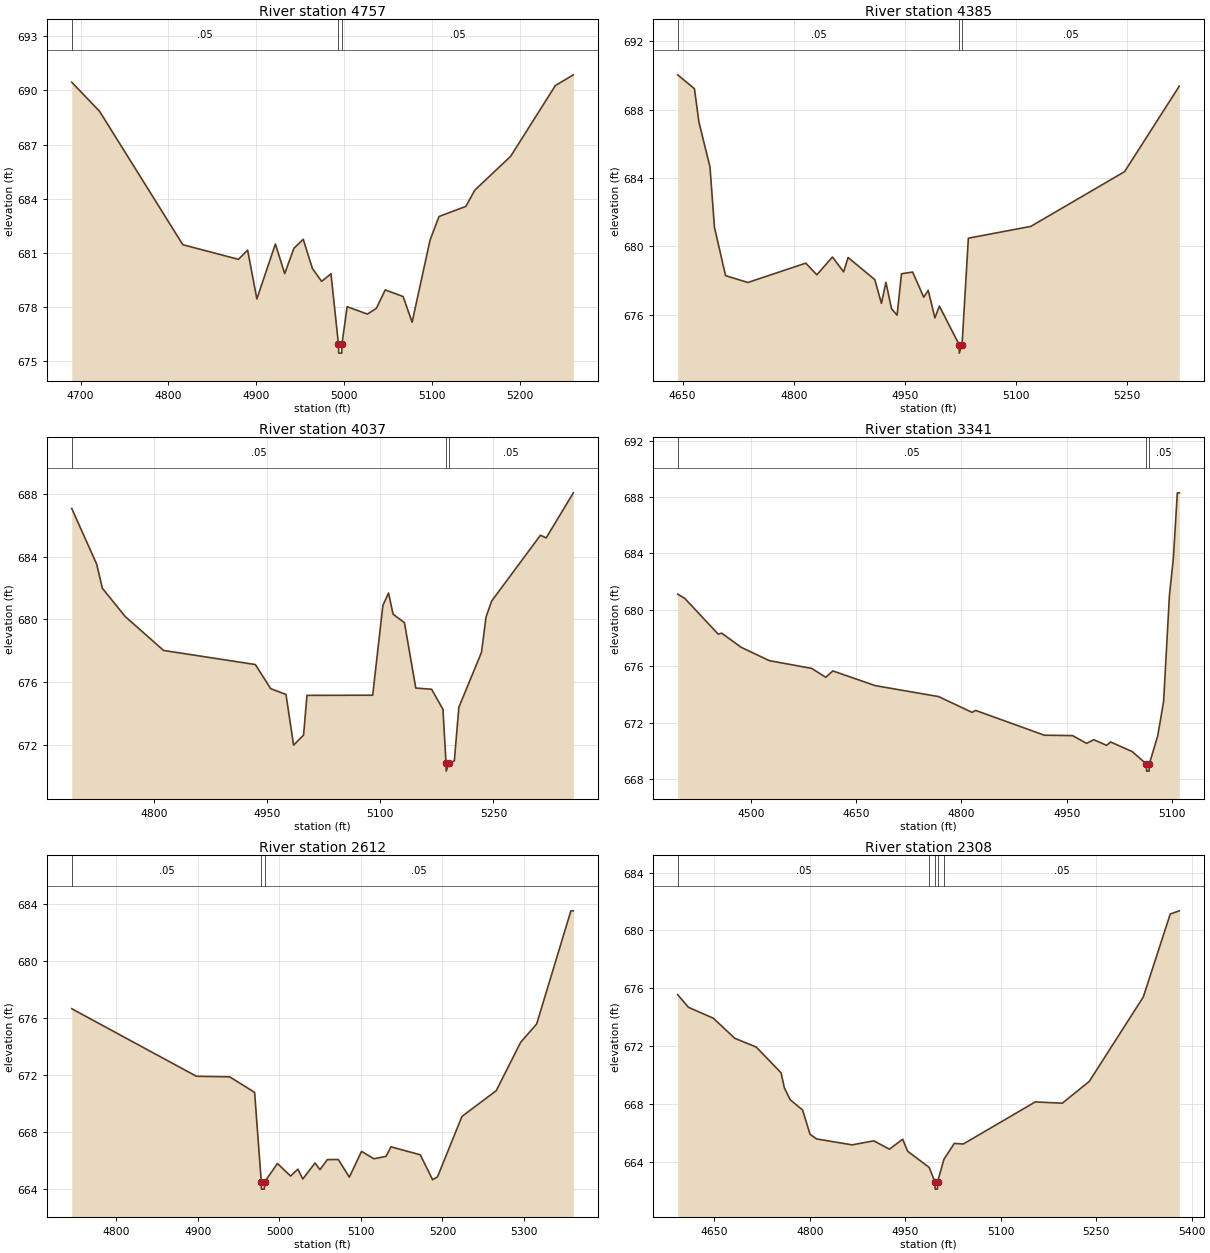
Type RM Length L Ch R = 1,4757,372,372,372
BEGIN DESCRIPTION:
Unnamed Tributary to Walnut Creek 2M 9.0
END DESCRIPTION:
XS GIS Cut Line= 3
      2331678.97      7033959.99      2331979.00      7034060.00
      2332228.99      7034010.00
#Sta/Elev= 30
  4689.9  690.45  4721.6  688.84  4816.4  681.46  4879.7  680.65  4890.2  681.16
  4900.7  678.46  4921.8  681.50  4932.4  679.86  4942.9  681.26  4953.5  681.76
  4964.0  680.14  4974.5  679.43  4985.1  679.85  4993.6  675.96  4993.9  675.46
  4997.4  675.46  4997.6  675.96  5003.5  678.03  5026.6  677.62  5036.8  677.94
  5046.9  678.96  5067.3  678.59  5077.5  677.17  5097.9  681.71  5108.1  683.02
  5138.7  683.58  5148.9  684.48  5189.7  686.35  5240.7  690.27  5261.1  690.86
#Mann=3,-1,0
  4689.9    0.05       0  4993.6   0.033       0  4997.6    0.05       0
Bank Sta=4993.6,4997.6
Exp/Cntr=0.3,0.1

Type RM Length L Ch R = 1,4385,348,348,348
BEGIN DESCRIPTION:
Unnamed Tributary to Walnut Creek 2M 8.0
END DESCRIPTION:
XS GIS Cut Line= 3
      2331628.98      7034059.99      2331929.00      7034260.00
      2332229.00      7034160.00
#Sta/Elev= 30
  4643.3  690.03  4665.9  689.22  4671.9  687.28  4686.9  684.64  4692.9  681.12
  4707.9  678.29  4738.0  677.89  4816.1  679.02  4831.1  678.34  4852.1  679.38
  4867.2  678.51  4873.2  679.35  4909.2  678.06  4918.2  676.67  4924.3  677.90
  4931.8  676.36  4939.3  675.98  4945.3  678.40  4960.3  678.50  4975.3  677.03
  4981.3  677.43  4990.4  675.82  4996.4  676.51  5023.0  674.26  5023.2  673.76
  5027.0  674.26  5035.5  680.48  5119.8  681.17  5246.3  684.37  5320.1  689.37
#Mann=3,-1,0
  4643.3    0.05       0  5023.0    0.04       0  5027.0    0.05       0
Bank Sta=5023,5027
Exp/Cntr=0.3,0.1

Type RM Length L Ch R = 1,4037,696,696,696
BEGIN DESCRIPTION:
Unnamed Tributary to Walnut Creek 2M 7.0
END DESCRIPTION:
XS GIS Cut Line= 3
      2331678.99      7034610.00      2331979.00      7034560.00
      2332278.99      7034360.00
#Sta/Elev= 30
  4691.2  687.08  4724.2  683.53  4731.8  681.98  4762.2  680.17  4812.9  678.01
  4934.5  677.11  4954.8  675.57  4975.1  675.20  4985.2  671.96  4998.4  672.60
  5002.9  675.14  5090.0  675.15  5103.5  680.88  5111.0  681.68  5117.0  680.33
  5132.1  679.78  5147.1  675.61  5168.1  675.53  5183.1  674.25  5187.2  670.80
  5187.4  670.30  5191.2  670.80  5198.2  670.96  5204.2  674.38  5234.2  677.89
  5240.2  680.15  5247.7  681.17  5312.3  685.37  5319.9  685.20  5355.9  688.08
#Mann=3,-1,0
  4691.2    0.05       0  5187.2   0.033       0  5191.2    0.05       0
Bank Sta=5187.2,5191.2
Exp/Cntr=0.3,0.1

Type RM Length L Ch R = 1,3341,729,729,729
BEGIN DESCRIPTION:
Unnamed Tributary to Walnut Creek 2M 6.0
END DESCRIPTION:
XS GIS Cut Line= 3
      2331778.97      7035010.00      2332379.00      7034960.00
      2332478.99      7035009.99
#Sta/Elev= 30
  4396.1  681.11  4406.2  680.81  4453.8  678.27  4458.8  678.34  4486.4  677.34
  4526.6  676.39  4586.8  675.84  4606.9  675.21  4616.9  675.66  4677.1  674.62
  4767.4  673.84  4815.1  672.72  4820.1  672.86  4917.9  671.10  4958.1  671.07
  4978.1  670.52  4988.2  670.78  5006.6  670.38  5012.2  670.62  5042.9  669.94
  5063.3  669.05  5063.5  668.55  5067.0  668.55  5067.3  669.05  5079.3  671.05
  5087.7  673.50  5096.0  681.04  5101.6  683.67  5107.2  688.30  5110.0  688.30
#Mann=3,-1,0
  4396.1    0.05       0  5063.3   0.033       0  5067.3    0.05       0
Bank Sta=5063.3,5067.3
Exp/Cntr=0.3,0.1

Type RM Length L Ch R = 1,2612,304,304,304
BEGIN DESCRIPTION:
Unnamed Tributary to Walnut Creek 2M 5.0
END DESCRIPTION:
XS GIS Cut Line= 3
      2331878.97      7035359.99      2332129.00      7035410.00
      2332428.97      7035210.02
#Sta/Elev= 30
  4745.1  676.68  4898.1  671.94  4938.9  671.90  4969.5  670.81  4977.7  664.52
  4977.9  664.02  4981.4  664.02  4981.7  664.52  4997.5  665.82  5013.6  664.94
  5022.6  665.42  5028.6  664.73  5043.6  665.85  5049.7  665.39  5058.7  666.09
  5072.2  666.10  5085.7  664.86  5100.7  666.67  5115.8  666.15  5130.8  666.32
  5136.8  666.99  5172.8  666.43  5187.9  664.68  5193.9  664.88  5223.9  669.12
  5266.0  670.93  5296.0  674.33  5315.6  675.61  5357.6  683.55  5360.6  683.55
#Mann=3,-1,0
  4745.1    0.05       0  4977.7   0.033       0  4981.7    0.05       0
Bank Sta=4977.7,4981.7
Exp/Cntr=0.3,0.1

Type RM Length L Ch R = 1,2308,509,509,509
BEGIN DESCRIPTION:
Unnamed Tributary to Walnut Creek 2M 4.0
END DESCRIPTION:
XS GIS Cut Line= 3
      2331878.99      7035560.00      2332229.00      7035660.00
      2332529.02      7035359.98
#Sta/Elev= 30
  4592.3  675.56  4609.2  674.69  4648.2  673.94  4682.0  672.55  4715.8  671.94
  4754.8  670.16  4760.0  669.12  4769.1  668.30  4788.6  667.59  4800.3  665.91
  4810.7  665.59  4866.6  665.18  4900.4  665.46  4925.1  664.88  4945.9  665.57
  4953.7  664.74  4987.5  663.62  4996.7  662.62  4997.0  662.12  5000.5  662.12
  5000.7  662.62  5010.7  664.18  5027.0  665.28  5041.2  665.24  5154.3  668.15
  5196.7  668.06  5239.2  669.57  5324.0  675.40  5366.4  681.14  5380.6  681.36
#Mann=5,-1,0
  4592.3    0.05       0  4987.5    0.12       0  4996.7    0.07       0
  5000.7    0.12       0  5010.7    0.05       0
Bank Sta=4996.7,5000.7
Exp/Cntr=0.3,0.1