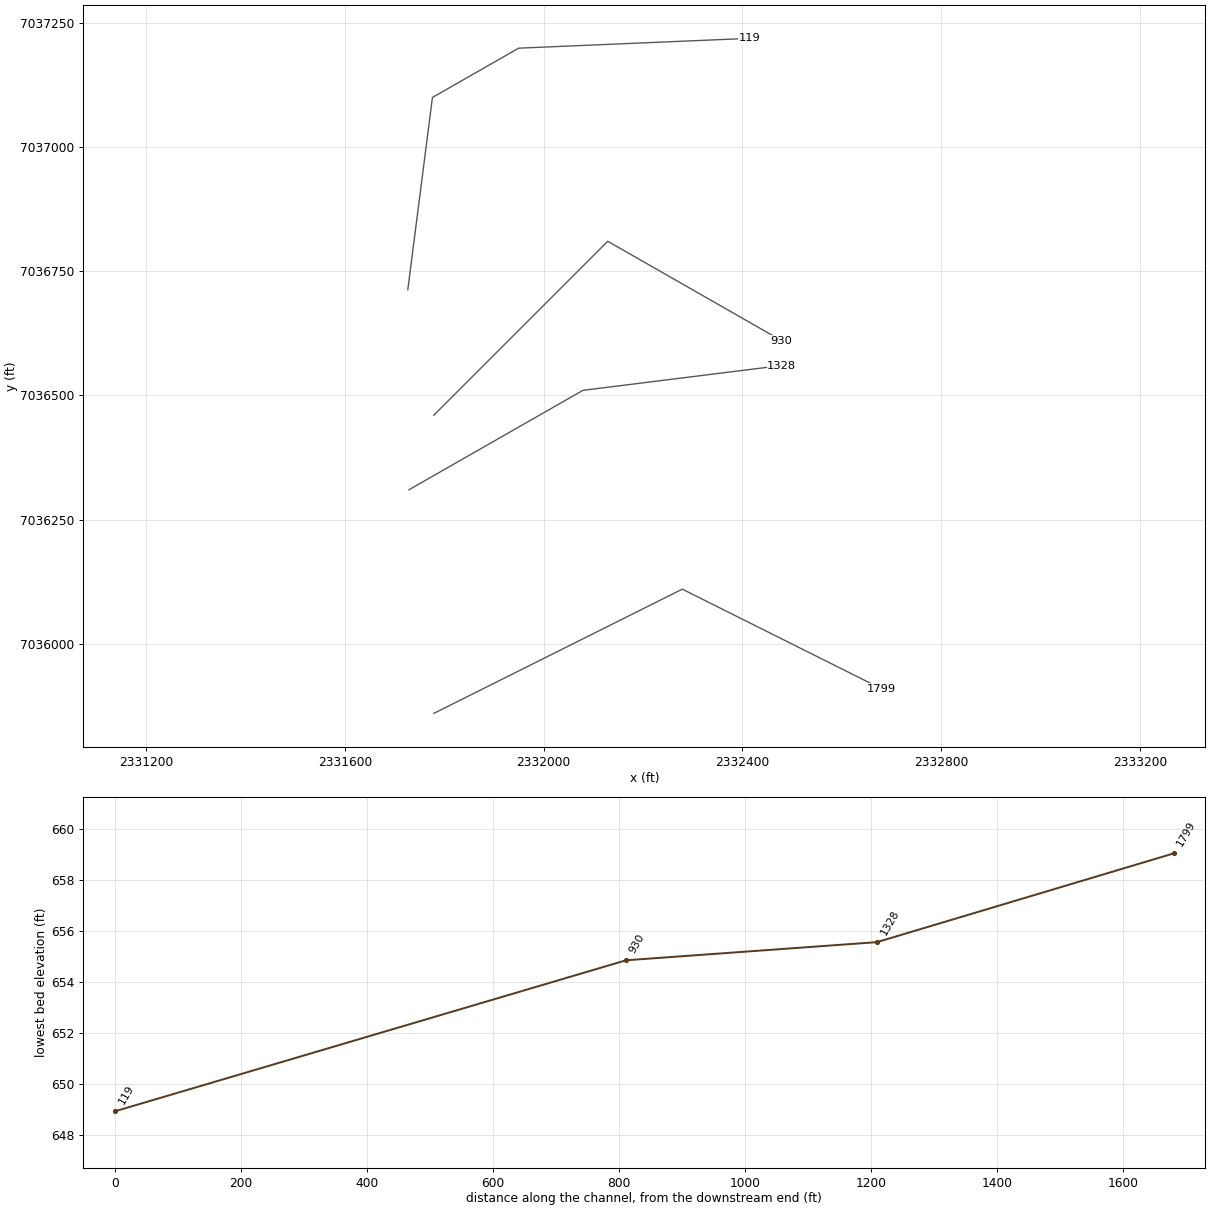
HEC-RAS study Unnamed Tr to Walnut Cr 2M.prj: Unnamed Tr to Walnut Cr 2M Base Level Engineering

--- Unnamed Tr to Walnut Cr 2M.g01 (geometry) --- (continued)

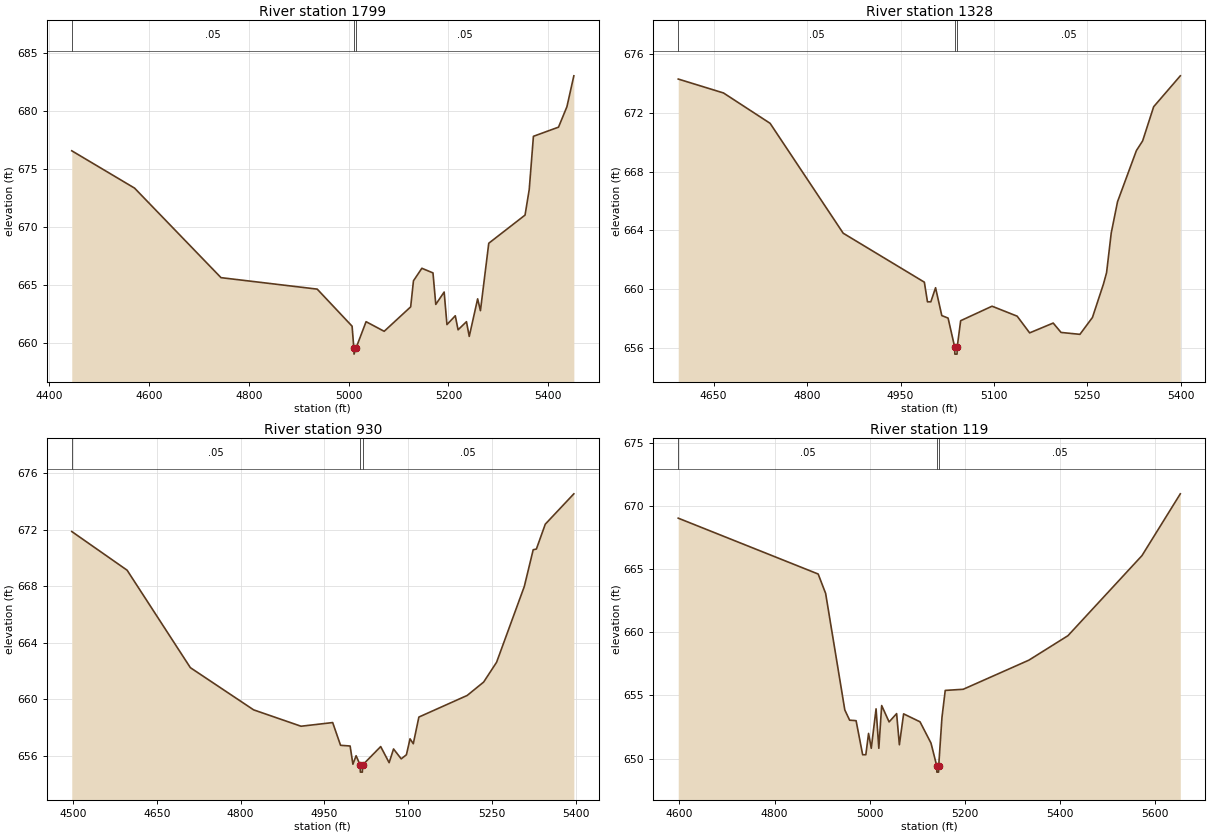
Type RM Length L Ch R = 1,1799,471,471,471
BEGIN DESCRIPTION:
Unnamed Tributary to Walnut Creek 2M 3.0
END DESCRIPTION:
XS GIS Cut Line= 3
      2331779.00      7035860.00      2332279.00      7036110.00
      2332678.97      7035910.01
#Sta/Elev= 30
  4445.1  676.58  4570.9  673.36  4744.2  665.63  4937.0  664.64  5006.9  661.44
  5010.4  659.53  5010.8  659.03  5014.6  659.53  5034.9  661.83  5071.2  661.00
  5124.3  663.11  5129.9  665.36  5146.7  666.44  5169.0  666.04  5174.6  663.32
  5191.4  664.39  5197.0  661.58  5213.7  662.34  5219.3  661.13  5236.1  661.83
  5241.7  660.56  5258.5  663.80  5264.1  662.78  5280.8  668.60  5353.5  671.03
  5361.9  673.24  5370.3  677.83  5420.6  678.62  5437.4  680.38  5451.3  683.05
#Mann=3,-1,0
  4445.1    0.05       0  5010.4   0.033       0  5014.6    0.05       0
Bank Sta=5010.4,5014.6
Exp/Cntr=0.3,0.1

Type RM Length L Ch R = 1,1328,398,398,398
BEGIN DESCRIPTION:
Unnamed Tributary to Walnut Creek 2M 2.0
END DESCRIPTION:
XS GIS Cut Line= 3
      2331729.02      7036310.01      2332079.00      7036510.00
      2332479.00      7036560.00
#Sta/Elev= 30
  4593.1  674.32  4665.8  673.37  4740.6  671.30  4858.0  663.80  4988.3  660.46
  4993.3  659.12  4998.7  659.12  5006.3  660.08  5016.3  658.18  5026.4  658.01
  5036.9  656.05  5037.3  655.55  5040.8  655.55  5041.1  656.05  5046.6  657.83
  5097.0  658.82  5137.3  658.14  5157.4  657.00  5195.2  657.67  5207.8  657.03
  5238.1  656.90  5258.2  658.05  5275.8  660.32  5280.9  661.11  5288.4  663.82
  5298.5  665.95  5328.8  669.44  5338.8  670.10  5356.5  672.43  5399.3  674.54
#Mann=3,-1,0
  4593.1    0.05       0  5036.9    0.04       0  5041.1    0.05       0
Bank Sta=5036.9,5041.1
Exp/Cntr=0.3,0.1

Type RM Length L Ch R = 1,930,811,811,811
BEGIN DESCRIPTION:
Unnamed Tributary to Walnut Creek 2M 1.0
END DESCRIPTION:
XS GIS Cut Line= 3
      2331779.00      7036460.00      2332129.00      7036810.00
      2332479.01      7036609.99
#Sta/Elev= 30
  4498.0  671.88  4597.0  669.14  4710.1  662.24  4823.3  659.25  4908.1  658.09
  4964.7  658.35  4978.8  656.74  4995.9  656.69  5000.9  655.40  5006.6  656.00
  5013.9  655.34  5014.2  654.84  5017.8  654.84  5018.1  655.34  5050.6  656.65
  5065.7  655.51  5073.6  656.48  5087.3  655.78  5096.6  656.07  5103.1  657.20
  5108.9  656.85  5118.9  658.74  5205.3  660.27  5234.8  661.22  5257.9  662.62
  5307.5  667.99  5323.4  670.59  5329.1  670.64  5345.0  672.40  5396.1  674.55
#Mann=3,-1,0
  4498.0    0.05       0  5013.9    0.04       0  5018.1    0.05       0
Bank Sta=5013.9,5018.1
Exp/Cntr=0.3,0.1

Type RM Length L Ch R = 1,119,0,0,0
BEGIN DESCRIPTION:
UNT Wal 2M 0.5
END DESCRIPTION:
XS GIS Cut Line= 4
      2331726.65      7036712.61      2331776.24      7037099.42
      2331949.83      7037198.61      2332415.01      7037218.40
#Sta/Elev= 30
  4597.6  669.06  4891.8  664.63  4907.5  663.09  4947.8  653.85  4957.9  653.04
  4971.5  653.00  4985.3  650.30  4992.0  650.30  4997.7  651.99  5003.4  650.81
  5013.5  653.94  5019.3  650.81  5025.3  654.20  5040.9  652.90  5056.7  653.56
  5062.5  651.09  5071.4  653.54  5105.9  652.91  5129.0  651.22  5141.0  649.42
  5141.3  648.92  5144.9  648.92  5145.2  649.42  5152.0  653.24  5158.9  655.40
  5196.7  655.49  5334.8  657.80  5416.9  659.74  5572.5  666.09  5653.1  670.99
#Mann=3,-1,0
  4597.6    0.05       0  5141.0    0.04       0  5145.2    0.05       0
Bank Sta=5141,5145.2
Exp/Cntr=0.3,0.1

Chan Stop Cuts=-1