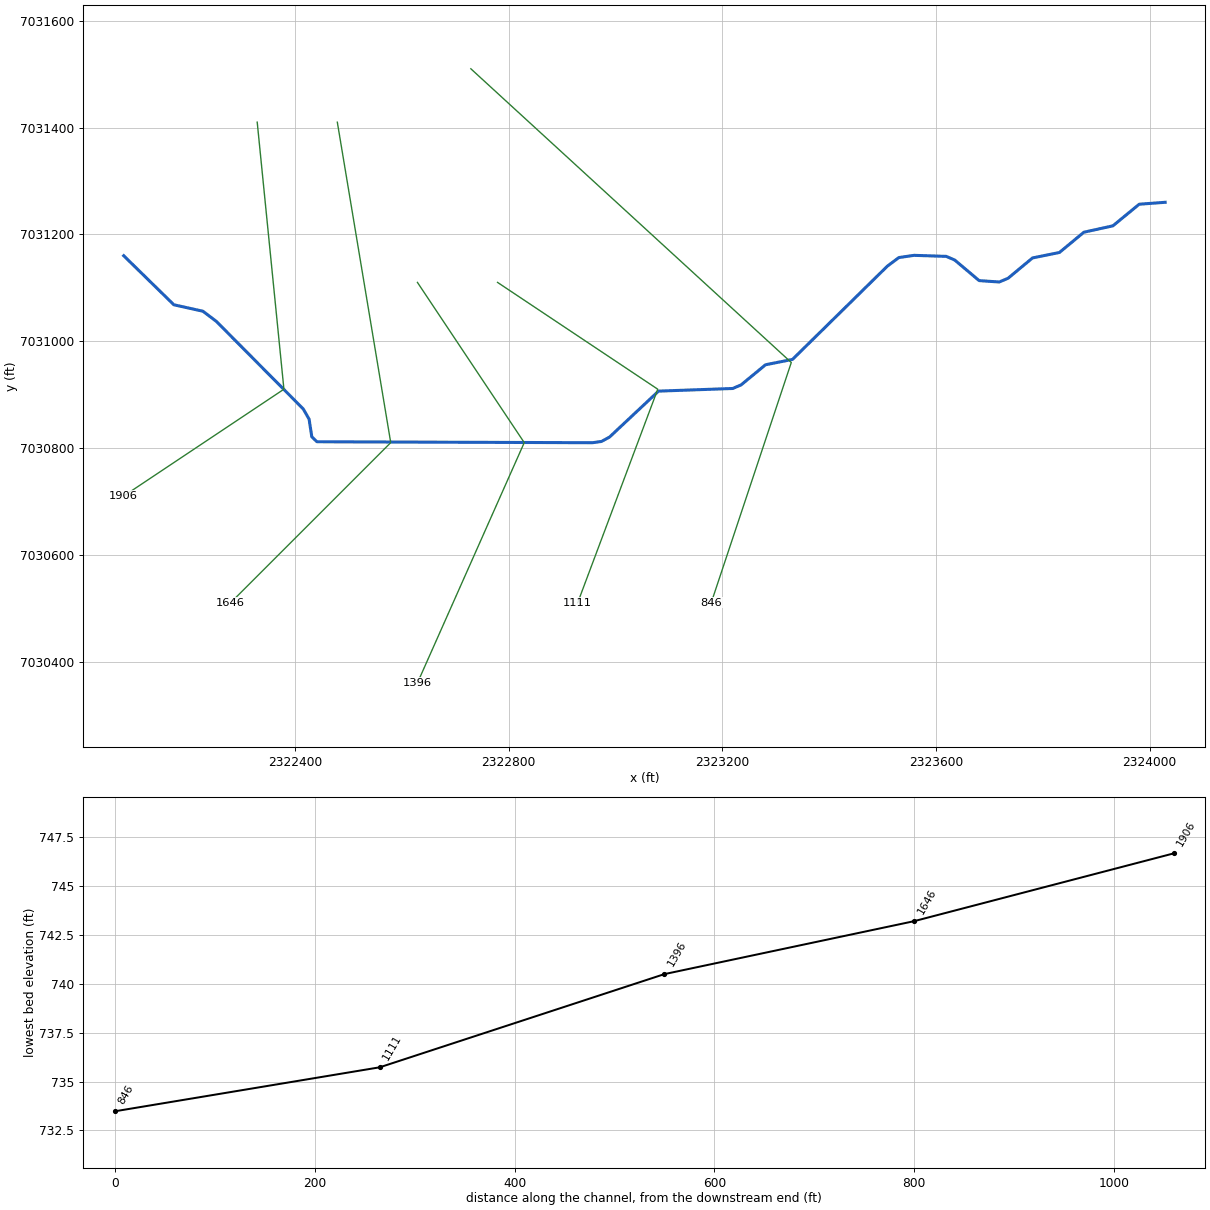
--- Unnamed Tr to Walnut Cr 2N.prj (project) ---

Proj Title=Unnamed Tr to Walnut Cr 2N Base Level Engineering
Current Plan=p01
Default Exp/Contr=0.3,0.1
English Units
Geom File=g01
Flow File=f01
Plan File=p01
BEGIN DESCRIPTION:
Unnamed Tr to Walnut Cr 2N
END DESCRIPTION:

--- Unnamed Tr to Walnut Cr 2N.p01 (plan) ---

Plan Title=Multiple Run
Short Identifier=Multiple
Geom File=g01
Flow File=f01
Subcritical Flow
K Sum by GR= 0
Std Step Tol= 0.01
Critical Tol= 0.01
Num of Std Step Trials= 20
Max Error Tol= 0.3
Flow Tol Ratio= 0.001
Split Flow NTrial= 30
Split Flow Tol= 0.02
Split Flow Ratio= 0.02
Log Output Level= 0
Friction Slope Method= 1
Unsteady Friction Slope Method= 2
Unsteady Bridges Friction Slope Method= 1
Parabolic Critical Depth
Global Vel Dist=  1 , 1 , 1
Global Log Level= 0
CheckData=True
Encroach Param= -1, 0, 0, 0
BEGIN DESCRIPTION:
Multiple Run
END DESCRIPTION:

--- Unnamed Tr to Walnut Cr 2N.f01 (steady flow) ---

Flow Title=Multiple
Number of Profiles=7
Profile Names=10-year,25-year,50-year,1pct_min,100-year,1pct_plu,500-year
River Rch & RM= Unnamed Tr to Wa,Reach-1,1906
     177     223     258     149     297     592     391
Boundary for River Rch & Prof#=Unnamed Tr to Wa,Reach-1,1
Up Type=0
Dn Type=3
Dn Slope=0.005
Boundary for River Rch & Prof#=Unnamed Tr to Wa,Reach-1,2
Up Type=0
Dn Type=3
Dn Slope=0.005
Boundary for River Rch & Prof#=Unnamed Tr to Wa,Reach-1,3
Up Type=0
Dn Type=3
Dn Slope=0.005
Boundary for River Rch & Prof#=Unnamed Tr to Wa,Reach-1,4
Up Type=0
Dn Type=3
Dn Slope=0.005
Boundary for River Rch & Prof#=Unnamed Tr to Wa,Reach-1,5
Up Type=0
Dn Type=3
Dn Slope=0.005
Boundary for River Rch & Prof#=Unnamed Tr to Wa,Reach-1,6
Up Type=0
Dn Type=3
Dn Slope=0.005
Boundary for River Rch & Prof#=Unnamed Tr to Wa,Reach-1,7
Up Type=0
Dn Type=3
Dn Slope=0.005

--- Unnamed Tr to Walnut Cr 2N.g01 (geometry) ---

Geom Title=Existing Conditions

River Reach=Unnamed Tr to Wa,Reach-1
Reach XY= 30
      2322079.00      7031160.00      2322172.93      7031068.11
      2322227.36      7031056.04      2322252.47      7031036.99
      2322415.26      7030872.95      2322426.16      7030853.88
      2322431.20      7030821.00      2322440.83      7030811.62
      2322956.35      7030809.81      2322973.55      7030812.18
      2322988.79      7030820.50      2323080.47      7030906.44
      2323219.34      7030911.37      2323235.07      7030918.10
      2323280.75      7030955.78      2323331.30      7030965.83
      2323508.85      7031140.42      2323530.50      7031156.54
      2323558.92      7031160.67      2323619.30      7031158.72
      2323635.05      7031151.86      2323680.74      7031113.37
      2323718.32      7031110.75      2323734.94      7031117.77
      2323780.72      7031155.78      2323831.20      7031166.08
      2323876.80      7031203.93      2323931.25      7031215.95
      2323980.49      7031256.40      2324029.00      7031260.00

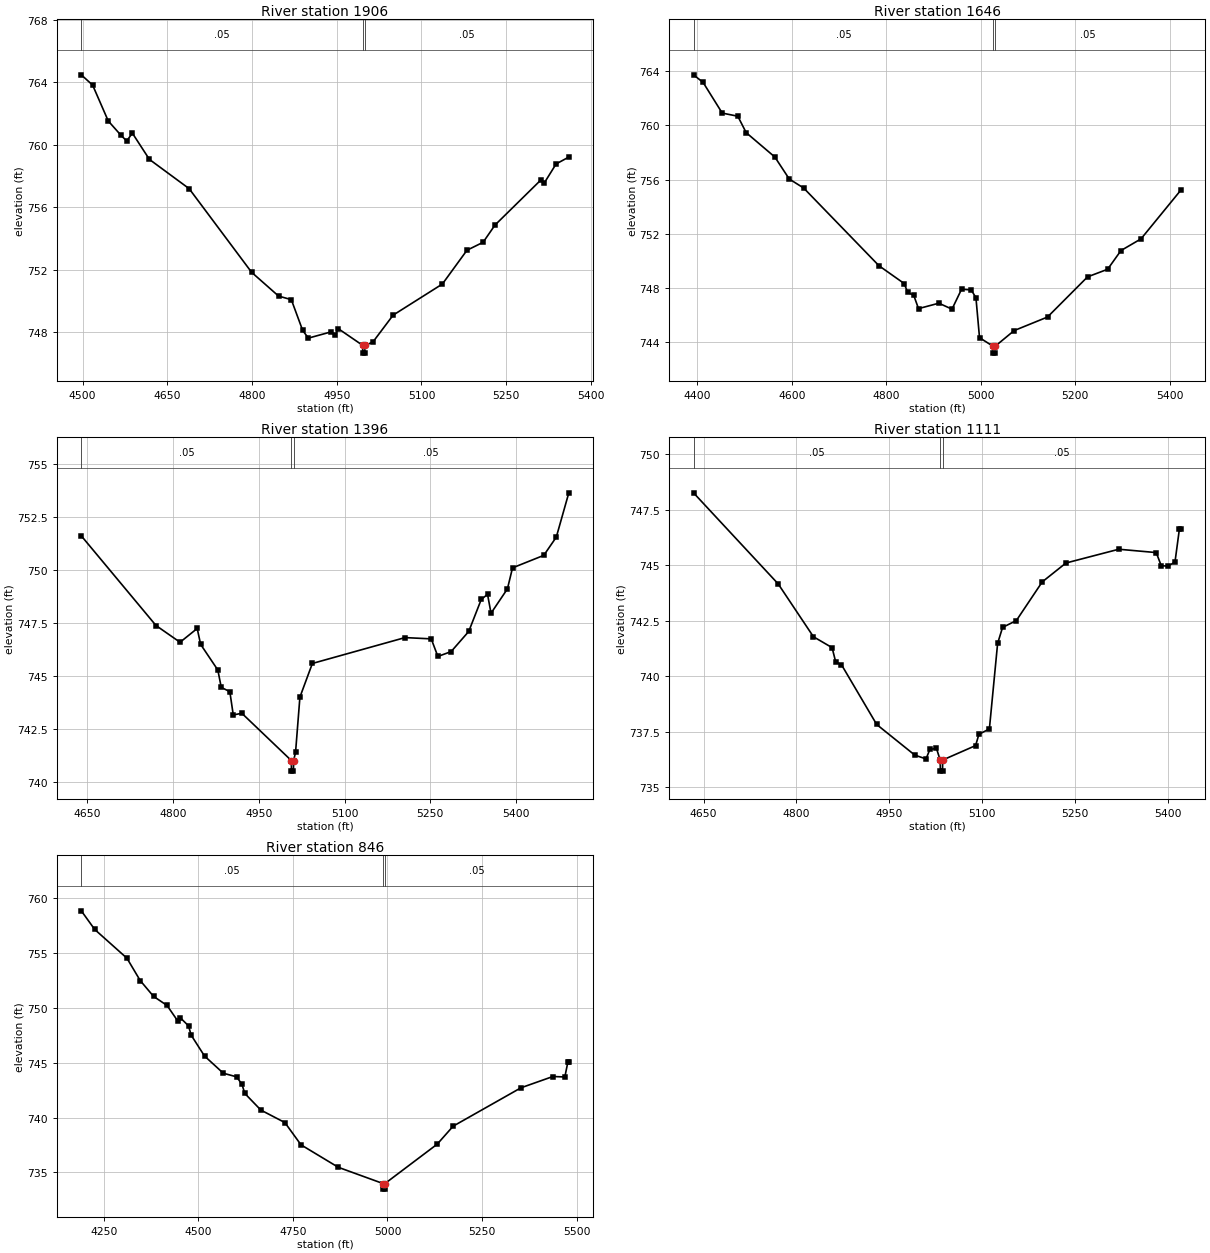
Type RM Length L Ch R = 1,1906,260,260,260
BEGIN DESCRIPTION:
Unnamed Tributary to Walnut Creek 2N 5.0
END DESCRIPTION:
XS GIS Cut Line= 3
      2322329.00      7031409.98      2322379.00      7030910.00
      2322079.02      7030710.01
#Sta/Elev= 30
  4497.8  764.48  4517.9  763.82  4545.5  761.53  4568.1  760.61  4578.2  760.25
  4588.2  760.75  4618.4  759.07  4688.7  757.20  4799.3  751.85  4847.0  750.33
  4869.6  750.10  4889.7  748.13  4899.8  747.64  4940.0  748.04  4947.5  747.81
  4952.5  748.25  4995.8  747.18  4996.0  746.68  4999.5  746.68  4999.8  747.18
  5013.8  747.38  5049.8  749.11  5137.0  751.10  5180.5  753.26  5209.1  753.77
  5230.1  754.87  5311.2  757.75  5317.3  757.56  5338.3  758.78  5360.8  759.22
#Mann=3,-1,0
  4497.8    0.05       0  4995.8    0.04       0  4999.8    0.05       0
Bank Sta=4995.8,4999.8
Exp/Cntr=0.3,0.1

Type RM Length L Ch R = 1,1646,250,250,250
BEGIN DESCRIPTION:
Unnamed Tributary to Walnut Creek 2N 4.0
END DESCRIPTION:
XS GIS Cut Line= 3
      2322479.00      7031409.99      2322579.00      7030810.00
      2322279.02      7030510.02
#Sta/Elev= 30
  4391.7  763.72  4412.0  763.16  4452.5  760.90  4485.5  760.67  4503.2  759.46
  4564.0  757.66  4594.5  756.04  4624.9  755.38  4784.5  749.65  4837.8  748.34
  4845.4  747.68  4858.0  747.48  4868.2  746.49  4911.3  746.89  4939.1  746.45
  4959.4  747.92  4979.7  747.87  4989.8  747.30  4997.4  744.35  5026.3  743.71
  5026.5  743.21  5030.0  743.21  5030.3  743.71  5070.7  744.87  5141.4  745.87
  5226.2  748.83  5268.7  749.39  5297.0  750.77  5339.4  751.63  5424.2  755.24
#Mann=3,-1,0
  4391.7    0.05       0  5026.3    0.05       0  5030.3    0.05       0
Bank Sta=5026.3,5030.3
Exp/Cntr=0.3,0.1

Type RM Length L Ch R = 1,1396,285,285,285
BEGIN DESCRIPTION:
Unnamed Tributary to Walnut Creek 2N 3.0
END DESCRIPTION:
XS GIS Cut Line= 3
      2322628.99      7031110.01      2322829.00      7030810.00
      2322629.01      7030360.01
#Sta/Elev= 30
  4639.4  751.60  4770.1  747.37  4812.2  746.58  4842.2  747.23  4848.2  746.48
  4878.3  745.27  4884.3  744.45  4899.3  744.25  4905.3  743.15  4920.3  743.23
  5006.9  741.00  5007.1  740.50  5010.6  740.50  5010.9  741.00  5014.3  741.39
  5021.9  743.99  5043.7  745.58  5205.8  746.80  5251.7  746.74  5263.3  745.91
  5286.5  746.14  5317.3  747.09  5339.2  748.60  5350.2  748.84  5356.3  747.95
  5385.0  749.10  5393.9  750.09  5448.6  750.68  5470.5  751.54  5492.4  753.63
#Mann=3,-1,0
  4639.4    0.05       0  5006.9    0.05       0  5010.9    0.05       0
Bank Sta=5006.9,5010.9
Exp/Cntr=0.3,0.1

Type RM Length L Ch R = 1,1111,265,265,265
BEGIN DESCRIPTION:
Unnamed Tributary to Walnut Creek 2N 2.0
END DESCRIPTION:
XS GIS Cut Line= 3
      2322778.97      7031110.02      2323079.00      7030910.00
      2322929.00      7030510.00
#Sta/Elev= 30
  4633.8  748.26  4770.6  744.16  4827.6  741.78  4857.7  741.29  4863.7  740.63
  4872.7  740.53  4929.8  737.83  4991.4  736.45  5009.5  736.28  5015.8  736.71
  5026.4  736.75  5032.4  736.23  5032.7  735.73  5036.2  735.73  5036.4  736.23
  5089.6  736.88  5095.0  737.39  5111.9  737.63  5125.2  741.48  5133.2  742.20
  5155.5  742.51  5197.3  744.25  5235.6  745.10  5321.0  745.72  5381.5  745.57
  5389.6  744.98  5400.2  744.96  5411.8  745.14  5418.9  746.62  5421.6  746.62
#Mann=3,-1,0
  4633.8    0.05       0  5032.4    0.04       0  5036.4    0.05       0
Bank Sta=5032.4,5036.4
Exp/Cntr=0.3,0.1

Type RM Length L Ch R = 1,846,0,0,0
BEGIN DESCRIPTION:
Unnamed Tributary to Walnut Creek 2N 1.0
END DESCRIPTION:
XS GIS Cut Line= 3
      2322728.97      7031510.03      2323329.00      7030960.00
      2323179.01      7030510.02
#Sta/Elev= 30
  4190.9  758.86  4226.4  757.16  4311.5  754.54  4346.6  752.50  4381.8  751.06
  4417.5  750.23  4445.9  748.81  4452.7  749.10  4474.3  748.37  4481.1  747.53
  4516.5  745.62  4566.2  744.05  4601.3  743.72  4615.5  743.04  4622.9  742.21
  4665.4  740.69  4728.9  739.55  4771.5  737.52  4870.1  735.47  4989.0  733.98
  4989.3  733.48  4992.8  733.48  4993.0  733.98  5131.4  737.58  5173.5  739.22
  5352.7  742.72  5437.1  743.75  5468.7  743.71  5476.6  745.05  5479.2  745.05
#Mann=3,-1,0
  4190.9    0.05       0  4989.0    0.04       0  4993.0    0.05       0
Bank Sta=4989,4993
Exp/Cntr=0.3,0.1

Chan Stop Cuts=-1