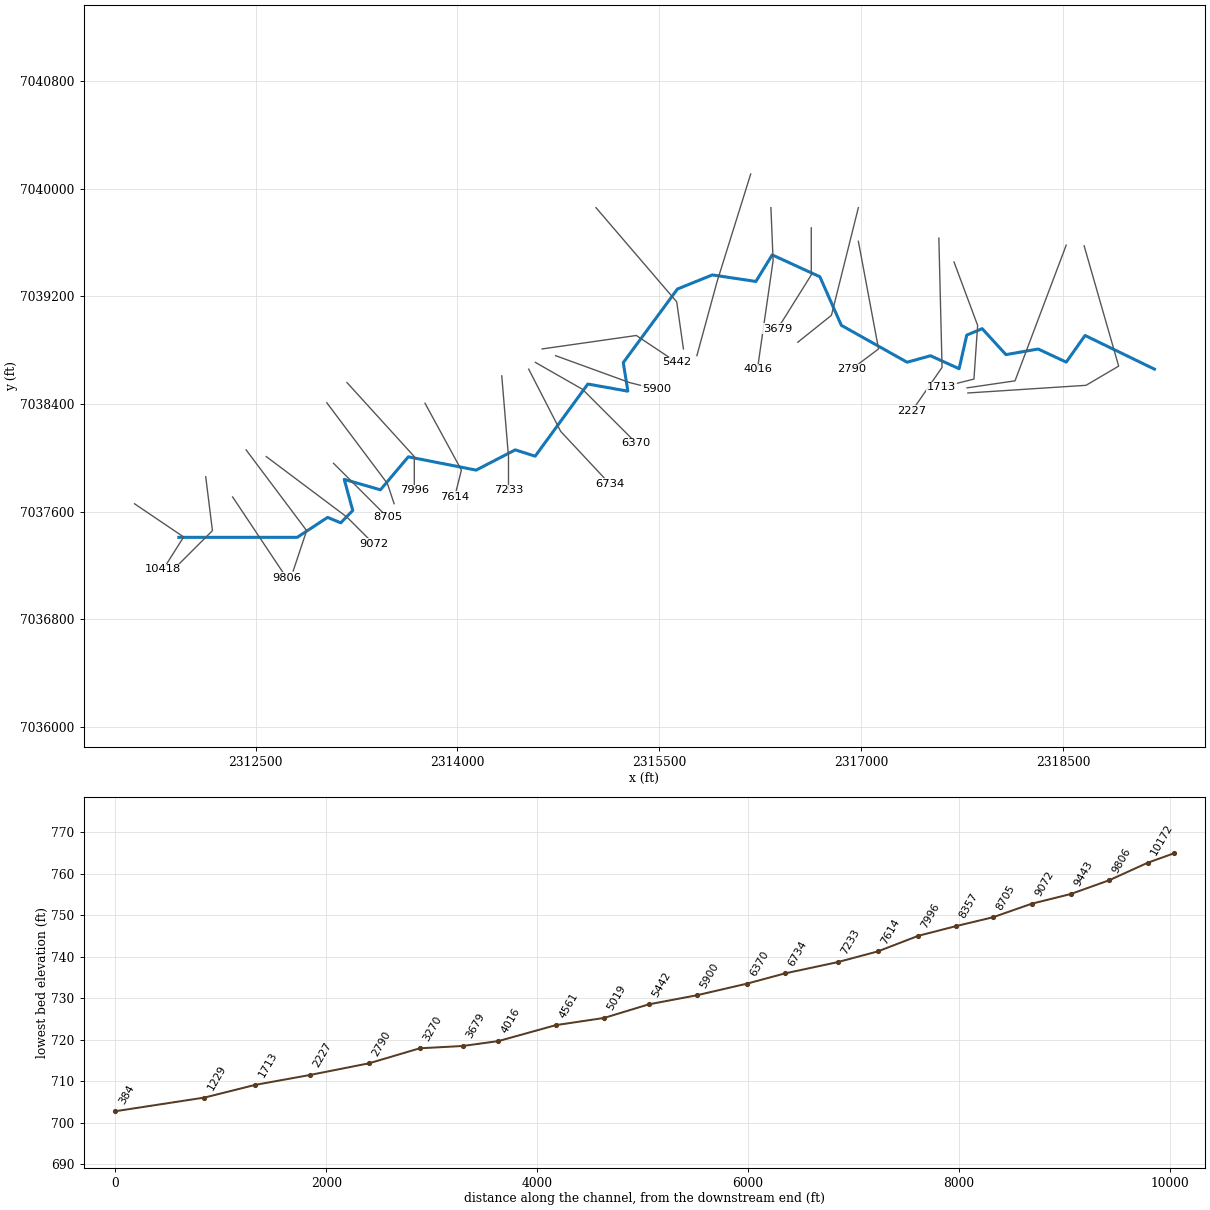
--- Unnamed Tr to Walnut Cr 2P.prj (project) ---

Proj Title=Unnamed Tr to Walnut Cr 2P Base Level Engineering
Current Plan=p01
Default Exp/Contr=0.3,0.1
English Units
Geom File=g01
Flow File=f01
Plan File=p01
BEGIN DESCRIPTION:
Unnamed Tr to Walnut Cr 2P
END DESCRIPTION:

--- Unnamed Tr to Walnut Cr 2P.p01 (plan) ---

Plan Title=Multiple Run
Short Identifier=Multiple
Geom File=g01
Flow File=f01
Subcritical Flow
K Sum by GR= 0
Std Step Tol= 0.01
Critical Tol= 0.01
Num of Std Step Trials= 20
Max Error Tol= 0.3
Flow Tol Ratio= 0.001
Split Flow NTrial= 30
Split Flow Tol= 0.02
Split Flow Ratio= 0.02
Log Output Level= 0
Friction Slope Method= 1
Unsteady Friction Slope Method= 2
Unsteady Bridges Friction Slope Method= 1
Parabolic Critical Depth
Global Vel Dist=  1 , 1 , 1
Global Log Level= 0
CheckData=True
Encroach Param= -1, 0, 0, 0
BEGIN DESCRIPTION:
Multiple Run
END DESCRIPTION:

--- Unnamed Tr to Walnut Cr 2P.f01 (steady flow) ---

Flow Title=Multiple
Number of Profiles=7
Profile Names=10-year,25-year,50-year,1pct_min,100-year,1pct_plu,500-year
River Rch & RM= Unnamed Tr to Wa,Reach-1,10418
     550     746     905     545    1090    2170    1570
River Rch & RM= Unnamed Tr to Wa,Reach-1,6734
     823    1140    1410     861    1720    3430    2550
River Rch & RM= Unnamed Tr to Wa,Reach-1,5442
     986    1380    1710    1050    2090    4180    3140
Boundary for River Rch & Prof#=Unnamed Tr to Wa,Reach-1,1
Up Type=0
Dn Type=3
Dn Slope=0.005
Boundary for River Rch & Prof#=Unnamed Tr to Wa,Reach-1,2
Up Type=0
Dn Type=3
Dn Slope=0.005
Boundary for River Rch & Prof#=Unnamed Tr to Wa,Reach-1,3
Up Type=0
Dn Type=3
Dn Slope=0.005
Boundary for River Rch & Prof#=Unnamed Tr to Wa,Reach-1,4
Up Type=0
Dn Type=3
Dn Slope=0.005
Boundary for River Rch & Prof#=Unnamed Tr to Wa,Reach-1,5
Up Type=0
Dn Type=3
Dn Slope=0.005
Boundary for River Rch & Prof#=Unnamed Tr to Wa,Reach-1,6
Up Type=0
Dn Type=3
Dn Slope=0.005
Boundary for River Rch & Prof#=Unnamed Tr to Wa,Reach-1,7
Up Type=0
Dn Type=3
Dn Slope=0.005

--- Unnamed Tr to Walnut Cr 2P.g01 (geometry) ---

Geom Title=Existing Conditions

River Reach=Unnamed Tr to Wa,Reach-1
Reach XY= 30
      2311929.00      7037410.00      2312808.97      7037410.06
      2313034.64      7037558.22      2313132.44      7037517.82
      2313221.71      7037609.89      2313158.31      7037840.74
      2313427.36      7037763.14      2313634.64      7038008.38
      2314138.28      7037909.55      2314429.00      7038060.00
      2314577.37      7038013.11      2314968.68      7038549.18
      2315265.84      7038496.27      2315232.04      7038708.58
      2315634.08      7039254.96      2315893.37      7039359.97
      2316217.47      7039311.50      2316338.63      7039508.91
      2316693.02      7039346.38      2316852.27      7038985.75
      2317341.02      7038711.19      2317515.03      7038759.46
      2317727.61      7038663.02      2317784.34      7038912.74
      2317899.13      7038960.72      2318075.57      7038767.79
      2318315.14      7038809.46      2318523.72      7038711.99
      2318663.52      7038910.00      2319179.00      7038660.00

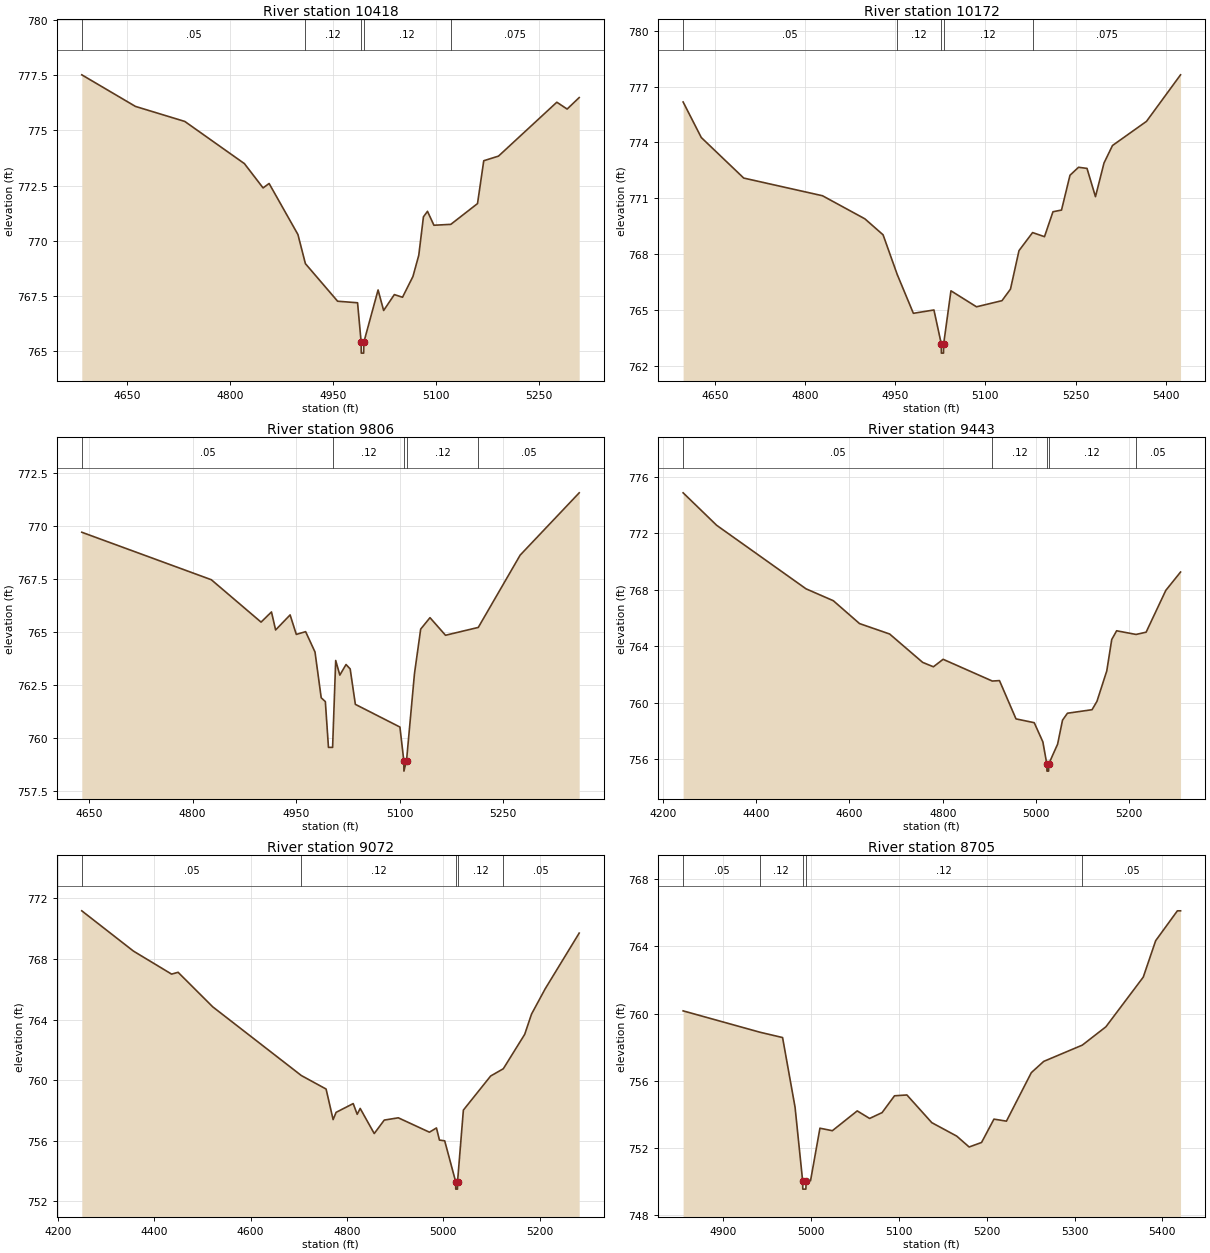
Type RM Length L Ch R = 1,10418,246,246,246
BEGIN DESCRIPTION:
UNT Walnut Ck 2P 20.0
END DESCRIPTION:
XS GIS Cut Line= 3
      2311600.06      7037659.35      2311965.12      7037412.69
      2311813.11      7037172.41
#Sta/Elev= 30
  4584.1  777.52  4662.3  776.09  4734.2  775.41  4821.1  773.50  4848.3  772.40
  4857.1  772.60  4899.1  770.29  4910.0  768.97  4956.9  767.27  4986.0  767.20
  4991.2  765.42  4991.4  764.92  4994.9  764.92  4995.2  765.42  5015.9  767.78
  5024.0  766.85  5039.6  767.57  5051.5  767.45  5066.7  768.39  5075.2  769.35
  5082.0  771.09  5087.9  771.34  5097.3  770.71  5121.9  770.75  5160.8  771.69
  5169.9  773.63  5191.4  773.84  5276.4  776.28  5291.4  775.97  5309.0  776.49
#Mann=5,-1,0
  4584.1    0.05       0  4910.0    0.12       0  4991.2    0.07       0
  4995.2    0.12       0  5121.9   0.075       0
Bank Sta=4991.2,4995.2
Exp/Cntr=0.3,0.1

Type RM Length L Ch R = 1,10172,366,366,366
BEGIN DESCRIPTION:
Unnamed Tributary to Walnut Creek 2P 19.0
END DESCRIPTION:
XS GIS Cut Line= 3
      2312129.00      7037859.99      2312179.00      7037460.00
      2311878.98      7037159.98
#Sta/Elev= 30
  4597.3  776.17  4627.5  774.26  4698.1  772.08  4829.1  771.13  4899.6  769.89
  4929.9  769.03  4953.4  766.90  4980.3  764.81  5014.5  764.99  5026.7  763.17
  5026.9  762.67  5030.4  762.67  5030.7  763.17  5042.8  766.02  5085.3  765.16
  5127.7  765.49  5141.8  766.11  5156.0  768.18  5178.6  769.15  5198.4  768.93
  5212.5  770.27  5226.7  770.36  5240.8  772.23  5255.0  772.66  5269.1  772.60
  5283.2  771.08  5297.4  772.89  5311.5  773.83  5368.1  775.13  5424.7  777.63
#Mann=5,-1,0
  4597.3    0.05       0  4953.4    0.12       0  5026.7    0.07       0
  5030.7    0.12       0  5178.6   0.075       0
Bank Sta=5026.7,5030.7
Exp/Cntr=0.3,0.1

Type RM Length L Ch R = 1,9806,363,363,363
BEGIN DESCRIPTION:
Unnamed Tributary to Walnut Creek 2P 18.0
END DESCRIPTION:
XS GIS Cut Line= 3
      2312328.98      7037710.03      2312529.00      7037410.00
      2312728.97      7037110.04
#Sta/Elev= 30
  4639.4  769.72  4827.2  767.48  4899.3  765.48  4914.4  765.96  4920.4  765.11
  4941.4  765.82  4950.4  764.90  4963.9  765.03  4977.5  764.07  4986.5  761.91
  4992.5  761.73  4997.0  759.57  5003.0  759.57  5003.9  760.39  5007.5  763.67
  5013.5  762.98  5022.5  763.48  5028.5  763.27  5036.0  761.60  5100.6  760.53
  5106.2  758.95  5106.4  758.45  5110.2  758.95  5121.7  763.05  5130.7  765.15
  5144.2  765.69  5166.7  764.86  5214.2  765.23  5274.9  768.64  5360.5  771.58
#Mann=5,-1,0
  4639.4    0.05       0  5003.9    0.12       0  5106.2   0.033       0
  5110.2    0.12       0  5214.2    0.05       0
Bank Sta=5106.2,5110.2
Exp/Cntr=0.3,0.1

Type RM Length L Ch R = 1,9443,371,371,371
BEGIN DESCRIPTION:
Unnamed Tributary to Walnut Creek 2P 17.0
END DESCRIPTION:
XS GIS Cut Line= 3
      2312429.00      7038060.00      2312879.00      7037460.00
      2312779.01      7037160.03
#Sta/Elev= 30
  4243.6  774.85  4315.5  772.55  4507.1  768.05  4565.5  767.21  4621.7  765.59
  4686.3  764.85  4757.1  762.84  4780.1  762.53  4800.9  763.06  4906.3  761.52
  4921.7  761.55  4957.1  758.84  4996.2  758.57  5014.7  757.21  5023.2  755.64
  5023.5  755.14  5027.0  755.14  5027.2  755.64  5046.3  757.05  5056.8  758.75
  5067.4  759.24  5120.1  759.49  5130.6  760.08  5151.7  762.24  5162.3  764.46
  5172.8  765.08  5214.4  764.82  5236.0  764.98  5278.2  767.94  5309.8  769.24
#Mann=5,-1,0
  4243.6    0.05       0  4906.3    0.12       0  5023.2    0.07       0
  5027.2    0.12       0  5214.4    0.05       0
Bank Sta=5023.2,5027.2
Exp/Cntr=0.3,0.1

Type RM Length L Ch R = 1,9072,367,367,367
BEGIN DESCRIPTION:
Unnamed Tributary to Walnut Creek 2P 16.0
END DESCRIPTION:
XS GIS Cut Line= 3
      2312578.99      7038010.01      2313179.00      7037560.00
      2313379.03      7037359.97
#Sta/Elev= 30
  4249.3  771.18  4356.6  768.52  4435.8  767.00  4449.3  767.12  4521.2  764.84
  4705.3  760.30  4756.6  759.41  4771.2  757.39  4777.4  757.87  4812.9  758.45
  4821.2  757.74  4827.4  758.13  4856.6  756.47  4877.4  757.36  4906.6  757.51
  4971.2  756.56  4985.8  756.84  4992.0  756.04  5002.9  755.99  5025.6  753.30
  5025.9  752.80  5029.4  752.80  5029.6  753.30  5041.7  758.02  5098.3  760.27
  5124.6  760.75  5169.0  763.02  5183.2  764.36  5211.4  766.02  5282.2  769.71
#Mann=5,-1,0
  4249.3    0.05       0  4705.3    0.12       0  5025.6    0.07       0
  5029.6    0.12       0  5124.6    0.05       0
Bank Sta=5025.6,5029.6
Exp/Cntr=0.3,0.1

Type RM Length L Ch R = 1,8705,348,348,348
BEGIN DESCRIPTION:
Unnamed Tributary to Walnut Creek 2P 15.0
END DESCRIPTION:
XS GIS Cut Line= 3
      2313079.01      7037959.99      2313179.00      7037860.00
      2313479.02      7037559.98
#Sta/Elev= 30
  4854.9  760.16  4942.1  758.89  4968.0  758.57  4982.2  754.42  4990.8  750.04
  4991.0  749.54  4994.5  749.54  4994.8  750.04  4999.8  750.04  5010.5  753.17
  5024.6  753.02  5052.9  754.20  5067.0  753.75  5081.2  754.10  5095.3  755.10
  5109.4  755.15  5137.7  753.50  5166.0  752.70  5180.2  752.05  5194.3  752.32
  5208.4  753.71  5222.6  753.59  5250.9  756.48  5265.0  757.15  5308.9  758.12
  5335.7  759.21  5378.2  762.17  5392.3  764.34  5417.0  766.12  5420.6  766.12
#Mann=5,-1,0
  4854.9    0.05       0  4942.1    0.12       0  4990.8    0.07       0
  4994.8    0.12       0  5308.9    0.05       0
Bank Sta=4990.8,4994.8
Exp/Cntr=0.3,0.1

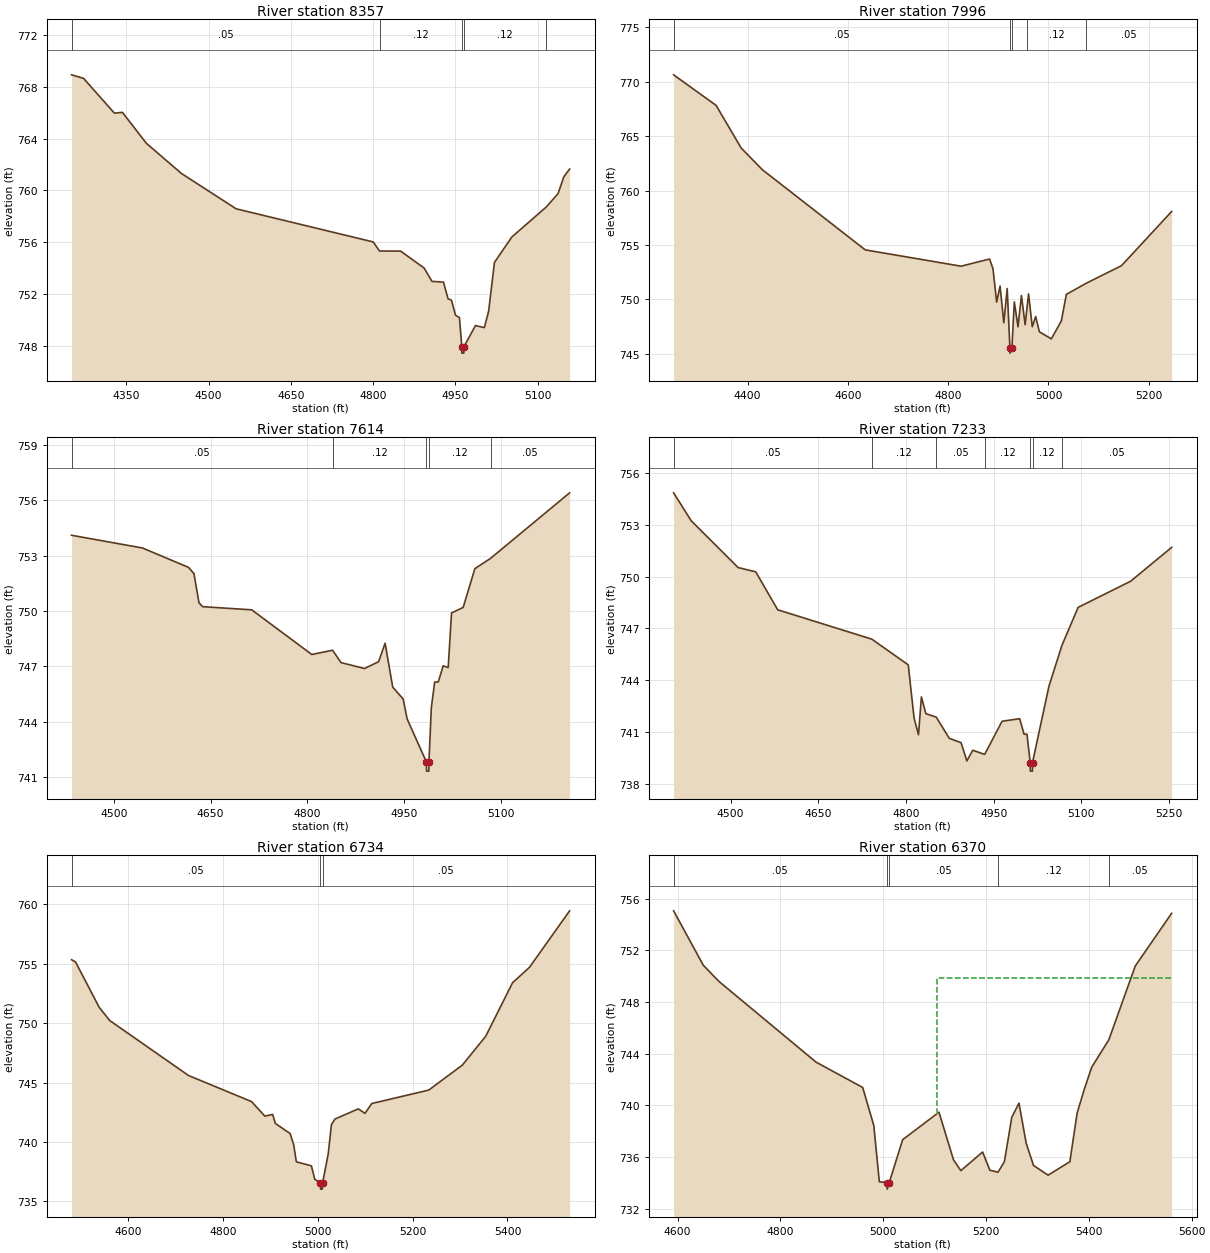
Type RM Length L Ch R = 1,8357,361,361,361
BEGIN DESCRIPTION:
Unnamed Tributary to Walnut Creek 2P 14.0
END DESCRIPTION:
XS GIS Cut Line= 3
      2313029.03      7038409.97      2313479.00      7037810.00
      2313529.01      7037659.97
#Sta/Elev= 30
  4250.0  768.92  4271.8  768.65  4328.1  765.96  4342.7  766.02  4386.4  763.63
  4450.0  761.31  4550.0  758.57  4800.0  756.01  4811.5  755.31  4850.0  755.30
  4892.7  754.00  4907.2  752.96  4928.1  752.91  4936.4  751.62  4942.7  751.51
  4950.0  750.35  4957.2  750.17  4961.5  747.92  4961.7  747.42  4965.2  747.42
  4965.5  747.92  4986.4  749.55  5002.6  749.39  5010.5  750.67  5021.0  754.42
  5052.7  756.39  5115.5  758.71  5137.0  759.74  5147.5  761.04  5158.1  761.64
#Mann=5,-1,0
  4250.0    0.05       0  4811.5    0.12       0  4961.5    0.07       0
  4965.5    0.12       0  5115.5    0.05       0
Bank Sta=4961.5,4965.5
Exp/Cntr=0.3,0.1

Type RM Length L Ch R = 1,7996,382,382,382
BEGIN DESCRIPTION:
Unnamed Tributary to Walnut Creek 2P 13.0
END DESCRIPTION:
XS GIS Cut Line= 3
      2313178.98      7038560.03      2313679.00      7038010.00
      2313679.00      7037760.04
#Sta/Elev= 30
  4252.4  770.64  4337.2  767.83  4387.2  763.91  4429.1  761.93  4634.6  754.55
  4825.8  753.05  4882.6  753.71  4889.3  752.83  4896.7  749.75  4903.5  751.23
  4910.9  747.85  4917.7  750.99  4923.1  745.56  4923.4  745.06  4927.1  745.56
  4931.9  749.77  4939.3  747.48  4946.1  750.36  4953.5  747.67  4957.6  749.38
  4960.3  750.50  4967.7  747.48  4974.5  748.42  4981.9  747.02  5005.7  746.37
  5025.7  748.02  5035.7  750.46  5074.8  751.47  5145.7  753.10  5245.7  758.08
#Mann=5,-1,0
  4252.4    0.05       0  4923.1    0.07       0  4927.1    0.05       0
  4957.6    0.12       0  5074.8    0.05       0
Bank Sta=4923.1,4927.1
Exp/Cntr=0.3,0.1

Type RM Length L Ch R = 1,7614,381,381,381
BEGIN DESCRIPTION:
Unnamed Tributary to Walnut Creek 2P 12.0
END DESCRIPTION:
XS GIS Cut Line= 3
      2313758.62      7038406.54      2314029.00      7037910.00
      2313979.01      7037710.04
#Sta/Elev= 30
  4434.6  754.10  4544.5  753.41  4615.8  752.36  4624.2  752.02  4632.0  750.44
  4637.7  750.23  4713.7  750.06  4806.7  747.64  4838.9  747.87  4852.0  747.20
  4888.4  746.88  4910.2  747.25  4920.3  748.25  4932.1  745.87  4948.2  745.23
  4954.4  744.15  4984.2  741.82  4984.5  741.32  4988.0  741.32  4988.2  741.82
  4991.9  744.76  4997.1  746.15  5002.6  746.15  5010.3  747.03  5018.0  746.93
  5023.2  749.89  5041.2  750.19  5059.3  752.29  5083.7  752.85  5206.1  756.40
#Mann=5,-1,0
  4434.6    0.05       0  4838.9    0.12       0  4984.2    0.07       0
  4988.2    0.12       0  5083.7    0.05       0
Bank Sta=4984.2,4988.2
Exp/Cntr=0.3,0.1

Type RM Length L Ch R = 1,7233,499,499,499
BEGIN DESCRIPTION:
Unnamed Tributary to Walnut Creek 2P 11.0
END DESCRIPTION:
XS GIS Cut Line= 3
      2314329.00      7038609.97      2314379.00      7038010.00
      2314379.00      7037760.05
#Sta/Elev= 30
  4402.4  754.86  4432.5  753.24  4512.7  750.53  4542.9  750.28  4580.5  748.08
  4741.4  746.38  4803.8  744.89  4813.8  741.80  4821.3  740.84  4826.3  743.03
  4833.9  742.06  4851.7  741.86  4874.0  740.63  4894.1  740.38  4904.1  739.32
  4914.1  739.94  4934.5  739.70  4964.3  741.62  4994.4  741.77  5001.9  740.87
  5006.9  740.87  5012.4  739.23  5012.7  738.73  5016.2  738.73  5016.4  739.23
  5044.4  743.64  5066.7  746.02  5094.4  748.22  5184.4  749.74  5254.4  751.70
#Mann=7,-1,0
  4402.4    0.05       0  4741.4    0.12       0  4851.7    0.05       0
  4934.5    0.12       0  5012.4    0.07       0  5016.4    0.12       0
  5066.7    0.05       0
Bank Sta=5012.4,5016.4
Exp/Cntr=0.3,0.1

Type RM Length L Ch R = 1,6734,364,364,364
BEGIN DESCRIPTION:
Unnamed Tributary to Walnut Creek 2P 10.0
END DESCRIPTION:
XS GIS Cut Line= 3
      2314528.99      7038660.01      2314766.73      7038197.34
      2315128.98      7037810.02
#Sta/Elev= 30
  4480.6  755.34  4488.9  755.16  4538.9  751.33  4561.1  750.22  4727.3  745.59
  4860.4  743.39  4888.2  742.17  4904.8  742.31  4910.4  741.55  4941.6  740.70
  4949.1  739.76  4954.7  738.32  4986.5  737.98  4993.5  736.86  5005.6  736.52
  5005.9  736.02  5009.5  736.02  5009.9  736.52  5021.9  738.97  5028.7  741.45
  5036.0  741.92  5085.4  742.78  5099.5  742.40  5113.7  743.23  5233.9  744.36
  5304.7  746.46  5354.1  748.89  5410.7  753.40  5446.4  754.70  5531.1  759.46
#Mann=3,-1,0
  4480.6    0.05       0  5005.6    0.04       0  5009.9    0.05       0
Bank Sta=5005.6,5009.9
Exp/Cntr=0.3,0.1

Type RM Length L Ch R = 1,6370,470,470,470
BEGIN DESCRIPTION:
Unnamed Tributary to Walnut Creek 2P 9.0
END DESCRIPTION:
XS GIS Cut Line= 3
      2314579.01      7038709.99      2314929.00      7038510.00
      2315329.01      7038109.99
#Sta/Elev= 30
  4592.3  755.05  4649.9  750.85  4680.8  749.58  4869.4  743.35  4960.1  741.39
  4981.7  738.45  4992.5  734.10  5007.4  734.03  5007.7  733.53  5011.7  734.03
  5037.8  737.35  5108.5  739.48  5136.8  735.79  5151.0  734.96  5193.4  736.40
  5207.5  734.99  5223.4  734.84  5235.8  735.66  5250.0  739.07  5264.1  740.18
  5278.2  737.07  5292.4  735.36  5320.7  734.61  5363.1  735.65  5377.2  739.41
  5391.4  741.28  5405.5  742.95  5438.9  745.08  5490.4  750.79  5561.1  754.86
#Mann=5,-1,0
  4592.3    0.05       0  5007.4   0.033       0  5011.7    0.05       0
  5223.4    0.12       0  5438.9    0.05       0
#XS Ineff=2,0
       0                 5105.10    0.00  749.82
Permanent Ineff=
       F       F
Bank Sta=5007.4,5011.7
Exp/Cntr=0.3,0.1

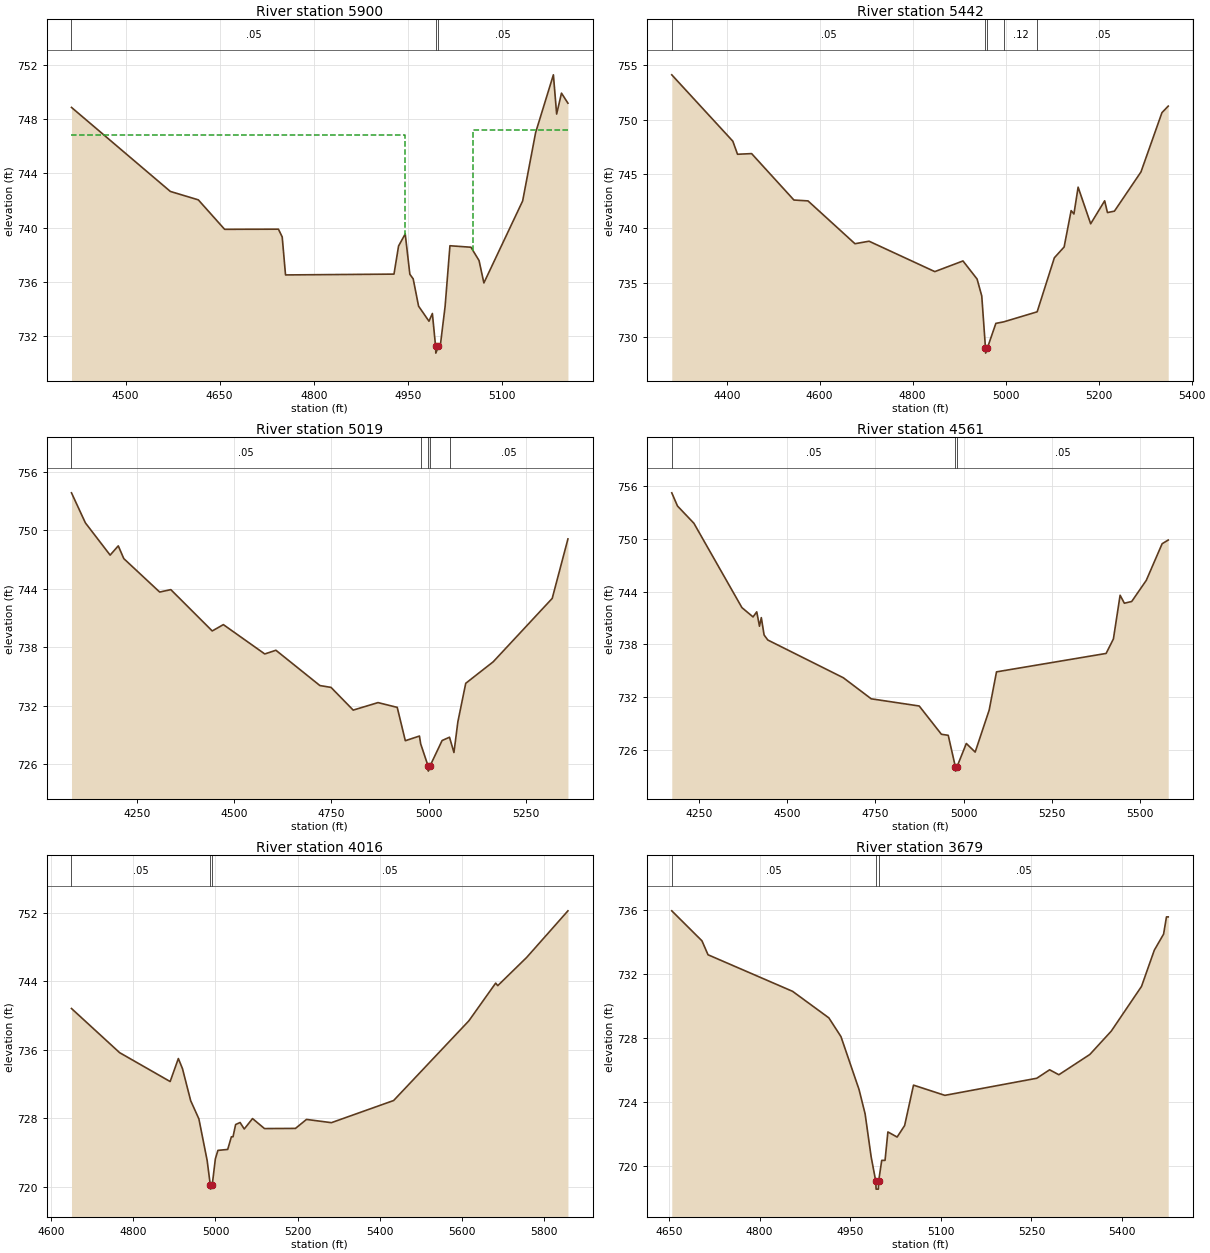
Type RM Length L Ch R = 1,5900,458,458,458
BEGIN DESCRIPTION:
Unnamed Tributary to Walnut Creek 2P 8.0
END DESCRIPTION:
XS GIS Cut Line= 3
      2314728.99      7038760.00      2315279.00      7038560.00
      2315479.00      7038510.00
#Sta/Elev= 30
  4413.9  748.86  4571.5  742.67  4616.1  742.05  4658.0  739.88  4743.8  739.89
  4749.8  739.32  4755.1  736.52  4928.0  736.58  4935.3  738.65  4945.9  739.54
  4953.3  736.57  4958.6  736.23  4967.2  734.22  4983.8  733.11  4989.2  733.68
  4994.3  731.26  4994.7  730.76  4998.7  731.26  5001.7  731.26  5009.5  734.21
  5017.2  738.67  5050.7  738.56  5063.6  737.58  5071.3  735.93  5133.1  741.97
  5153.8  747.01  5182.1  751.26  5187.3  748.37  5195.0  749.91  5205.3  749.17
#Mann=3,-1,0
  4413.9    0.05       0  4994.3   0.033       0  4998.7    0.05       0
#XS Ineff=2,0
    0.00 4946.10  746.86 5053.90    0.00  747.17
Permanent Ineff=
       F       F
Bank Sta=4994.3,4998.7
Exp/Cntr=0.3,0.1

Type RM Length L Ch R = 1,5442,423,423,423
BEGIN DESCRIPTION:
Unnamed Tributary to Walnut Creek 2P 7.0
END DESCRIPTION:
XS GIS Cut Line= 3
      2314628.99      7038810.00      2315329.00      7038910.00
      2315629.02      7038709.98
#Sta/Elev= 30
  4281.9  754.10  4413.2  748.01  4423.3  746.81  4453.6  746.87  4544.6  742.61
  4574.9  742.53  4675.9  738.60  4706.2  738.83  4847.6  736.04  4908.2  737.02
  4938.5  735.36  4948.6  733.80  4956.5  729.06  4956.9  728.56  4960.9  729.06
  4978.9  731.29  4995.8  731.43  5067.7  732.35  5104.7  737.31  5125.7  738.30
  5140.8  741.64  5146.8  741.33  5155.8  743.79  5182.8  740.43  5212.9  742.54
  5218.9  741.46  5233.9  741.59  5291.0  745.19  5336.1  750.63  5349.6  751.23
#Mann=5,-1,0
  4281.9    0.05       0  4956.5    0.07       0  4960.9    0.05       0
  4995.8    0.12       0  5067.7    0.05       0
Bank Sta=4956.5,4960.9
Exp/Cntr=0.3,0.1

Type RM Length L Ch R = 1,5019,458,458,458
BEGIN DESCRIPTION:
Unnamed Tributary to Walnut Creek 2P 6.0
END DESCRIPTION:
XS GIS Cut Line= 3
      2315029.01      7039859.99      2315629.00      7039160.00
      2315679.00      7038810.00
#Sta/Elev= 30
  4082.5  753.84  4118.2  750.76  4181.8  747.45  4202.7  748.40  4216.9  747.09
  4309.1  743.66  4337.7  743.91  4444.1  739.67  4472.7  740.32  4579.1  737.31
  4607.7  737.69  4720.7  734.07  4749.3  733.88  4806.3  731.55  4870.0  732.32
  4919.4  731.83  4940.2  728.41  4976.5  728.89  4979.7  728.08  4998.9  725.79
  4999.3  725.29  5003.3  725.79  5034.7  728.43  5053.7  728.77  5065.1  727.20
  5075.2  730.35  5095.4  734.30  5166.1  736.51  5317.6  743.01  5358.0  749.11
#Mann=5,-1,0
  4082.5    0.05       0  4979.7    0.12       0  4998.9    0.07       0
  5003.3    0.12       0  5053.7    0.05       0
Bank Sta=4998.9,5003.3
Exp/Cntr=0.3,0.1

Type RM Length L Ch R = 1,4561,545,545,545
BEGIN DESCRIPTION:
Unnamed Tributary to Walnut Creek 2P 5.0
END DESCRIPTION:
XS GIS Cut Line= 3
      2316179.00      7040109.98      2315929.00      7039310.00
      2315779.01      7038760.02
#Sta/Elev= 30
  4172.2  755.26  4188.4  753.76  4235.0  751.79  4371.2  742.18  4402.7  741.12
  4413.2  741.70  4421.0  740.06  4426.2  741.04  4434.1  739.06  4444.6  738.49
  4658.8  734.19  4737.9  731.79  4874.1  730.97  4937.0  727.75  4956.4  727.63
  4976.6  724.05  4977.1  723.55  4981.3  724.05  5007.7  726.70  5032.8  725.72
  5072.5  730.50  5093.3  734.86  5404.2  736.96  5424.9  738.61  5443.9  743.59
  5456.0  742.68  5476.8  742.88  5518.2  745.29  5563.1  749.46  5580.4  749.88
#Mann=3,-1,0
  4172.2    0.05       0  4976.6   0.033       0  4981.3    0.05       0
Bank Sta=4976.6,4981.3
Exp/Cntr=0.3,0.1

Type RM Length L Ch R = 1,4016,337,337,337
BEGIN DESCRIPTION:
Unnamed Tributary to Walnut Creek 2P 4.0
END DESCRIPTION:
XS GIS Cut Line= 3
      2316329.00      7039859.98      2316345.49      7039467.01
      2316229.00      7038659.99
#Sta/Elev= 30
  4649.4  740.83  4766.5  735.67  4889.6  732.29  4909.6  734.98  4919.6  733.80
  4939.6  730.05  4959.6  727.92  4979.7  723.06  4987.3  720.21  4987.8  719.71
  4992.1  720.21  4999.7  723.26  5005.9  724.24  5029.7  724.35  5038.7  725.83
  5042.7  725.83  5049.0  727.26  5059.9  727.50  5070.0  726.74  5090.2  727.96
  5119.3  726.79  5194.7  726.81  5221.6  727.86  5282.2  727.48  5433.7  730.07
  5616.9  739.39  5682.2  743.80  5687.2  743.50  5757.6  746.80  5858.1  752.25
#Mann=3,-1,0
  4649.4    0.05       0  4987.3   0.033       0  4992.1    0.05       0
Bank Sta=4987.3,4992.1
Exp/Cntr=0.3,0.1

Type RM Length L Ch R = 1,3679,409,409,409
BEGIN DESCRIPTION:
Unnamed Tributary to Walnut Creek 2P 3.0
END DESCRIPTION:
XS GIS Cut Line= 3
      2316629.00      7039710.00      2316629.00      7039360.00
      2316379.00      7038960.00
#Sta/Elev= 30
  4654.8  735.95  4704.8  734.07  4714.8  733.20  4854.8  730.91  4914.8  729.25
  4934.8  728.08  4964.8  724.76  4974.8  723.24  4984.8  720.55  4992.4  719.03
  4993.0  718.53  4996.7  718.53  4997.2  719.03  5002.3  720.33  5007.8  720.33
  5012.5  722.11  5027.8  721.79  5040.2  722.51  5054.9  725.04  5106.8  724.40
  5258.9  725.47  5280.2  726.00  5295.5  725.69  5346.8  726.96  5382.2  728.42
  5432.3  731.22  5453.5  733.49  5468.8  734.49  5473.6  735.57  5476.5  735.57
#Mann=3,-1,0
  4654.8    0.05       0  4992.4   0.033       0  4997.2    0.05       0
Bank Sta=4992.4,4997.2
Exp/Cntr=0.3,0.1

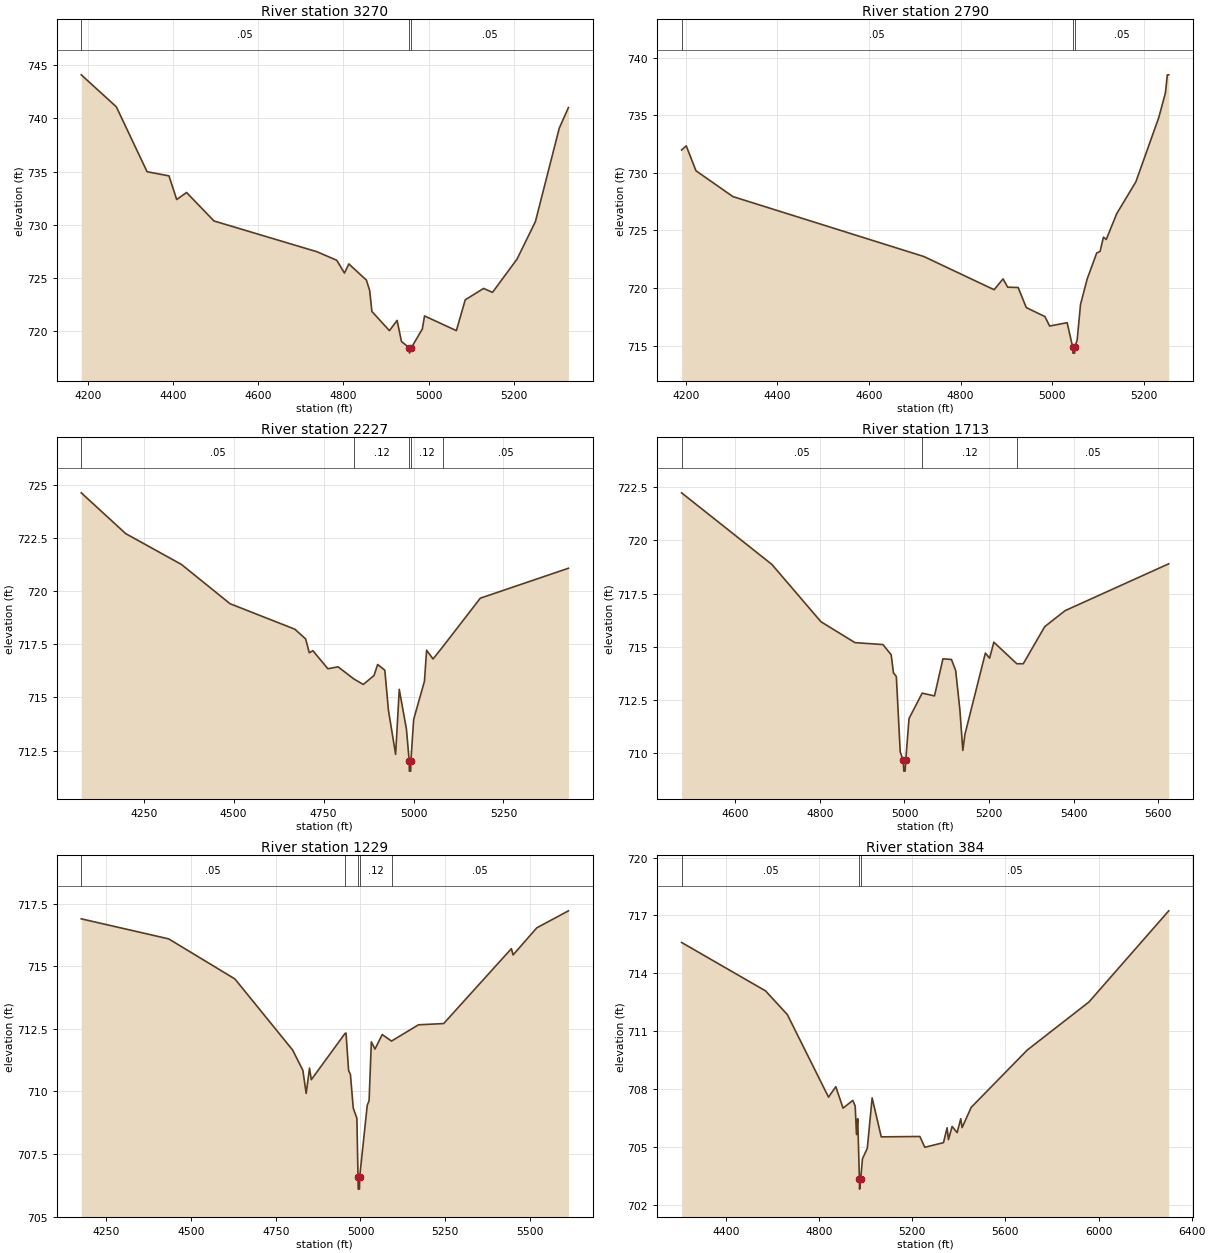
Type RM Length L Ch R = 1,3270,480,480,480
BEGIN DESCRIPTION:
Unnamed Tributary to Walnut Creek 2P 2.0
END DESCRIPTION:
XS GIS Cut Line= 3
      2316978.99      7039859.97      2316779.00      7039060.00
      2316529.04      7038860.03
#Sta/Elev= 30
  4183.9  744.08  4266.3  741.08  4338.5  734.99  4390.0  734.60  4408.1  732.38
  4431.3  733.04  4495.7  730.37  4737.9  727.48  4784.3  726.68  4802.3  725.48
  4812.6  726.34  4853.9  724.82  4861.6  723.84  4866.8  721.88  4908.0  720.08
  4926.0  721.04  4936.3  719.06  4954.6  718.47  4955.1  717.97  4959.4  718.47
  4985.3  720.24  4990.5  721.46  5065.3  720.08  5086.1  722.97  5129.3  724.04
  5150.2  723.67  5207.8  726.79  5251.0  730.31  5307.0  739.07  5328.6  741.01
#Mann=3,-1,0
  4183.9    0.05       0  4954.6   0.033       0  4959.4    0.05       0
Bank Sta=4954.6,4959.4
Exp/Cntr=0.3,0.1

Type RM Length L Ch R = 1,2790,563,563,563
BEGIN DESCRIPTION:
Unnamed Tributary to Walnut Creek 2P 1.0
END DESCRIPTION:
XS GIS Cut Line= 3
      2316978.99      7039610.04      2317129.00      7038810.00
      2316928.98      7038659.99
#Sta/Elev= 30
  4190.8  731.98  4201.0  732.34  4222.2  730.18  4302.8  727.94  4719.9  722.74
  4873.4  719.86  4892.9  720.80  4903.0  720.08  4925.9  720.05  4943.7  718.31
  4984.4  717.53  4994.6  716.71  5032.9  717.00  5045.1  714.86  5045.6  714.36
  5049.3  714.36  5049.9  714.86  5054.8  715.51  5062.1  718.58  5076.7  720.80
  5097.5  723.05  5104.8  723.18  5112.1  724.42  5118.3  724.22  5141.2  726.46
  5182.9  729.21  5232.9  734.78  5247.5  736.92  5251.7  738.50  5254.8  738.50
#Mann=3,-1,0
  4190.8    0.05       0  5045.1   0.033       0  5049.9    0.05       0
Bank Sta=5045.1,5049.9
Exp/Cntr=0.3,0.1

Type RM Length L Ch R = 1,2227,514,514,514
BEGIN DESCRIPTION:
UNT Walnut Ck 2P 0.5
END DESCRIPTION:
XS GIS Cut Line= 3
      2317577.12      7039633.48      2317600.90      7038672.87
      2317377.39      7038349.50
#Sta/Elev= 30
  4076.6  724.63  4200.1  722.71  4354.9  721.26  4490.2  719.41  4670.3  718.21
  4700.3  717.75  4710.3  717.10  4720.3  717.20  4762.0  716.35  4790.3  716.44
  4834.1  715.87  4860.3  715.61  4890.3  716.03  4900.3  716.55  4920.3  716.28
  4930.3  714.40  4950.3  712.32  4960.4  715.38  4980.4  713.50  4987.9  712.03
  4988.5  711.53  4992.2  711.53  4992.8  712.03  5000.4  713.96  5030.4  715.76
  5036.4  717.22  5054.4  716.81  5082.1  717.40  5185.6  719.67  5430.6  721.08
#Mann=5,-1,0
  4076.6    0.05       0  4834.1    0.12       0  4987.9    0.07       0
  4992.8    0.12       0  5082.1    0.05       0
Bank Sta=4987.9,4992.8
Exp/Cntr=0.3,0.1

Type RM Length L Ch R = 1,1713,484,484,484
BEGIN DESCRIPTION:
UNT Walnut Ck 2P 0.4
END DESCRIPTION:
XS GIS Cut Line= 4
      2317689.82      7039456.03      2317865.26      7038984.96
      2317837.80      7038586.04      2317596.13      7038525.45
#Sta/Elev= 30
  4473.1  722.23  4686.6  718.87  4802.6  716.18  4883.0  715.20  4949.1  715.11
  4968.6  714.63  4974.0  713.78  4980.8  713.61  4990.0  710.07  4997.0  709.67
  4998.5  709.17  5001.5  709.17  5003.0  709.67  5010.8  711.64  5041.9  712.83
  5071.0  712.70  5091.0  714.44  5111.1  714.41  5121.1  713.89  5131.1  712.03
  5138.0  710.14  5143.0  710.90  5191.3  714.71  5201.3  714.47  5211.3  715.22
  5265.6  714.21  5280.9  714.21  5331.6  715.95  5379.7  716.70  5624.8  718.90
#Mann=3,-1,0
  4473.1    0.05       0  5041.9    0.12       0  5265.6    0.05       0
Bank Sta=4997,5003
Exp/Cntr=0.3,0.1

Type RM Length L Ch R = 1,1229,845,845,845
BEGIN DESCRIPTION:
UNT Walnut Ck 2P 0.3
END DESCRIPTION:
XS GIS Cut Line= 3
      2318523.41      7039581.10      2318143.00      7038573.01
      2317786.39      7038520.71
#Sta/Elev= 30
  4176.0  716.89  4434.1  716.09  4629.5  714.49  4800.0  711.65  4830.1  710.84
  4839.8  709.92  4849.7  710.93  4855.0  710.47  4954.7  712.32  4957.4  712.33
  4965.1  710.83  4970.4  710.68  4978.8  709.33  4989.5  708.93  4992.8  706.60
  4993.4  706.10  4997.1  706.10  4997.8  706.60  5020.1  709.45  5025.5  709.63
  5032.2  711.98  5042.9  711.69  5064.3  712.27  5091.7  712.01  5171.2  712.66
  5245.7  712.71  5445.5  715.70  5450.6  715.45  5520.4  716.53  5613.9  717.21
#Mann=5,-1,0
  4176.0    0.05       0  4954.7    0.12       0  4992.8    0.07       0
  4997.8    0.12       0  5091.7    0.05       0
Bank Sta=4992.8,4997.8
Exp/Cntr=0.3,0.1

Type RM Length L Ch R = 1,384,0,0,0
BEGIN DESCRIPTION:
UNT Walnut Ck 2P 0.2
END DESCRIPTION:
XS GIS Cut Line= 4
      2318656.57      7039576.42      2318913.37      7038682.38
      2318670.84      7038539.72      2317792.55      7038482.75
#Sta/Elev= 30
  4209.9  715.60  4570.3  713.09  4664.0  711.86  4840.8  707.58  4872.1  708.12
  4903.3  707.01  4944.9  707.41  4955.3  707.12  4960.9  705.64  4966.1  706.46
  4973.5  703.31  4974.2  702.81  4978.7  703.31  4986.5  704.38  5007.3  704.93
  5028.1  707.54  5067.2  705.52  5232.9  705.54  5254.3  704.98  5334.4  705.22
  5350.0  705.99  5355.8  705.38  5371.5  706.06  5393.0  705.74  5408.6  706.46
  5414.4  706.00  5453.4  707.05  5693.9  710.02  5958.7  712.51  6301.6  717.24
#Mann=3,-1,0
  4209.9    0.05       0  4973.5   0.033       0  4978.7    0.05       0
Bank Sta=4973.5,4978.7
Exp/Cntr=0.3,0.1

Chan Stop Cuts=-1