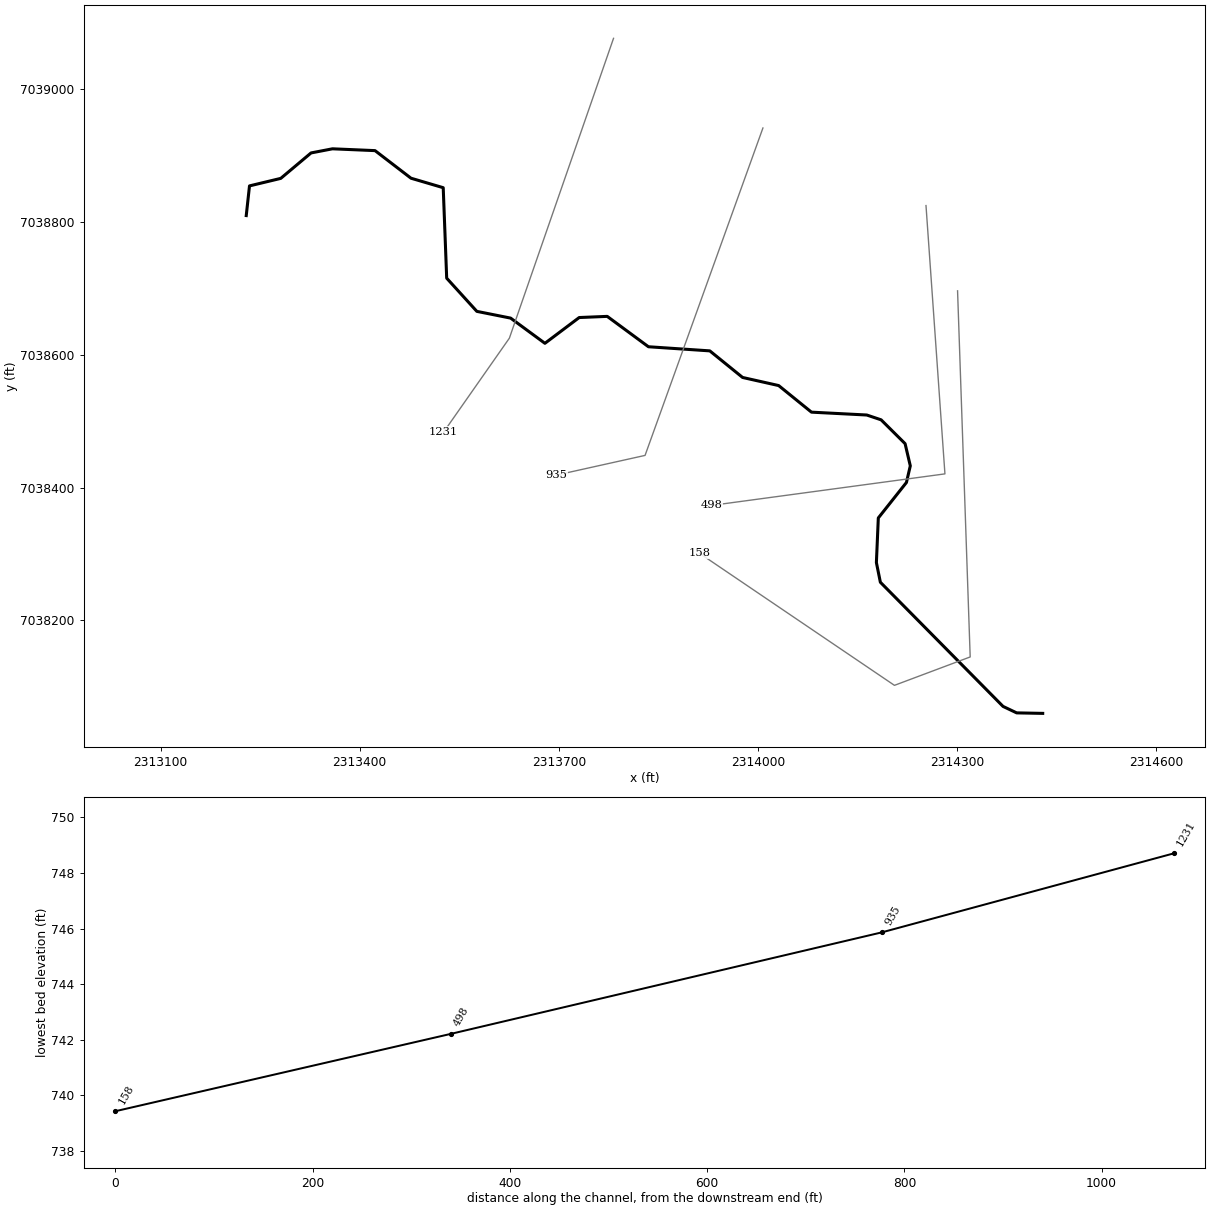
--- Unnamed Tr to Walnut Cr 2Q.prj (project) ---

Proj Title=Unnamed Tr to Walnut Cr 2Q Base Level Engineering
Current Plan=p01
Default Exp/Contr=0.3,0.1
English Units
Geom File=g01
Flow File=f01
Plan File=p01
BEGIN DESCRIPTION:
Unnamed Tr to Walnut Cr 2Q
END DESCRIPTION:

--- Unnamed Tr to Walnut Cr 2Q.p01 (plan) ---

Plan Title=Multiple Run
Short Identifier=Multiple
Geom File=g01
Flow File=f01
Subcritical Flow
K Sum by GR= 0
Std Step Tol= 0.01
Critical Tol= 0.01
Num of Std Step Trials= 20
Max Error Tol= 0.3
Flow Tol Ratio= 0.001
Split Flow NTrial= 30
Split Flow Tol= 0.02
Split Flow Ratio= 0.02
Log Output Level= 0
Friction Slope Method= 1
Unsteady Friction Slope Method= 2
Unsteady Bridges Friction Slope Method= 1
Parabolic Critical Depth
Global Vel Dist=  1 , 1 , 1
Global Log Level= 0
CheckData=True
Encroach Param= -1, 0, 0, 0
BEGIN DESCRIPTION:
Multiple Run
END DESCRIPTION:

--- Unnamed Tr to Walnut Cr 2Q.f01 (steady flow) ---

Flow Title=Multiple
Number of Profiles=7
Profile Names=10-year,25-year,50-year,1pct_min,100-year,1pct_plu,500-year
River Rch & RM= Unnamed Tr to Wa,Reach-1,1231
     377     499     595     353     705    1410     985
Boundary for River Rch & Prof#=Unnamed Tr to Wa,Reach-1,1
Up Type=0
Dn Type=3
Dn Slope=0.005
Boundary for River Rch & Prof#=Unnamed Tr to Wa,Reach-1,2
Up Type=0
Dn Type=3
Dn Slope=0.005
Boundary for River Rch & Prof#=Unnamed Tr to Wa,Reach-1,3
Up Type=0
Dn Type=3
Dn Slope=0.005
Boundary for River Rch & Prof#=Unnamed Tr to Wa,Reach-1,4
Up Type=0
Dn Type=3
Dn Slope=0.005
Boundary for River Rch & Prof#=Unnamed Tr to Wa,Reach-1,5
Up Type=0
Dn Type=3
Dn Slope=0.005
Boundary for River Rch & Prof#=Unnamed Tr to Wa,Reach-1,6
Up Type=0
Dn Type=3
Dn Slope=0.005
Boundary for River Rch & Prof#=Unnamed Tr to Wa,Reach-1,7
Up Type=0
Dn Type=3
Dn Slope=0.005

--- Unnamed Tr to Walnut Cr 2Q.g01 (geometry) ---

Geom Title=Existing Conditions

River Reach=Unnamed Tr to Wa,Reach-1
Reach XY= 30
      2313229.00      7038810.00      2313233.90      7038854.72
      2313281.00      7038866.05      2313326.64      7038904.39
      2313358.94      7038910.61      2313423.06      7038907.87
      2313477.22      7038866.31      2313525.77      7038852.01
      2313531.00      7038715.68      2313576.42      7038665.69
      2313627.32      7038655.53      2313679.00      7038617.56
      2313730.64      7038656.39      2313772.87      7038658.14
      2313834.97      7038612.38      2313927.42      7038606.17
      2313976.82      7038566.11      2314031.18      7038553.89
      2314080.59      7038513.83      2314163.94      7038509.53
      2314185.55      7038502.26      2314221.65      7038466.38
      2314229.50      7038432.93      2314223.66      7038407.85
      2314181.31      7038354.44      2314178.41      7038287.21
      2314184.40      7038257.57      2314369.21      7038070.51
      2314389.76      7038060.75      2314429.00      7038060.00

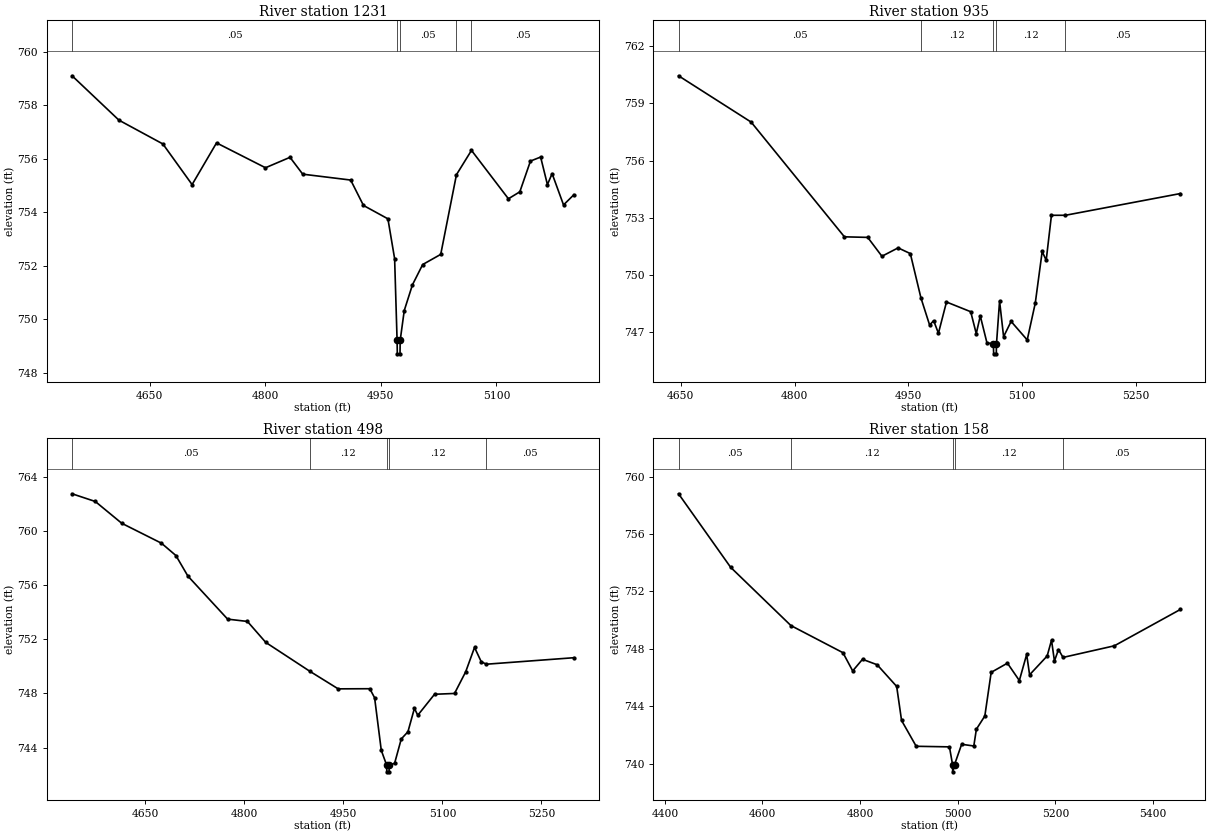
Type RM Length L Ch R = 1,1231,296,296,296
BEGIN DESCRIPTION:
Unnamed Tributary to Walnut Creek 2Q 3.0
END DESCRIPTION:
XS GIS Cut Line= 3
      2313782.37      7039077.05      2313625.45      7038625.32
      2313526.42      7038483.84
#Sta/Elev= 30
  4549.5  759.10  4610.3  757.44  4667.3  756.55  4705.2  755.03  4736.9  756.59
  4800.4  755.66  4832.2  756.05  4848.7  755.42  4910.9  755.20  4927.5  754.25
  4959.2  753.75  4967.9  752.26  4971.1  749.20  4971.4  748.70  4974.9  748.70
  4975.1  749.20  4980.4  750.32  4991.0  751.28  5004.3  752.04  5027.7  752.42
  5048.1  755.40  5067.6  756.31  5115.5  754.50  5130.3  754.76  5144.1  755.91
  5157.3  756.06  5166.1  755.03  5172.2  755.44  5187.0  754.27  5200.4  754.65
#Mann=5,-1,0
  4549.5    0.05       0  4971.1   0.033       0  4975.1    0.05       0
  5048.1    0.12       0  5067.6    0.05       0
Bank Sta=4971.1,4975.1
Exp/Cntr=0.3,0.1

Type RM Length L Ch R = 1,935,437,437,437
BEGIN DESCRIPTION:
UNT Walnut Ck 2Q 2.5
END DESCRIPTION:
XS GIS Cut Line= 3
      2314007.46      7038941.97      2313829.87      7038448.67
      2313696.72      7038419.08
#Sta/Elev= 30
  4647.3  760.45  4742.9  758.02  4865.7  752.00  4896.4  751.97  4915.1  750.98
  4936.4  751.42  4952.5  751.12  4966.5  748.79  4977.9  747.37  4983.2  747.60
  4989.5  746.94  5000.1  748.58  5032.0  748.07  5039.3  746.92  5044.6  747.85
  5053.3  746.45  5061.9  746.36  5062.2  745.86  5065.7  745.86  5065.9  746.36
  5070.0  748.63  5075.3  746.76  5085.2  747.56  5106.4  746.59  5117.0  748.52
  5126.1  751.23  5131.4  750.77  5138.3  753.13  5156.7  753.13  5308.0  754.27
#Mann=5,-1,0
  4647.3    0.05       0  4966.5    0.12       0  5061.9    0.07       0
  5065.9    0.12       0  5156.7    0.05       0
Bank Sta=5061.9,5065.9
Exp/Cntr=0.3,0.1

Type RM Length L Ch R = 1,498,340,340,340
BEGIN DESCRIPTION:
Unnamed Tributary to Walnut Creek 2Q 2.0
END DESCRIPTION:
XS GIS Cut Line= 3
      2314253.15      7038825.08      2314281.68      7038420.84
      2313929.83      7038373.29
#Sta/Elev= 30
  4538.8  762.75  4574.0  762.18  4614.1  760.57  4674.2  759.10  4696.1  758.19
  4714.3  756.67  4774.5  753.49  4804.5  753.32  4832.3  751.77  4899.0  749.64
  4942.0  748.34  4989.9  748.35  4997.2  747.68  5007.3  743.80  5015.4  742.71
  5015.6  742.21  5019.1  742.21  5019.4  742.71  5027.5  742.84  5037.6  744.64
  5047.7  745.17  5057.5  746.90  5062.6  746.39  5088.0  747.94  5118.3  748.00
  5135.2  749.60  5148.6  751.40  5158.7  750.35  5166.4  750.16  5299.1  750.64
#Mann=5,-1,0
  4538.8    0.05       0  4899.0    0.12       0  5015.4    0.07       0
  5019.4    0.12       0  5166.4    0.05       0
Bank Sta=5015.4,5019.4
Exp/Cntr=0.3,0.1

Type RM Length L Ch R = 1,158,0,0,0
BEGIN DESCRIPTION:
Unnamed Tributary to Walnut Creek 2Q 1.0
END DESCRIPTION:
XS GIS Cut Line= 4
      2314300.71      7038696.63      2314319.73      7038145.03
      2314205.60      7038102.23      2313912.36      7038300.88
#Sta/Elev= 30
  4428.0  758.80  4534.7  753.68  4658.2  749.62  4764.8  747.73  4784.8  746.46
  4804.9  747.27  4834.9  746.89  4874.9  745.38  4884.9  743.01  4914.9  741.21
  4983.0  741.17  4989.4  739.93  4989.6  739.43  4993.4  739.93  5008.0  741.35
  5032.9  741.23  5038.2  742.40  5055.5  743.32  5068.5  746.36  5101.8  747.00
  5126.2  745.79  5141.2  747.61  5147.2  746.19  5183.2  747.50  5192.1  748.60
  5198.1  747.15  5206.4  747.95  5215.7  747.40  5320.9  748.21  5456.0  750.74
#Mann=5,-1,0
  4428.0    0.05       0  4658.2    0.12       0  4989.4    0.07       0
  4993.4    0.12       0  5215.7    0.05       0
Bank Sta=4989.4,4993.4
Exp/Cntr=0.3,0.1

Chan Stop Cuts=-1