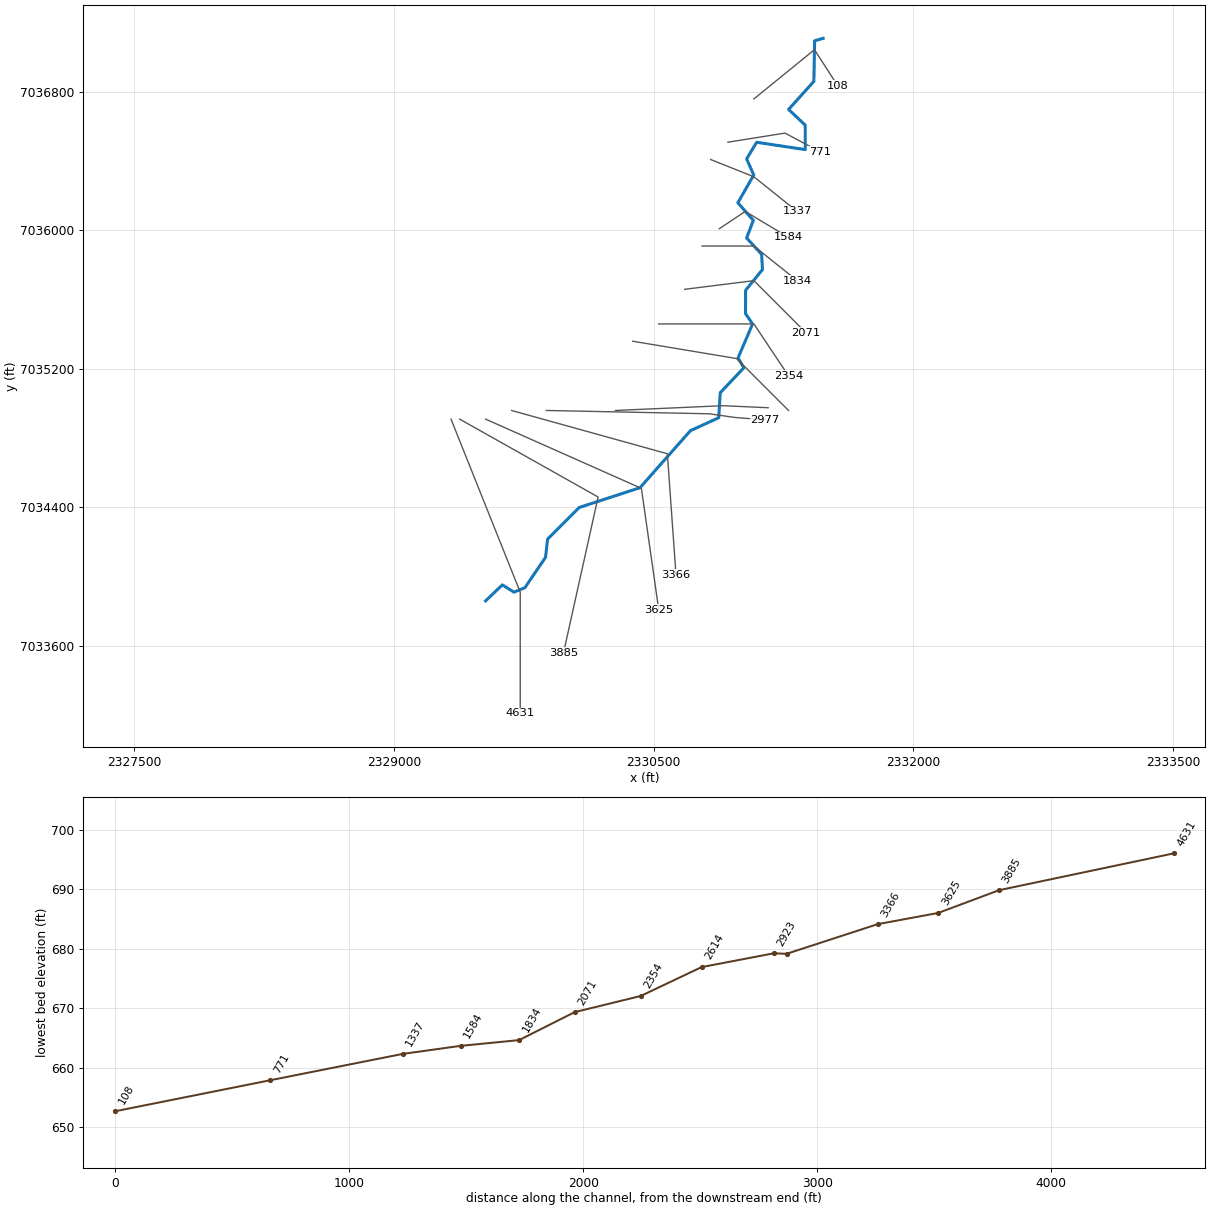
--- Unnamed Tr to Walnut Cr 2R.prj (project) ---

Proj Title=Unnamed Tr to Walnut Cr 2R Base Level Engineering
Current Plan=p01
Default Exp/Contr=0.3,0.1
English Units
Geom File=g01
Flow File=f01
Plan File=p01
BEGIN DESCRIPTION:
Unnamed Tr to Walnut Cr 2R
END DESCRIPTION:

--- Unnamed Tr to Walnut Cr 2R.p01 (plan) ---

Plan Title=Multiple Run
Short Identifier=Multiple
Geom File=g01
Flow File=f01
Subcritical Flow
K Sum by GR= 0
Std Step Tol= 0.01
Critical Tol= 0.01
Num of Std Step Trials= 20
Max Error Tol= 0.3
Flow Tol Ratio= 0.001
Split Flow NTrial= 30
Split Flow Tol= 0.02
Split Flow Ratio= 0.02
Log Output Level= 0
Friction Slope Method= 1
Unsteady Friction Slope Method= 2
Unsteady Bridges Friction Slope Method= 1
Parabolic Critical Depth
Global Vel Dist=  1 , 1 , 1
Global Log Level= 0
CheckData=True
Encroach Param= -1, 0, 0, 0
BEGIN DESCRIPTION:
Multiple Run
END DESCRIPTION:

--- Unnamed Tr to Walnut Cr 2R.f01 (steady flow) ---

Flow Title=Multiple
Number of Profiles=7
Profile Names=10-year,25-year,50-year,1pct_min,100-year,1pct_plu,500-year
River Rch & RM= Unnamed Tr to Wa,Reach-1,4631
     537     731     891     540    1080    2150    1570
Boundary for River Rch & Prof#=Unnamed Tr to Wa,Reach-1,1
Up Type=0
Dn Type=3
Dn Slope=0.005
Boundary for River Rch & Prof#=Unnamed Tr to Wa,Reach-1,2
Up Type=0
Dn Type=3
Dn Slope=0.005
Boundary for River Rch & Prof#=Unnamed Tr to Wa,Reach-1,3
Up Type=0
Dn Type=3
Dn Slope=0.005
Boundary for River Rch & Prof#=Unnamed Tr to Wa,Reach-1,4
Up Type=0
Dn Type=3
Dn Slope=0.005
Boundary for River Rch & Prof#=Unnamed Tr to Wa,Reach-1,5
Up Type=0
Dn Type=3
Dn Slope=0.005
Boundary for River Rch & Prof#=Unnamed Tr to Wa,Reach-1,6
Up Type=0
Dn Type=3
Dn Slope=0.005
Boundary for River Rch & Prof#=Unnamed Tr to Wa,Reach-1,7
Up Type=0
Dn Type=3
Dn Slope=0.005

--- Unnamed Tr to Walnut Cr 2R.g01 (geometry) ---

Geom Title=Existing Conditions

River Reach=Unnamed Tr to Wa,Reach-1
Reach XY= 30
      2329529.00      7033860.00      2329625.59      7033952.30
      2329693.07      7033910.33      2329755.88      7033936.02
      2329875.17      7034111.59      2329886.86      7034216.17
      2330069.32      7034399.24      2330420.81      7034513.67
      2330712.32      7034843.36      2330875.77      7034917.99
      2330884.47      7035062.44      2331021.01      7035206.66
      2330987.29      7035263.22      2331071.44      7035460.00
      2331030.54      7035519.60      2331031.17      7035654.55
      2331128.60      7035773.92      2331123.57      7035862.43
      2331036.84      7035956.60      2331075.82      7036058.35
      2330986.30      7036159.92      2331078.20      7036320.70
      2331037.05      7036413.35      2331094.80      7036509.34
      2331375.79      7036467.25      2331375.53      7036608.73
      2331279.39      7036698.98      2331425.46      7036861.46
      2331429.80      7037095.56      2331479.00      7037110.00

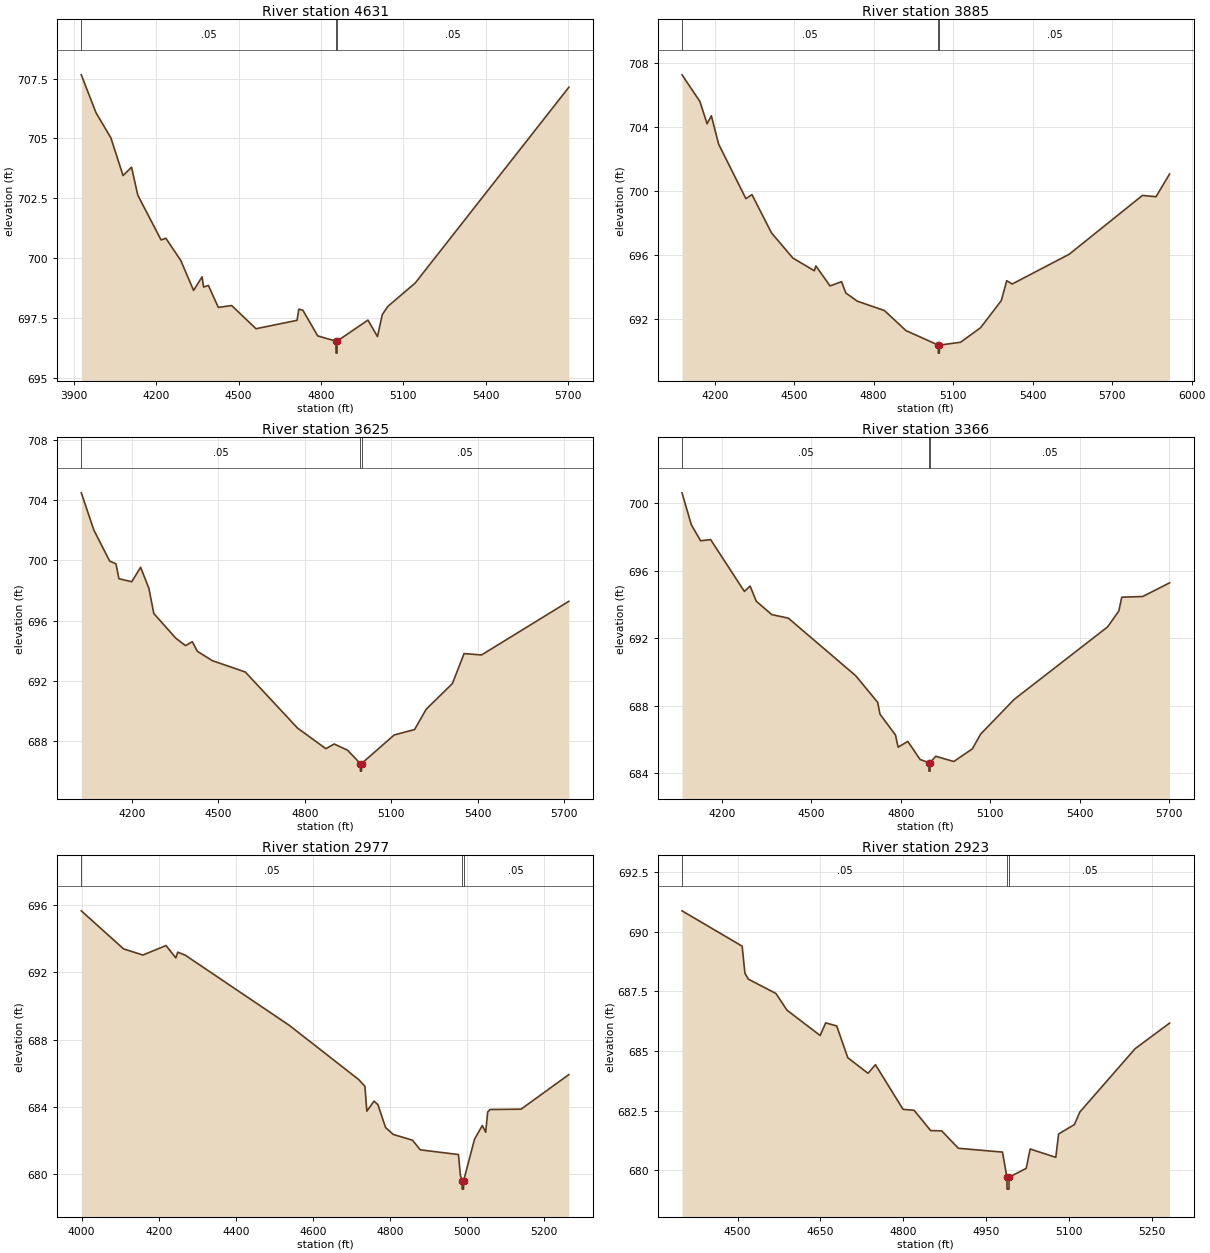
Type RM Length L Ch R = 1,4631,746,746,746
BEGIN DESCRIPTION:
Unnamed Tributary to Walnut Creek 2R 14.0
END DESCRIPTION:
XS GIS Cut Line= 3
      2329328.99      7034910.03      2329729.00      7033910.00
      2329729.00      7033209.96
#Sta/Elev= 30
  3926.5  707.66  3980.4  706.07  4034.2  705.03  4078.7  703.45  4109.6  703.80
  4132.5  702.63  4217.3  700.76  4234.8  700.83  4288.7  699.91  4335.8  698.65
  4366.8  699.22  4372.2  698.79  4389.7  698.86  4426.0  697.94  4474.5  698.02
  4563.3  697.05  4712.8  697.40  4719.5  697.87  4734.3  697.82  4788.2  696.75
  4854.8  696.53  4855.1  696.03  4858.6  696.03  4858.8  696.53  4971.3  697.41
  5006.1  696.72  5023.6  697.64  5043.6  697.98  5143.6  698.96  5703.6  707.14
#Mann=3,-1,0
  3926.5    0.05       0  4854.8   0.033       0  4858.8    0.05       0
Bank Sta=4854.8,4858.8
Exp/Cntr=0.3,0.1

Type RM Length L Ch R = 1,3885,260,260,260
BEGIN DESCRIPTION:
Unnamed Tributary to Walnut Creek 2R 13.0
END DESCRIPTION:
XS GIS Cut Line= 3
      2329379.01      7034910.00      2330179.00      7034460.00
      2329979.01      7033560.02
#Sta/Elev= 30
  4076.9  707.24  4144.1  705.58  4171.5  704.18  4187.5  704.68  4214.9  702.91
  4317.8  699.50  4340.8  699.75  4414.4  697.36  4495.4  695.78  4576.3  694.99
  4582.0  695.29  4635.6  694.04  4678.9  694.31  4694.9  693.60  4738.2  693.09
  4840.8  692.50  4921.8  691.25  5044.0  690.34  5044.2  689.84  5047.7  689.84
  5048.0  690.34  5127.9  690.52  5203.5  691.43  5281.6  693.12  5302.1  694.37
  5322.6  694.16  5537.7  696.02  5814.3  699.70  5865.5  699.62  5916.7  701.04
#Mann=3,-1,0
  4076.9    0.05       0  5044.0    0.04       0  5048.0    0.05       0
Bank Sta=5044,5048
Exp/Cntr=0.3,0.1

Type RM Length L Ch R = 1,3625,259,259,259
BEGIN DESCRIPTION:
Unnamed Tributary to Walnut Creek 2R 12.0
END DESCRIPTION:
XS GIS Cut Line= 3
      2329528.99      7034910.01      2330429.00      7034510.00
      2330529.00      7033810.01
#Sta/Elev= 30
  4024.1  704.48  4067.9  702.00  4122.6  699.95  4144.5  699.77  4154.7  698.78
  4199.2  698.58  4230.0  699.54  4258.7  698.14  4275.8  696.47  4351.7  694.84
  4385.9  694.34  4409.2  694.60  4427.0  693.96  4478.9  693.34  4593.2  692.59
  4774.4  688.87  4872.9  687.50  4901.6  687.81  4948.1  687.40  4992.6  686.51
  4992.9  686.01  4996.4  686.01  4996.6  686.51  5110.0  688.41  5180.7  688.77
  5221.1  690.12  5312.0  691.82  5352.5  693.81  5413.1  693.72  5716.1  697.28
#Mann=3,-1,0
  4024.1    0.05       0  4992.6    0.04       0  4996.6    0.05       0
Bank Sta=4992.6,4996.6
Exp/Cntr=0.3,0.1

Type RM Length L Ch R = 1,3366,389,389,389
BEGIN DESCRIPTION:
Unnamed Tributary to Walnut Creek 2R 11.0
END DESCRIPTION:
XS GIS Cut Line= 3
      2329678.96      7034960.01      2330579.00      7034710.00
      2330629.00      7034010.00
#Sta/Elev= 30
  4065.9  700.60  4097.1  698.71  4128.2  697.76  4161.9  697.83  4275.1  694.76
  4294.3  695.08  4315.0  694.18  4366.9  693.39  4422.4  693.18  4648.7  689.77
  4722.4  688.19  4730.2  687.49  4782.1  686.26  4790.9  685.54  4823.6  685.88
  4864.6  684.81  4894.2  684.62  4894.5  684.12  4898.0  684.12  4898.2  684.62
  4917.0  685.00  4977.7  684.69  5040.1  685.44  5067.7  686.31  5180.5  688.37
  5493.8  692.66  5531.4  693.60  5541.4  694.42  5611.6  694.46  5701.8  695.27
#Mann=3,-1,0
  4065.9    0.05       0  4894.2    0.04       0  4898.2    0.05       0
Bank Sta=4894.2,4898.2
Exp/Cntr=0.3,0.1

Type RM Length L Ch R = 1,2977,54,54,54
BEGIN DESCRIPTION:
Unnamed Tributary to Walnut Creek 2R 10.0
END DESCRIPTION:
XS GIS Cut Line= 4
      2329879.04      7034960.00      2330820.55      7034940.85
      2330967.62      7034919.84      2331142.69      7034905.84
#Sta/Elev= 30
  3999.1  695.63  4109.1  693.37  4159.1  693.01  4219.1  693.57  4244.6  692.84
  4249.6  693.18  4269.1  693.00  4539.2  688.84  4719.2  685.63  4735.5  685.23
  4740.5  683.75  4759.2  684.35  4769.2  684.14  4789.2  682.78  4809.2  682.37
  4859.2  682.03  4879.2  681.46  4978.4  681.18  4983.4  679.95  4987.8  679.63
  4988.0  679.13  4991.5  679.13  4991.8  679.63  5020.1  682.09  5040.3  682.90
  5049.1  682.50  5054.2  683.70  5060.5  683.85  5140.9  683.87  5265.0  685.92
#Mann=3,-1,0
  3999.1    0.05       0  4987.8    0.04       0  4991.8    0.05       0
Bank Sta=4987.8,4991.8
Exp/Cntr=0.3,0.1

Type RM Length L Ch R = 1,2923,309,309,309
BEGIN DESCRIPTION:
Unnamed Tributary to Walnut Creek 2R 9.0
END DESCRIPTION:
XS GIS Cut Line= 3
      2330279.04      7034960.00      2330899.92      7034987.54
      2331161.36      7034975.87
#Sta/Elev= 30
  4399.4  690.87  4508.3  689.39  4513.3  688.26  4519.5  688.01  4569.5  687.41
  4589.6  686.71  4649.6  685.65  4659.6  686.18  4679.6  686.05  4699.7  684.72
  4736.3  684.07  4749.7  684.43  4799.8  682.56  4819.8  682.52  4849.8  681.67
  4869.8  681.66  4899.9  680.93  4979.9  680.77  4987.9  679.72  4988.2  679.22
  4991.7  679.22  4991.9  679.72  5022.9  680.09  5030.0  680.90  5076.5  680.55
  5081.5  681.53  5110.1  681.92  5120.1  682.45  5220.2  685.10  5282.6  686.17
#Mann=3,-1,0
  4399.4    0.05       0  4987.9    0.04       0  4991.9    0.05       0
Bank Sta=4987.9,4991.9
Exp/Cntr=0.3,0.1

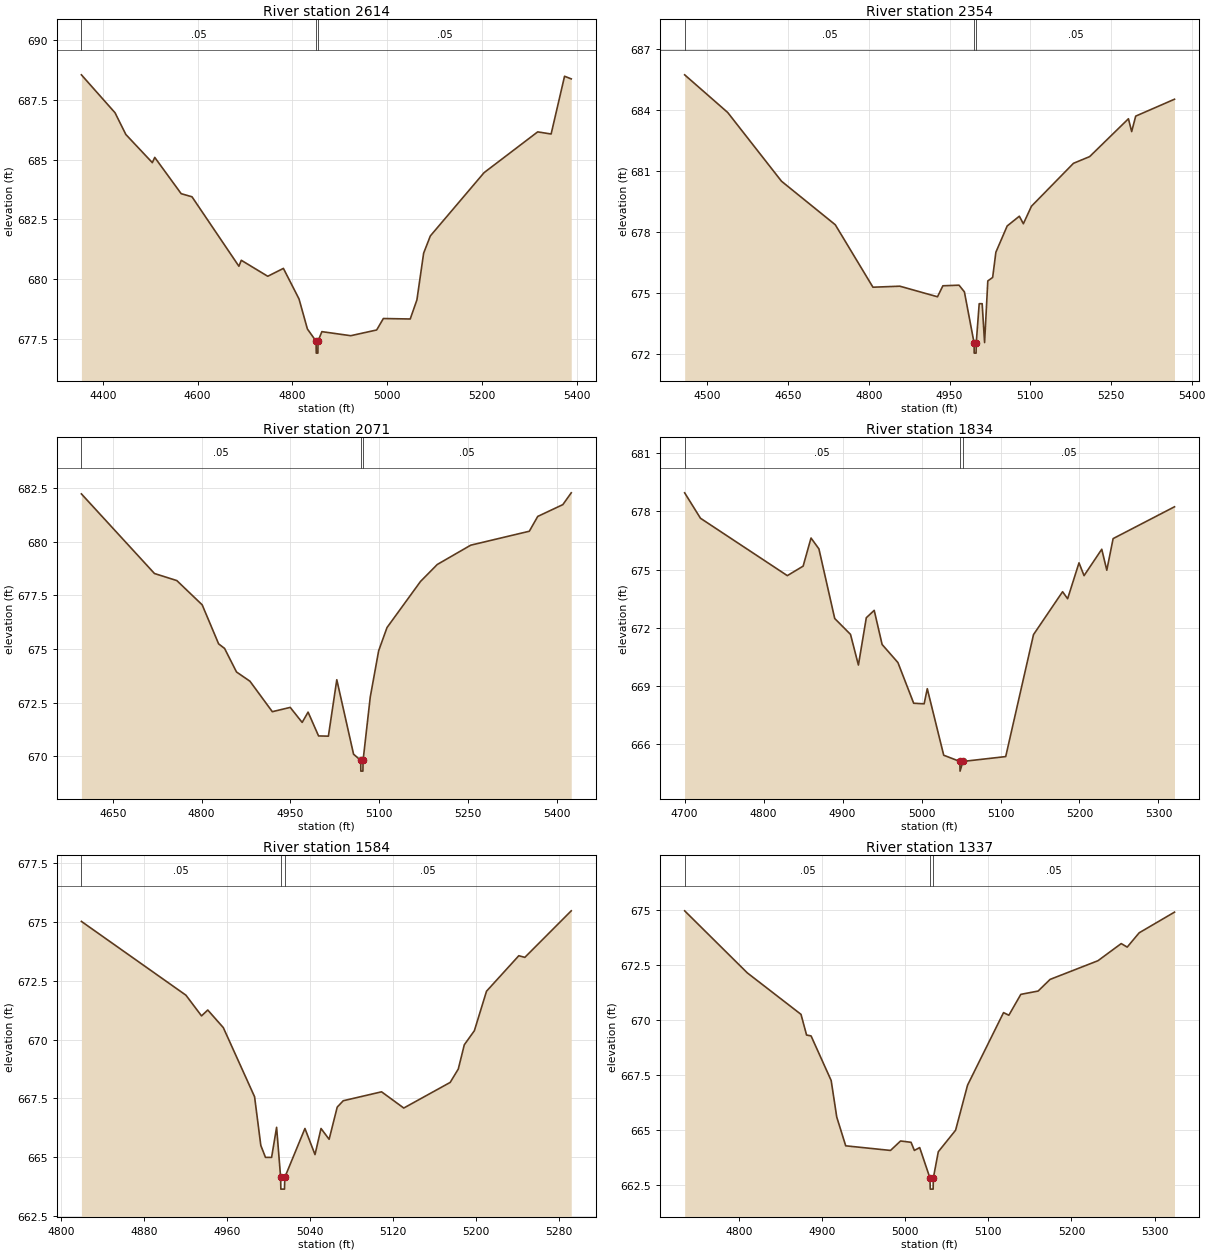
Type RM Length L Ch R = 1,2614,260,260,260
BEGIN DESCRIPTION:
Unnamed Tributary to Walnut Creek 2R 8.0
END DESCRIPTION:
XS GIS Cut Line= 3
      2330379.04      7035359.99      2330979.00      7035260.00
      2331279.00      7034960.00
#Sta/Elev= 30
  4355.1  688.56  4426.0  686.97  4448.8  686.06  4504.6  684.88  4509.7  685.10
  4565.4  683.58  4588.2  683.45  4687.1  680.54  4692.1  680.79  4747.9  680.12
  4780.9  680.45  4813.8  679.17  4831.5  677.91  4849.8  677.40  4850.1  676.90
  4853.6  676.90  4853.8  677.40  4862.0  677.80  4922.8  677.63  4977.5  677.87
  4991.6  678.35  5048.2  678.33  5062.3  679.13  5076.5  681.09  5090.6  681.81
  5203.8  684.46  5316.9  686.17  5345.2  686.08  5373.5  688.50  5387.6  688.39
#Mann=3,-1,0
  4355.1    0.05       0  4849.8    0.04       0  4853.8    0.05       0
Bank Sta=4849.8,4853.8
Exp/Cntr=0.3,0.1

Type RM Length L Ch R = 1,2354,283,283,283
BEGIN DESCRIPTION:
Unnamed Tributary to Walnut Creek 2R 7.0
END DESCRIPTION:
XS GIS Cut Line= 3
      2330529.04      7035460.00      2331079.00      7035460.00
      2331278.99      7035160.01
#Sta/Elev= 30
  4457.6  685.72  4537.6  683.87  4637.6  680.49  4737.6  678.35  4807.6  675.28
  4857.6  675.33  4927.6  674.81  4937.6  675.35  4967.6  675.38  4977.6  675.05
  4995.6  672.54  4995.8  672.04  4999.3  672.04  4999.6  672.54  5005.1  674.47
  5010.6  674.47  5015.1  672.56  5021.1  675.59  5030.1  675.76  5036.1  677.00
  5057.1  678.29  5079.7  678.77  5087.2  678.40  5102.2  679.26  5180.3  681.37
  5210.4  681.70  5282.5  683.56  5288.5  682.93  5296.0  683.69  5368.1  684.52
#Mann=3,-1,0
  4457.6    0.05       0  4995.6    0.04       0  4999.6    0.05       0
Bank Sta=4995.6,4999.6
Exp/Cntr=0.3,0.1

Type RM Length L Ch R = 1,2071,237,237,237
BEGIN DESCRIPTION:
Unnamed Tributary to Walnut Creek 2R 6.0
END DESCRIPTION:
XS GIS Cut Line= 3
      2330679.03      7035660.00      2331079.00      7035710.00
      2331379.04      7035409.96
#Sta/Elev= 30
  4596.9  682.23  4720.3  678.52  4758.1  678.19  4800.9  677.06  4828.7  675.24
  4838.7  675.03  4858.9  673.93  4881.6  673.50  4919.4  672.08  4949.6  672.28
  4969.8  671.58  4979.8  672.06  4997.5  670.95  5014.1  670.94  5028.3  673.57
  5056.6  670.10  5068.7  669.81  5068.9  669.31  5072.4  669.31  5072.7  669.81
  5084.8  672.76  5099.0  674.92  5113.1  676.00  5169.7  678.15  5198.0  678.94
  5254.5  679.84  5353.5  680.49  5367.7  681.18  5410.1  681.73  5424.3  682.28
#Mann=3,-1,0
  4596.9    0.05       0  5068.7    0.04       0  5072.7    0.05       0
Bank Sta=5068.7,5072.7
Exp/Cntr=0.3,0.1

Type RM Length L Ch R = 1,1834,250,250,250
BEGIN DESCRIPTION:
Unnamed Tributary to Walnut Creek 2R 5.0
END DESCRIPTION:
XS GIS Cut Line= 3
      2330778.98      7035910.00      2331079.00      7035910.00
      2331329.02      7035709.99
#Sta/Elev= 30
  4700.1  678.96  4720.1  677.65  4830.1  674.69  4850.1  675.18  4860.1  676.63
  4870.1  676.07  4890.1  672.48  4910.1  671.66  4920.1  670.08  4930.1  672.52
  4940.1  672.90  4950.1  671.14  4970.1  670.21  4990.1  668.11  5003.3  668.08
  5007.3  668.86  5028.1  665.43  5048.5  665.11  5048.8  664.61  5052.5  665.11
  5106.6  665.36  5141.8  671.65  5178.6  673.86  5185.0  673.50  5199.4  675.35
  5205.8  674.69  5228.2  676.05  5234.6  674.97  5242.6  676.60  5320.3  678.24
#Mann=3,-1,0
  4700.1    0.05       0  5048.5    0.04       0  5052.5    0.05       0
Bank Sta=5048.5,5052.5
Exp/Cntr=0.3,0.1

Type RM Length L Ch R = 1,1584,247,247,247
BEGIN DESCRIPTION:
Unnamed Tributary to Walnut Creek 2R 4.0
END DESCRIPTION:
XS GIS Cut Line= 3
      2330879.00      7036010.00      2331029.00      7036110.00
      2331278.98      7035960.01
#Sta/Elev= 30
  4819.8  675.03  4920.5  671.89  4935.5  671.01  4941.5  671.26  4956.5  670.51
  4986.6  667.57  4992.6  665.50  4997.1  664.99  5003.0  664.99  5007.8  666.27
  5011.7  664.14  5011.9  663.64  5015.4  663.64  5015.7  664.14  5035.1  666.22
  5044.8  665.11  5050.6  666.22  5058.4  665.76  5066.2  667.13  5072.0  667.40
  5108.9  667.78  5130.3  667.09  5175.0  668.18  5182.8  668.75  5188.6  669.78
  5198.3  670.38  5210.0  672.06  5241.1  673.57  5246.9  673.50  5291.6  675.48
#Mann=3,-1,0
  4819.8    0.05       0  5011.7    0.04       0  5015.7    0.05       0
Bank Sta=5011.7,5015.7
Exp/Cntr=0.3,0.1

Type RM Length L Ch R = 1,1337,566,566,566
BEGIN DESCRIPTION:
Unnamed Tributary to Walnut Creek 2R 3.0
END DESCRIPTION:
XS GIS Cut Line= 3
      2330829.05      7036409.98      2331079.00      7036310.00
      2331329.03      7036109.98
#Sta/Elev= 30
  4734.6  674.95  4809.9  672.13  4874.6  670.24  4881.3  669.30  4886.7  669.26
  4910.9  667.23  4917.6  665.57  4928.4  664.26  4982.3  664.05  4994.4  664.48
  5007.0  664.42  5011.0  664.05  5017.4  664.18  5029.8  662.79  5030.1  662.29
  5033.6  662.29  5033.8  662.79  5039.8  663.99  5060.6  664.97  5075.0  667.02
  5118.3  670.32  5124.7  670.20  5139.1  671.15  5159.9  671.30  5174.3  671.83
  5231.9  672.68  5259.9  673.46  5267.1  673.30  5281.5  673.95  5324.0  674.89
#Mann=3,-1,0
  4734.6    0.05       0  5029.8    0.04       0  5033.8    0.05       0
Bank Sta=5029.8,5033.8
Exp/Cntr=0.3,0.1

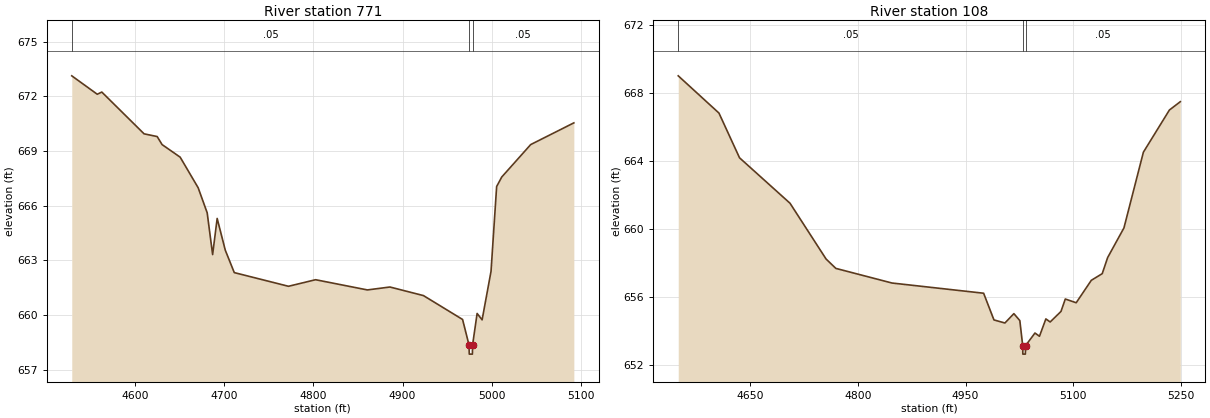
Type RM Length L Ch R = 1,771,663,663,663
BEGIN DESCRIPTION:
Unnamed Tributary to Walnut Creek 2R 2.0
END DESCRIPTION:
XS GIS Cut Line= 3
      2330928.95      7036509.99      2331258.84      7036562.54
      2331460.90      7036454.46
#Sta/Elev= 30
  4528.9  673.12  4557.5  672.11  4562.6  672.23  4610.0  669.94  4624.7  669.79
  4630.2  669.35  4650.5  668.66  4670.7  666.98  4680.8  665.61  4686.9  663.32
  4692.0  665.30  4701.1  663.56  4711.2  662.33  4772.0  661.58  4802.4  661.94
  4860.5  661.38  4885.8  661.54  4923.4  661.07  4967.3  659.76  4974.5  658.36
  4974.8  657.86  4978.3  657.86  4978.5  658.36  4983.6  660.09  4989.2  659.74
  4999.2  662.40  5005.5  667.05  5011.2  667.57  5043.7  669.35  5092.1  670.54
#Mann=3,-1,0
  4528.9    0.05       0  4974.5    0.04       0  4978.5    0.05       0
Bank Sta=4974.5,4978.5
Exp/Cntr=0.3,0.1

Type RM Length L Ch R = 1,108,0,0,0
BEGIN DESCRIPTION:
Unnamed Tributary to Walnut Creek 2R 1.0
END DESCRIPTION:
XS GIS Cut Line= 3
      2331078.99      7036759.99      2331428.91      7037044.41
      2331563.94      7036834.89
#Sta/Elev= 30
  4549.3  669.00  4606.1  666.81  4634.8  664.18  4705.2  661.51  4755.5  658.23
  4769.1  657.68  4847.4  656.82  4975.2  656.22  4989.6  654.65  5004.9  654.47
  5017.4  655.02  5025.7  654.61  5029.7  653.14  5029.9  652.64  5033.4  652.64
  5033.7  653.14  5046.8  653.88  5053.1  653.69  5062.0  654.71  5068.0  654.53
  5083.1  655.15  5089.1  655.88  5104.3  655.66  5125.4  656.98  5140.6  657.37
  5148.2  658.32  5170.9  660.06  5198.0  664.51  5234.3  666.99  5249.5  667.48
#Mann=3,-1,0
  4549.3    0.05       0  5029.7    0.04       0  5033.7    0.05       0
Bank Sta=5029.7,5033.7
Exp/Cntr=0.3,0.1

Chan Stop Cuts=-1