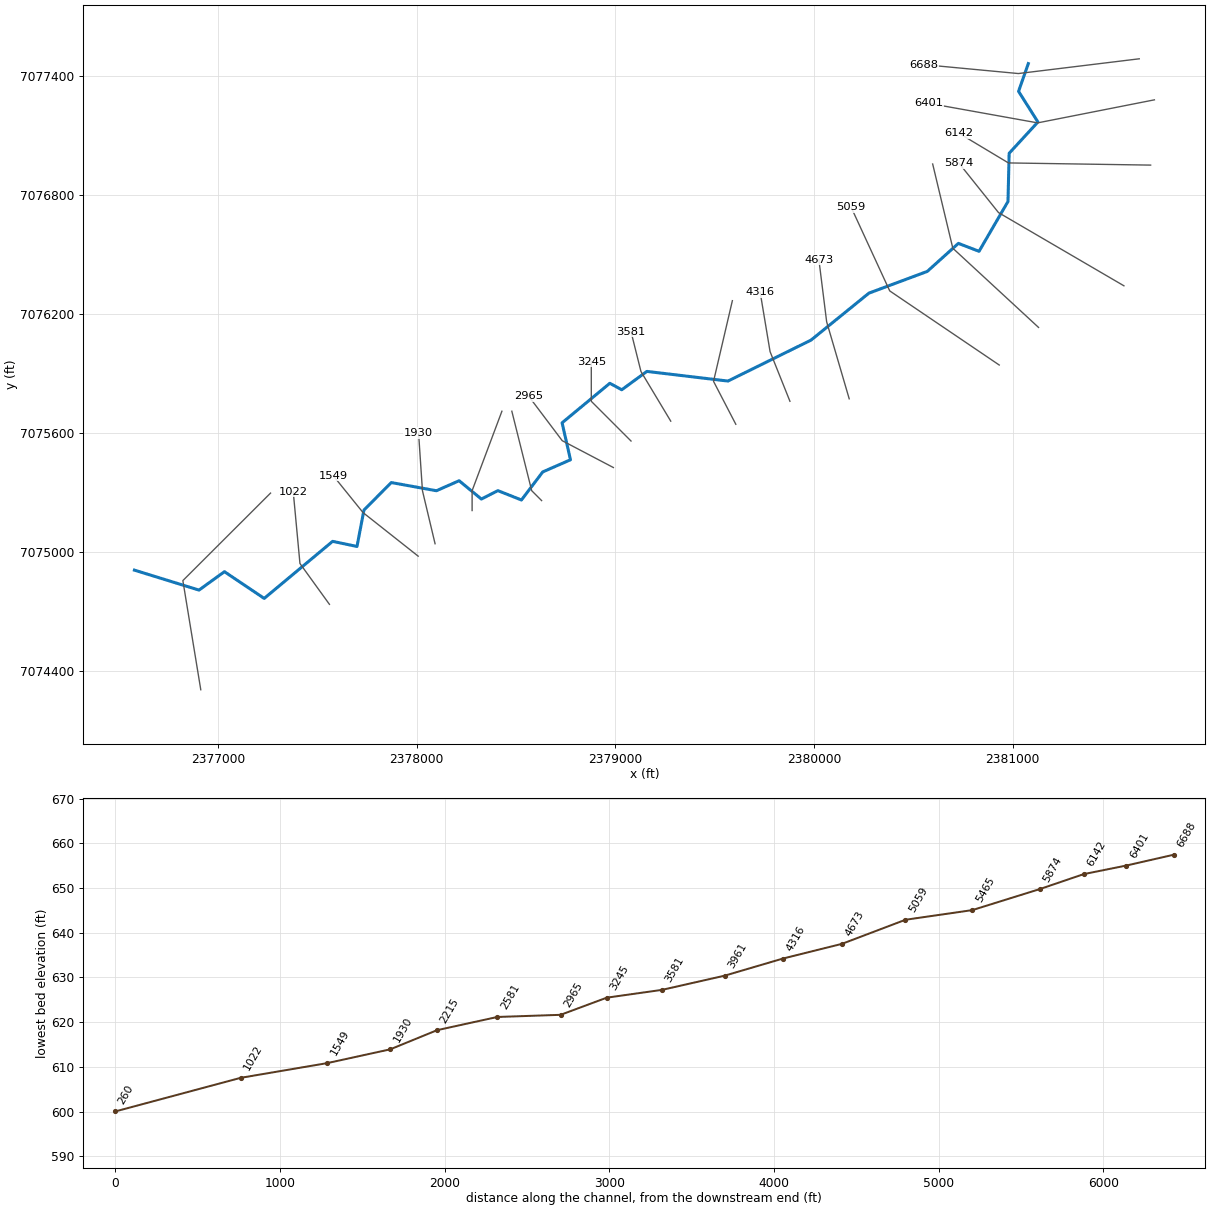
--- WB_1 Tr 2.prj (project) ---

Proj Title=WB_1 Tr 2 Base Level Engineering
Current Plan=p01
Default Exp/Contr=0.3,0.1
English Units
Geom File=g01
Flow File=f01
Plan File=p01
Y Axis Title=Elevation
X Axis Title(PF)=Main Channel Distance
X Axis Title(XS)=Station
BEGIN DESCRIPTION:
WB_1 Tr 2
END DESCRIPTION:
DSS Export Rating Curves= 0
DSS Export Rating Curve Sorted= 0
DSS Export Volume Flow Curves= 0
DXF OffsetX= 0
DXF OffsetY= 0
DXF ScaleX= 1
DXF ScaleY= 10

--- WB_1 Tr 2.p01 (plan) ---

Plan Title=Multiple Run
Short Identifier=Multiple
Geom File=g01
Flow File=f01
Subcritical Flow
K Sum by GR= 0
Std Step Tol= 0.01
Critical Tol= 0.01
Num of Std Step Trials= 20
Max Error Tol= 0.3
Flow Tol Ratio= 0.001
Split Flow NTrial= 30
Split Flow Tol= 0.02
Split Flow Ratio= 0.02
Log Output Level= 0
Friction Slope Method= 1
Unsteady Friction Slope Method= 2
Unsteady Bridges Friction Slope Method= 1
Parabolic Critical Depth
Global Vel Dist=  1 , 1 , 1
Global Log Level= 0
CheckData=True
Encroach Param= -1, 0, 0, 0
BEGIN DESCRIPTION:
Multiple Run
END DESCRIPTION:

--- WB_1 Tr 2.f01 (steady flow) ---

Flow Title=Multiple
Number of Profiles=7
Profile Names=10-year,25-year,50-year,1pct_min,100-year,1pct_plu,500-year
River Rch & RM= WB_1 Tr 2,Reach-1,6688
     455     616     747     452     901    1798    1311
River Rch & RM= WB_1 Tr 2,Reach-1,4673
     697     965    1188     727    1451    2895    2167
Boundary for River Rch & Prof#=WB_1 Tr 2,Reach-1,1
Up Type=0
Dn Type=3
Dn Slope=0.005
Boundary for River Rch & Prof#=WB_1 Tr 2,Reach-1,2
Up Type=0
Dn Type=3
Dn Slope=0.005
Boundary for River Rch & Prof#=WB_1 Tr 2,Reach-1,3
Up Type=0
Dn Type=3
Dn Slope=0.005
Boundary for River Rch & Prof#=WB_1 Tr 2,Reach-1,4
Up Type=0
Dn Type=3
Dn Slope=0.005
Boundary for River Rch & Prof#=WB_1 Tr 2,Reach-1,5
Up Type=0
Dn Type=3
Dn Slope=0.005
Boundary for River Rch & Prof#=WB_1 Tr 2,Reach-1,6
Up Type=0
Dn Type=3
Dn Slope=0.005
Boundary for River Rch & Prof#=WB_1 Tr 2,Reach-1,7
Up Type=0
Dn Type=3
Dn Slope=0.005

--- WB_1 Tr 2.g01 (geometry) ---

Geom Title=Existing Conditions
Program Version=4.10

River Reach=WB_1 Tr 2       ,Reach-1
Reach XY= 30
        2381079.        7077460.      2381029.93      7077320.47
      2381127.42      7077166.05      2380982.54      7077008.54
      2380976.74      7076765.94        2380831.      7076514.99
      2380727.02      7076554.99      2380570.38      7076413.84
      2380276.58      7076304.46      2379985.32      7076068.07
      2379566.99      7075861.85      2379158.82      7075910.43
      2379032.33      7075818.02      2378972.33       7075850.7
      2378731.98      7075651.66      2378774.23      7075465.58
      2378634.61       7075404.4      2378527.38      7075263.13
       2378408.8      7075310.19       2378325.6      7075267.84
      2378213.66      7075360.04      2378099.15      7075309.65
      2377872.26      7075350.87      2377734.47      7075212.45
      2377699.52      7075029.09      2377576.72      7075054.87
      2377232.34       7074767.6      2377032.23      7074902.16
      2376904.04       7074809.5        2376579.        7074910.

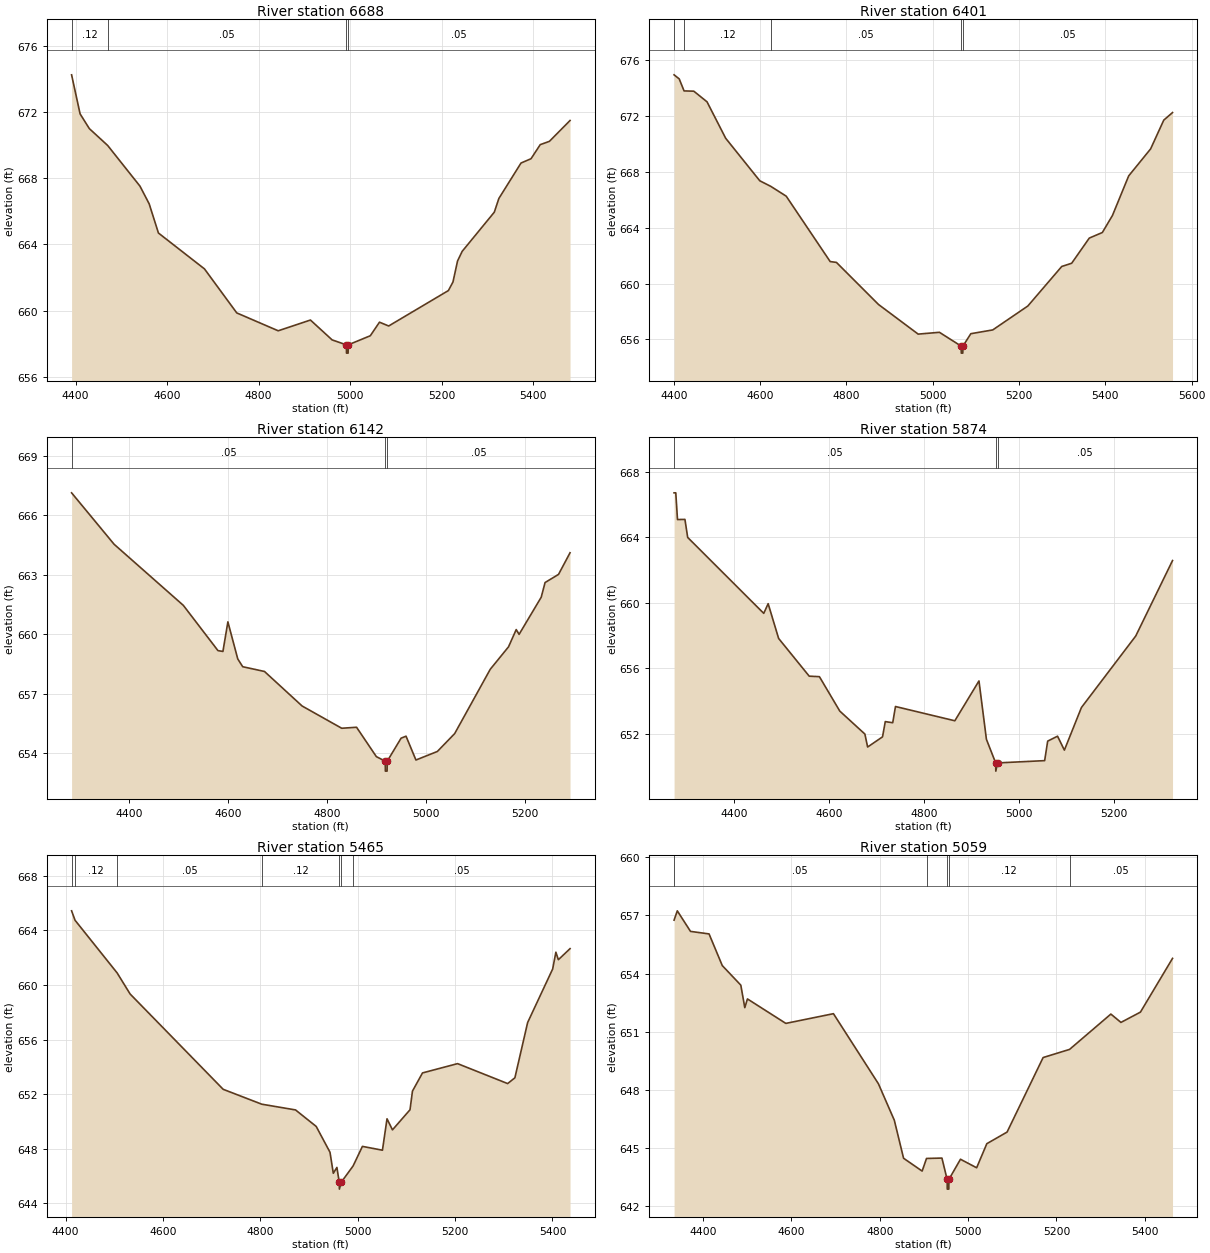
Type RM Length L Ch R = 1 ,6688    ,287,287,287
BEGIN DESCRIPTION:
WB-1 Tr 2 18.0
END DESCRIPTION:
XS GIS Cut Line= 3
       2381637.5      7077484.27        2381029.        7077410.
      2380554.12      7077454.76
#Sta/Elev= 30
  4391.1  674.25  4409.7  671.89  4429.9     671    4470  669.98  4540.7  667.52
  4560.8  666.45    4581  664.69  4681.7  662.52  4752.3  659.86  4842.9  658.78
  4913.4  659.43  4960.8  658.23    4992  657.93  4992.3  657.43  4995.8  657.43
    4996  657.93  5044.3  658.48  5064.4   659.3  5084.5  659.07    5215  661.21
  5225.1  661.73  5235.1     663  5245.2  663.58  5315.5  665.95  5325.5  666.78
  5373.9  668.92  5395.8  669.18  5415.9  670.03    5436  670.23  5481.1  671.49
#Mann= 4 ,-1 , 0
  4391.1     .12       0    4470     .05       0    4992     .04       0
    4996     .05       0
Bank Sta=4992,4996
XS Rating Curve= 0 ,0
Exp/Cntr=0.3,0.1

Type RM Length L Ch R = 1 ,6401    ,259,259,259
BEGIN DESCRIPTION:
WB-1 Tr 2 17.0
END DESCRIPTION:
XS GIS Cut Line= 3
      2381713.86      7077277.67       2381125.9      7077161.65
      2380578.98        7077260.
#Sta/Elev= 30
  4400.7  674.93  4412.6  674.64  4423.8  673.78  4446.4  673.76    4477     673
  4520.3  670.39  4599.3  667.35  4624.8  666.95  4660.5  666.25  4762.4  661.57
  4776.9  661.51  4874.4   658.5  4966.3  656.38  5015.5  656.51    5066  655.52
  5066.2  655.02  5069.7  655.02    5070  655.52  5088.3  656.41  5139.1  656.68
  5220.4  658.39    5299  661.22    5322  661.45  5362.8  663.25  5393.1  663.65
  5416.5  664.87  5454.1   667.7  5504.9  669.63  5535.4  671.69  5555.7  672.23
#Mann= 5 ,-1 , 0
  4400.7     .05       0  4423.8     .12       0  4624.8     .05       0
    5066    .033       0    5070     .05       0
Bank Sta=5066,5070
XS Rating Curve= 0 ,0
Exp/Cntr=0.3,0.1

Type RM Length L Ch R = 1 ,6142    ,268,268,268
BEGIN DESCRIPTION:
WB-1 Tr 2 16.0
END DESCRIPTION:
XS GIS Cut Line= 3
      2381694.91      7076949.06        2380979.        7076960.
      2380729.03      7077109.98
#Sta/Elev= 30
  4283.5  667.12  4369.4  664.53  4509.4  661.45  4579.4  659.17  4589.4  659.13
  4599.4  660.62  4619.4  658.75  4629.4  658.36  4673.4  658.12  4749.5  656.38
  4829.5  655.26  4859.5  655.31  4899.5  653.83  4917.5   653.6  4917.7   653.1
  4921.2   653.1  4921.5   653.6  4949.5  654.76  4959.5  654.86  4979.5  653.66
  5022.8  654.09  5057.8  654.99  5129.7  658.23  5166.6  659.36  5182.2  660.23
    5188  659.99  5232.7  661.86  5240.5   662.6  5267.7  663.01    5291   664.1
#Mann= 3 ,-1 , 0
  4283.5     .05       0  4917.5    .033       0  4921.5     .05       0
Bank Sta=4917.5,4921.5
XS Rating Curve= 0 ,0
Exp/Cntr=0.3,0.1

Type RM Length L Ch R = 1 ,5874    ,409,409,409
BEGIN DESCRIPTION:
WB-1 Tr 2 15.0
END DESCRIPTION:
XS GIS Cut Line= 3
      2381560.33      7076341.41        2380929.        7076710.
      2380729.01      7076959.99
#Sta/Elev= 30
  4273.2  666.71  4276.8  666.71  4280.4  665.08  4296.1  665.09  4301.9  663.99
  4462.3  659.36  4471.6  659.95  4493.7  657.83  4558.2  655.53  4579.7   655.5
  4622.7   653.4  4675.6     652  4681.4  651.21  4712.8  651.83  4718.6  652.76
  4734.3  652.69  4740.1  653.68  4865.3  652.81  4916.2  655.24  4931.9  651.68
  4951.4  650.24  4951.7  649.74  4955.4  650.24  5054.7  650.38  5061.1  651.57
  5081.9  651.87  5096.3  651.02  5132.3  653.62  5246.8  657.98  5324.4  662.58
#Mann= 3 ,-1 , 0
  4273.2     .05       0  4951.4    .033       0  4955.4     .05       0
Bank Sta=4951.4,4955.4
XS Rating Curve= 0 ,0
Exp/Cntr=0.3,0.1

Type RM Length L Ch R = 1 ,5465    ,406,406,406
BEGIN DESCRIPTION:
WB-1 Tr 2 14.0
END DESCRIPTION:
XS GIS Cut Line= 3
      2381130.56      7076131.82      2380698.96      7076530.56
      2380597.56      7076954.71
#Sta/Elev= 30
  4412.4  665.43  4419.5  664.74    4506  660.88  4532.6  659.34  4723.7  652.36
  4802.9  651.27  4872.3  650.85  4914.8  649.64  4943.1  647.75  4949.9  646.21
  4957.3  646.64  4962.1  645.55  4962.4  645.05  4966.1  645.55  4990.6  646.75
  5009.7  648.18  5050.8   647.9  5060.2   650.2  5071.4  649.39  5107.4  650.86
  5112.5  652.23  5133.1  653.56  5205.1  654.24  5307.9  652.78  5322.8   653.2
    5349  657.25  5400.4  661.17    5407   662.4  5412.1  661.85  5436.1  662.66
#Mann= 7 ,-1 , 0
  4412.4     .05       0  4419.5     .12       0    4506     .05       0
  4802.9     .12       0  4962.1    .033       0  4966.1     .12       0
  4990.6     .05       0
Bank Sta=4962.1,4966.1
XS Rating Curve= 0 ,0
Exp/Cntr=0.3,0.1

Type RM Length L Ch R = 1 ,5059    ,386,386,386
BEGIN DESCRIPTION:
WB-1 Tr 2 13.0
END DESCRIPTION:
XS GIS Cut Line= 3
       2380932.6      7075942.61      2380381.32      7076315.77
      2380187.51      7076736.03
#Sta/Elev= 30
  4334.3  656.75  4341.6  657.23  4371.5  656.17  4413.5  656.04  4443.4  654.41
  4485.4   653.4  4494.4  652.24  4500.4  652.69  4587.3  651.43  4695.1  651.93
  4796.9  648.32  4832.9  646.44  4853.9  644.48  4895.9  643.82  4905.8  644.47
  4940.7  644.49  4952.5  643.39  4952.8  642.89  4956.3  642.89  4956.5  643.39
  4982.7  644.43  5019.3  643.99  5042.3  645.23  5088.2  645.83  5169.8  649.67
  5229.7  650.09  5323.2  651.91    5346  651.48  5390.1  652.01  5462.8  654.78
#Mann= 5 ,-1 , 0
  4334.3     .05       0  4905.8     .12       0  4952.5     .07       0
  4956.5     .12       0  5229.7     .05       0
Bank Sta=4952.5,4956.5
XS Rating Curve= 0 ,0
Exp/Cntr=0.3,0.1

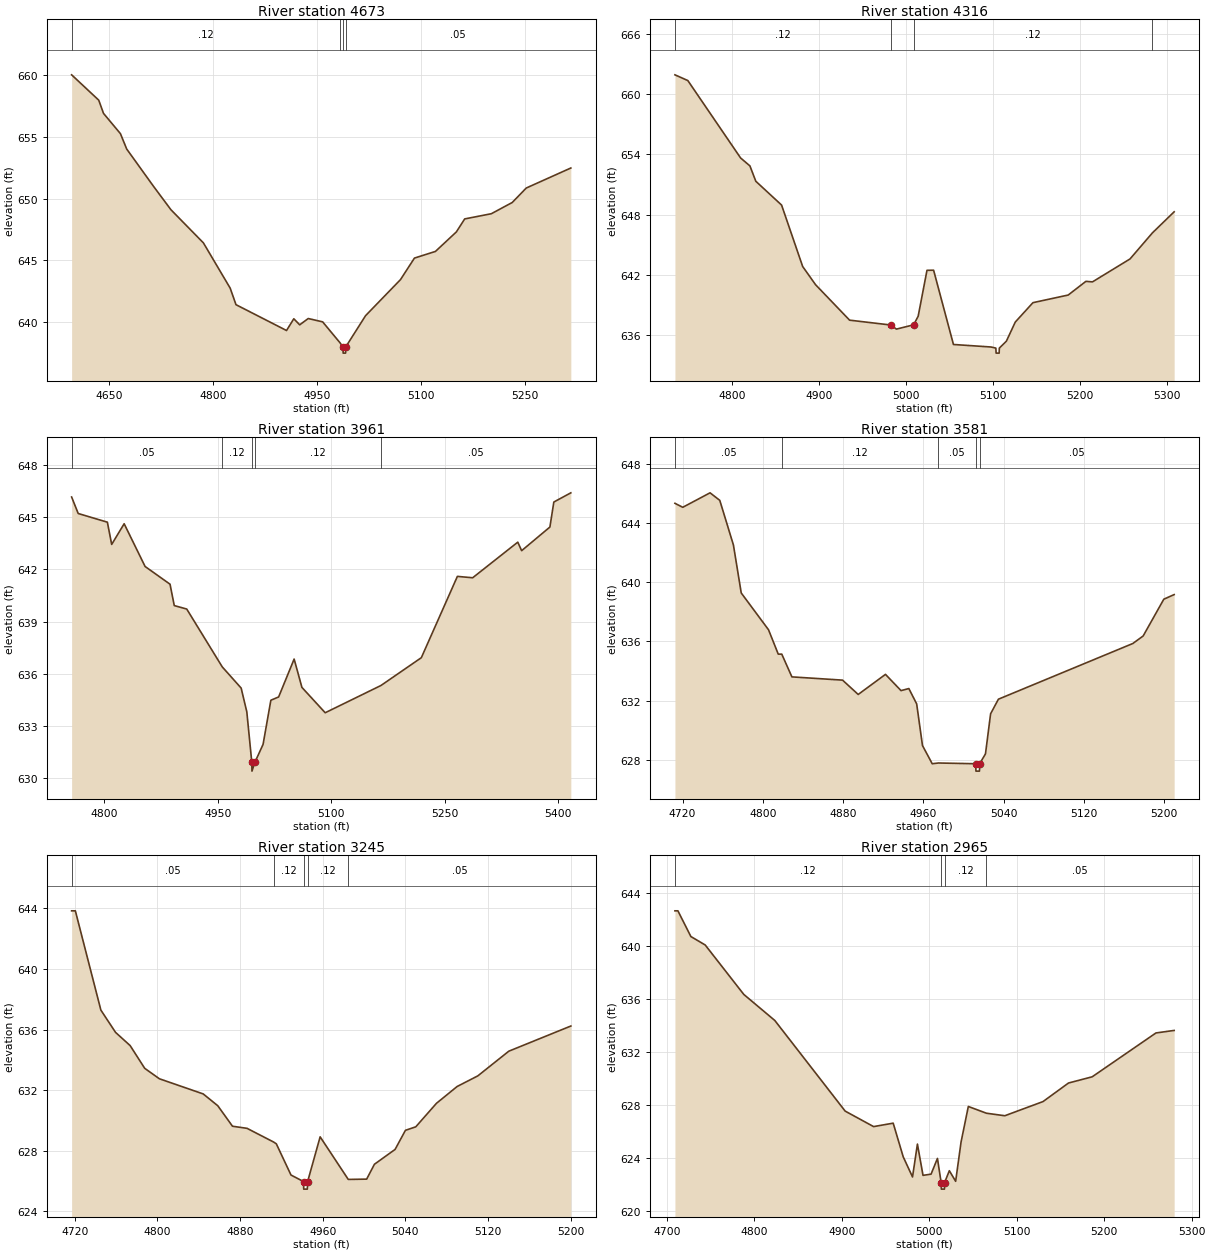
Type RM Length L Ch R = 1 ,4673    ,357,357,357
BEGIN DESCRIPTION:
WB-1 Tr 2 12.0
END DESCRIPTION:
XS GIS Cut Line= 3
      2380177.41      7075772.46      2380063.81      7076160.26
      2380024.63      7076473.83
#Sta/Elev= 30
  4595.9  660.02    4635  657.97  4641.9   656.9  4666.3  655.26  4675.3  654.02
    4714     651  4739.2   649.1    4786  646.42  4824.6  642.76    4833  641.42
  4905.9  639.33  4916.4  640.28  4924.9  639.79  4937.2   640.3    4958  640.03
    4983  638.34  4987.3     638  4987.6   637.5  4991.1   637.5  4991.3     638
  5019.9  640.53  5070.3  643.45  5090.4  645.19  5120.7  645.73  5150.9  647.31
  5162.9  648.36  5201.3  648.78  5231.5  649.69  5251.7  650.86    5316  652.48
#Mann= 4 ,-1 , 0
  4595.9     .12       0    4983     .05       0  4987.3    .033       0
  4991.3     .05       0
Bank Sta=4987.3,4991.3
XS Rating Curve= 0 ,0
Exp/Cntr=0.3,0.1

Type RM Length L Ch R = 1 ,4316    ,355,355,355
BEGIN DESCRIPTION:
WB-1 Tr 2 11.0
END DESCRIPTION:
XS GIS Cut Line= 3
      2379878.99      7075760.03        2379779.        7076010.
      2379728.99      7076310.04
#Sta/Elev= 30
  4734.7  661.92  4749.5  661.35  4810.1  653.65  4820.8  652.86  4827.6  651.33
  4857.2  648.96  4881.4  642.85  4896.2  641.04  4935.3  637.51  4982.4  637.03
  4989.1  636.62 5008.89 637.046  5014.1  637.91  5024.2  642.47  5031.8  642.48
  5054.6  635.09  5097.7  634.84  5103.3  634.73  5103.6  634.23  5107.1  634.23
  5107.3  634.73  5115.4  635.42  5125.6  637.32  5145.9  639.25  5186.4  640.01
  5206.7  641.37  5214.3  641.32  5257.4   643.6  5283.2   646.2  5308.1  648.29
#Mann= 4 ,-1 , 0
  4734.7     .12       0  4982.4     .07       0 5008.89     .12       0
  5283.2     .05       0
Bank Sta=4982.4,5008.89
XS Rating Curve= 0 ,0
Exp/Cntr=0.3,0.1

Type RM Length L Ch R = 1 ,3961    ,380,380,380
BEGIN DESCRIPTION:
WB-1 Tr 2 10.0
END DESCRIPTION:
XS GIS Cut Line= 3
      2379606.49      7075644.28       2379494.4      7075860.34
      2379589.22      7076266.52
#Sta/Elev= 30
  4756.6  646.17  4765.3  645.22  4803.9  644.72  4809.6  643.44  4826.1  644.63
  4853.8  642.17  4886.8  641.15  4892.4  639.92  4908.9  639.72  4955.9  636.39
  4980.9  635.17  4988.4   633.8    4995  630.89  4995.2  630.39    4999  630.89
  5009.9  631.93  5020.2  634.47  5030.5  634.66    5051  636.84  5061.3  635.21
  5092.1  633.75  5165.9  635.32  5219.3  636.92    5267   641.6  5287.2  641.52
  5346.9  643.57    5352  643.08  5389.4  644.44  5394.6  645.88  5417.1  646.41
#Mann= 5 ,-1 , 0
  4756.6     .05       0  4955.9     .12       0    4995     .07       0
    4999     .12       0  5165.9     .05       0
Bank Sta=4995,4999
XS Rating Curve= 0 ,0
Exp/Cntr=0.3,0.1

Type RM Length L Ch R = 1 ,3581    ,336,336,336
BEGIN DESCRIPTION:
WB-1 Tr 2 9.0
END DESCRIPTION:
XS GIS Cut Line= 3
      2379278.99      7075660.01        2379129.        7075910.
        2379079.      7076110.01
#Sta/Elev= 30
  4712.4  645.35  4720.2  645.08  4747.4  646.06  4757.1  645.55  4770.7  642.53
  4778.5  639.28  4805.7  636.79  4815.4  635.14  4818.9  635.14    4829   633.6
  4879.5  633.38  4895.1  632.41  4922.3  633.77  4937.8  632.67  4945.6  632.81
  4953.4  631.77  4959.2  628.95  4968.9  627.72  4975.1  627.77  5012.2  627.72
  5012.5  627.22    5016  627.22  5016.2  627.72    5022  628.39  5027.1   631.1
  5034.9  632.09  5168.9  635.86  5179.2  636.37  5199.8  638.86  5210.1  639.17
#Mann= 5 ,-1 , 0
  4712.4     .05       0  4818.9     .12       0  4975.1     .05       0
  5012.2    .033       0  5016.2     .05       0
Bank Sta=5012.2,5016.2
XS Rating Curve= 0 ,0
Exp/Cntr=0.3,0.1

Type RM Length L Ch R = 1 ,3245    ,280,280,280
BEGIN DESCRIPTION:
WB-1 Tr 2 8.0
END DESCRIPTION:
XS GIS Cut Line= 3
      2379079.02      7075559.98        2378879.        7075760.
        2378879.      7075960.03
#Sta/Elev= 30
  4717.1  643.83  4720.7  643.83  4745.4  637.28  4759.6  635.81  4773.7  634.94
  4787.8  633.44    4802  632.75  4844.4  631.75  4858.5  630.97  4872.7  629.62
  4886.8  629.48  4912.4  628.58  4915.1  628.46  4929.3   626.4  4941.4  625.97
  4941.6  625.47  4945.1  625.47  4945.4  625.97  4957.5  628.92  4984.7  626.11
  5002.5  626.13    5010  627.11    5030  628.09    5040  629.35    5050  629.58
    5070  631.13    5090  632.24    5110  632.94    5140  634.57    5200  636.23
#Mann= 5 ,-1 , 0
  4717.1     .05       0  4912.4     .12       0  4941.4     .04       0
  4945.4     .12       0  4984.7     .05       0
Bank Sta=4941.4,4945.4
XS Rating Curve= 0 ,0
Exp/Cntr=0.3,0.1

Type RM Length L Ch R = 1 ,2965    ,384,384,384
BEGIN DESCRIPTION:
WB-1 Tr 2 7.0
END DESCRIPTION:
XS GIS Cut Line= 3
       2378990.1       7075426.5      2378732.72      7075561.63
      2378564.18      7075785.23
#Sta/Elev= 30
  4709.3  642.65  4712.7  642.65  4727.5  640.71  4743.9  640.07    4788  636.34
  4823.5  634.37  4903.9  627.53  4936.4  626.36  4958.8  626.62  4970.3  624.07
  4980.9  622.56  4986.5  625.04  4992.9  622.68  5002.1  622.77  5009.4  623.96
  5013.6  622.14  5013.9  621.64  5017.4  621.64  5017.6  622.14    5023  623.03
  5030.2  622.23  5036.4   625.2  5044.7  627.88  5065.4  627.37  5086.4  627.18
  5130.1  628.25  5159.2  629.65  5186.3  630.12  5259.2  633.43    5280  633.62
#Mann= 4 ,-1 , 0
  4709.3     .12       0  5013.6     .07       0  5017.6     .12       0
  5065.4     .05       0
Bank Sta=5013.6,5017.6
XS Rating Curve= 0 ,0
Exp/Cntr=0.3,0.1

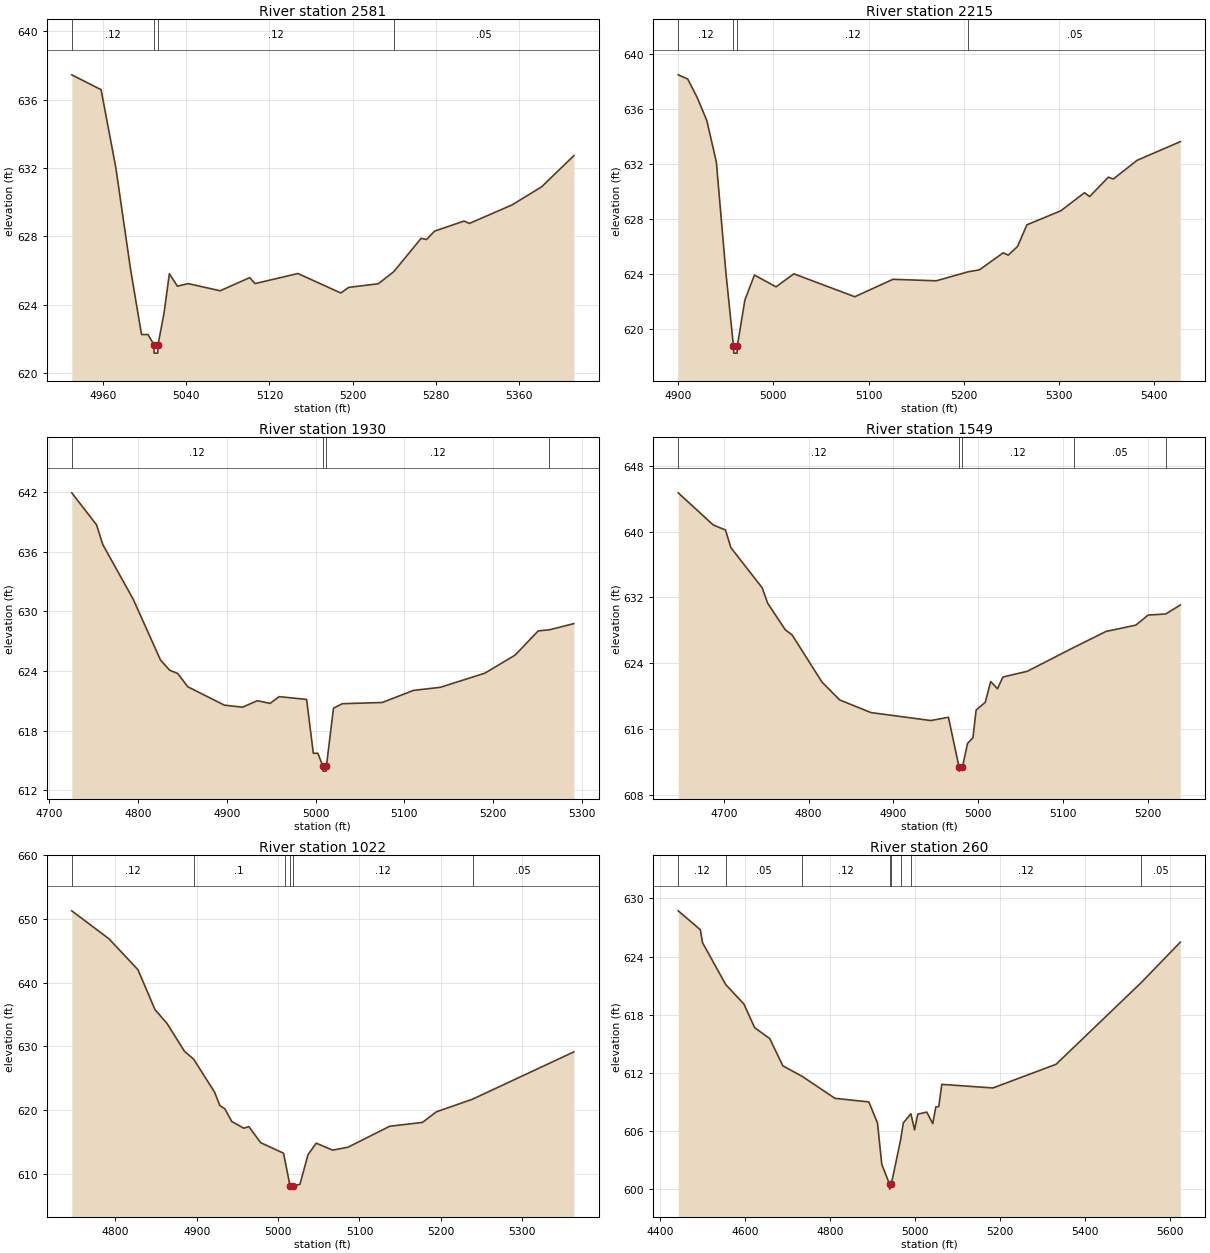
Type RM Length L Ch R = 1 ,2581    ,366,366,366
BEGIN DESCRIPTION:
WB-1 Tr 2 6.0
END DESCRIPTION:
XS GIS Cut Line= 3
      2378628.97      7075260.03        2378579.        7075310.
        2378479.      7075710.02
#Sta/Elev= 30
  4929.8  637.45    4958  636.58  4972.2  632.01  4986.3  626.09  4996.9  622.25
  5003.1  622.25  5008.8  621.66    5009  621.16  5012.5  621.16  5012.8  621.66
  5018.5  623.48  5023.7  625.81  5031.4  625.08  5041.7  625.23  5072.6  624.81
    5101  625.58  5106.1  625.23  5147.4  625.82  5188.6  624.68  5196.3  625.01
  5224.7  625.22  5239.6  625.93  5265.9  627.88  5271.1  627.81  5278.8   628.3
  5307.1  628.89  5312.3  628.75  5353.5  629.84  5381.9   630.9  5412.8  632.72
#Mann= 4 ,-1 , 0
  4929.8     .12       0  5008.8     .07       0  5012.8     .12       0
  5239.6     .05       0
Bank Sta=5008.8,5012.8
XS Rating Curve= 0 ,0
Exp/Cntr=0.3,0.1

Type RM Length L Ch R = 1 ,2215    ,285,285,285
BEGIN DESCRIPTION:
WB-1 Tr 2 5.0
END DESCRIPTION:
XS GIS Cut Line= 3
        2378279.      7075209.99        2378279.        7075310.
        2378429.      7075709.99
#Sta/Elev= 30
  4900.1  638.49  4910.1  638.18  4920.1  636.82  4930.1  635.16  4940.1  632.15
  4950.1  624.11  4958.1  618.71  4958.4  618.21  4961.9  618.21  4962.1  618.71
  4970.1  622.08  4980.1   623.9  5002.8  623.04  5021.5  623.99  5085.5  622.32
  5125.6  623.59    5171  623.48  5204.7  624.14  5216.4  624.28  5241.3  625.52
  5246.6  625.35  5256.4  625.98  5266.2  627.56  5301.8  628.58  5326.7   629.9
  5332.1  629.62  5351.7  631.03    5357   630.9  5381.9  632.26  5427.3  633.62
#Mann= 4 ,-1 , 0
  4900.1     .12       0  4958.1     .07       0  4962.1     .12       0
  5204.7     .05       0
Bank Sta=4958.1,4962.1
XS Rating Curve= 0 ,0
Exp/Cntr=0.3,0.1

Type RM Length L Ch R = 1 ,1930    ,381,381,381
BEGIN DESCRIPTION:
WB-1 Tr 2 4.0
END DESCRIPTION:
XS GIS Cut Line= 3
      2378092.56      7075042.81        2378029.      7075309.85
      2378009.52        7075600.
#Sta/Elev= 30
  4725.5  641.94  4753.4  638.72  4760.5  636.72  4794.6  631.24  4825.4  625.11
  4835.7  624.08  4844.8  623.75  4856.2  622.41  4897.4  620.56  4917.9  620.36
  4934.3  621.01  4948.8  620.74    4959  621.42  4989.9  621.14  4997.5  615.72
  5002.6  615.72  5008.2  614.42  5008.4  613.92  5011.9  613.92  5012.2  614.42
  5020.2  620.26  5030.2  620.71    5075  620.83  5110.4  622.05  5140.5  622.36
  5190.6  623.78  5224.8  625.61  5250.7  628.04  5263.3  628.15  5290.8  628.77
#Mann= 4 ,-1 , 0
  4725.5     .12       0  5008.2     .07       0  5012.2     .12       0
  5263.3     .05       0
Bank Sta=5008.2,5012.2
XS Rating Curve= 0 ,0
Exp/Cntr=0.3,0.1

Type RM Length L Ch R = 1 ,1549    ,527,527,527
BEGIN DESCRIPTION:
WB-1 Tr 2 3.0
END DESCRIPTION:
XS GIS Cut Line= 3
      2378007.49      7074980.31      2377730.06      7075199.56
      2377580.38      7075384.86
#Sta/Elev= 30
  4646.4  644.74  4687.6  640.83  4702.1  640.21  4708.5  638.06  4745.4  633.17
  4751.8   631.3  4772.6  628.06  4780.6  627.44  4815.9  621.69  4836.7  619.52
  4873.6  617.98  4944.1  617.01  4964.9  617.41  4977.4  611.35  4977.6  610.85
  4981.4  611.35  4987.4  614.22  4993.8  614.93  4997.5  618.28  5008.3  619.23
  5014.7  621.76  5022.7  620.88  5029.1  622.31  5057.9  623.01  5113.2  625.94
  5150.6  627.86  5185.8  628.63  5200.2  629.85  5221.1  629.99  5238.2  631.08
#Mann= 5 ,-1 , 0
  4646.4     .12       0  4977.4     .07       0  4981.4     .12       0
  5113.2     .05       0  5221.1     .12       0
Bank Sta=4977.4,4981.4
XS Rating Curve= 0 ,0
Exp/Cntr=0.3,0.1

Type RM Length L Ch R = 1 ,1022    ,762,762,762
BEGIN DESCRIPTION:
WB-1 Tr 2 2.0
END DESCRIPTION:
XS GIS Cut Line= 3
      2377560.77      7074737.73      2377412.33      7074943.35
      2377378.47      7075305.27
#Sta/Elev= 30
  4746.4  651.27  4792.2  646.87  4827.8  642.01  4848.7  635.75  4863.4   633.6
  4884.9  629.21  4896.2  627.97  4921.9  622.79  4928.4  620.69  4934.6  620.16
  4943.1  618.17  4957.8  617.12    4964  617.37  4978.7  614.84  5006.7  613.19
    5008  612.35  5014.7  608.05    5015  607.55  5018.5  607.55  5018.7  608.05
  5026.8   608.3  5036.8  612.97  5046.9  614.77  5066.9  613.68  5085.7  614.12
  5137.2  617.43  5177.4  618.03  5194.6   619.7    5239  621.68  5363.5  629.11
#Mann= 6 ,-1 , 0
  4746.4     .12       0  4896.2      .1       0    5008     .12       0
  5014.7     .07       0  5018.7     .12       0    5239     .05       0
Bank Sta=5014.7,5018.7
XS Rating Curve= 0 ,0
Exp/Cntr=0.3,0.1

Type RM Length L Ch R = 1 ,260     ,0,0,0
BEGIN DESCRIPTION:
WB-1 Tr 2 1.0
END DESCRIPTION:
XS GIS Cut Line= 3
      2376913.09      7074307.73      2376822.89      7074857.27
      2377264.24      7075297.83
#Sta/Elev= 30
  4443.1  628.72  4495.1  626.77  4500.2  625.44  4554.9  621.11  4597.4  619.12
  4622.7  616.68  4658.2  615.55  4689.1  612.74  4735.1  611.64  4811.6  609.39
  4891.3  609.02  4911.6  606.84  4921.7  602.59    4940  600.53  4940.2  600.03
    4944  600.53  4965.7  605.05  4972.4  606.86  4990.1   607.8  4998.8  606.14
  5006.3  607.76  5027.5  607.97  5041.6  606.78  5048.7  608.51  5055.7  608.54
  5062.8  610.83    5183  610.46  5331.5   612.9  5531.9  621.33  5623.6  625.49
#Mann= 8 ,-1 , 0
  4443.1     .12       0  4554.9     .05       0  4735.1     .12       0
    4940     .07       0    4944     .12       0  4965.7      .1       0
  4990.1     .12       0  5531.9     .05       0
Bank Sta=4940,4944
XS Rating Curve= 0 ,0
Exp/Cntr=0.3,0.1

Chan Stop Cuts=-1
Use User Specified Reach Order=0
Composite Channel Slope=5