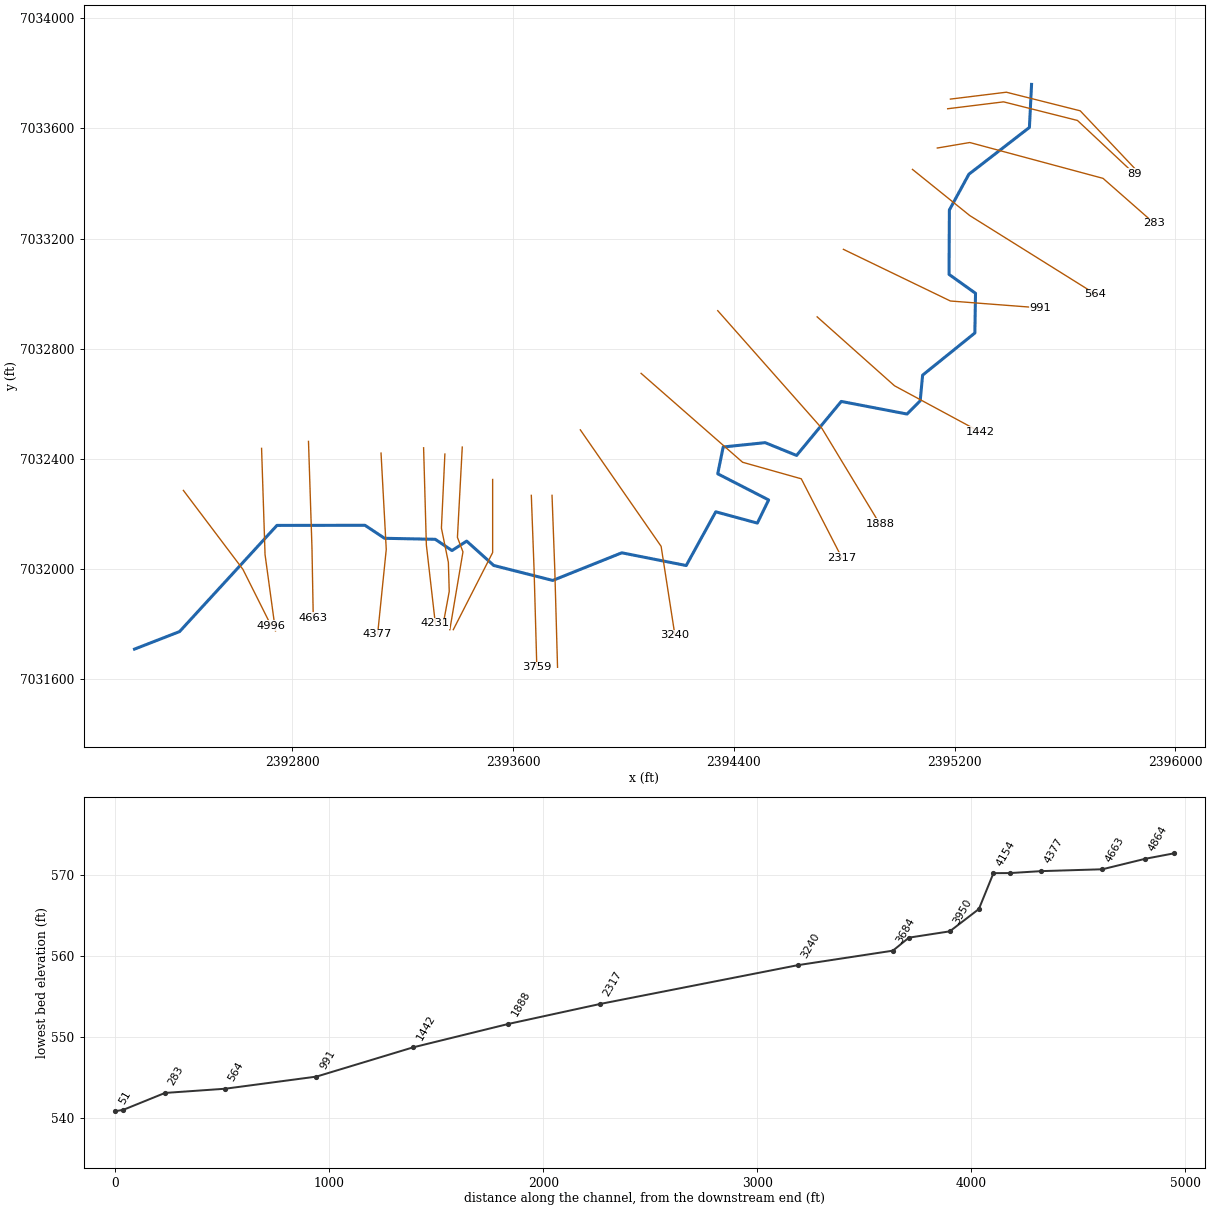
--- West Jones Branch.prj (project) ---

Proj Title=West Jones Branch Base Level Engineering
Current Plan=p01
Default Exp/Contr=0.3,0.1
English Units
Geom File=g01
Flow File=f01
Plan File=p01
Y Axis Title=Elevation
X Axis Title(PF)=Main Channel Distance
X Axis Title(XS)=Station
BEGIN DESCRIPTION:
West Jones Branch
END DESCRIPTION:
DSS Export Rating Curves= 0
DSS Export Rating Curve Sorted= 0
DSS Export Volume Flow Curves= 0
DXF OffsetX= 0
DXF OffsetY= 0
DXF ScaleX= 1
DXF ScaleY= 10

--- West Jones Branch.p01 (plan) ---

Plan Title=Multiple Run
Program Version=4.10
Short Identifier=Multiple
Geom File=g01
Flow File=f01
Subcritical Flow
K Sum by GR= 0
Std Step Tol= 0.01
Critical Tol= 0.01
Num of Std Step Trials= 20
Max Error Tol= 0.3
Flow Tol Ratio= 0.001
Split Flow NTrial= 30
Split Flow Tol= 0.02
Split Flow Ratio= 0.02
Log Output Level= 0
Friction Slope Method= 1
Unsteady Friction Slope Method= 2
Unsteady Bridges Friction Slope Method= 1
Parabolic Critical Depth
Global Vel Dist= 1 , 1 , 1
Global Log Level= 0
CheckData=True
Encroach Param=-1 ,0,0, 0
BEGIN DESCRIPTION:
Multiple Run
END DESCRIPTION:
Computation Interval=1HOUR
Output Interval=1HOUR
Run HTab= 0
Run UNet= 0
Run PostProcess= 0
Run WQNet= 0
UNET Theta= 1
UNET Theta Warmup= 1
UNET ZTol= 0.02
UNET ZSATol= 0.05
UNET MxIter= 20
UNET MaxInSteps= 0
UNET DtIC= 0
UNET DtMin= 0
UNET MaxCRTS= 20
UNET WFStab= 2
UNET SFStab= 1
UNET WFX= 1
UNET SFX= 1
UNET DSS MLevel= 4
UNET DZMax Abort= 100
UNET Convert EG Bridges= 0
UNET Use Existing IB Tables=-1
UNET Froude Reduction=False
UNET Froude Limit= 1
UNET Froude Power= 10
UNET Time Slicing=0,0, 5
UNET Junction Losses=0
Instantaneous Interval=1HOUR
Write IC File= 0
Write IC File at Sim End=0
Echo Input=False
Echo Parameters=False
Echo Output=False
Write Detailed= 0
WQ AD Non Conservative
WQ ULTIMATE=-1
WQ Max Comp Step=1HOUR
WQ Output Interval=15MIN
WQ Output Selected Increments= 0
WQ Output face flow=0
WQ Output face velocity=0
WQ Output face area=0
WQ Output face dispersion=0
WQ Output cell volume=0
WQ Output cell surface area=0
WQ Output cell continuity=0
WQ Output cumulative cell continuity=0
WQ Output face conc=0
WQ Output face dconc_dx=0
WQ Output face courant=0
WQ Output face peclet=0
WQ Output face adv mass=0
WQ Output face disp mass=0
WQ Output cell mass=0
WQ Output cell source sink temp=0
WQ Output cell source sink nsm=0
WQ Output MaxMinRange=-1
WQ Daily Max Min Mean=-1
WQ Daily Range=0
WQ Daily Time=0
WQ Create Restart=0
WQ Fixed Restart=0
WQ System Summary=0
WQ Use Fixed Temperature=0
Sorting and Armoring Iterations= 10
XS Update Threshold= 0.02
Hydraulics Update Threshold= 0.02
Energy Slope Method= 1
Volume Change Method= 0
XS Weighting Method= 0
Number of US Weighted Cross Sections= 1
Number of DS Weighted Cross Sections= 1
Upstream XS Weight=0.25
Main XS Weight=0.5
Downstream XS Weight=0.25
Number of DS XS's Weighted with US Boundary= 1
Upstream Boundary Weight= 1
Weight of XSs Associated with US Boundary= 0
Number of US XS's Weighted with DS Boundary= 1
Downstream Boundary Weight= 0.5
Weight of XSs Associated with DS Boundary= 0.5
Sediment Output Level= 4
Mass or Volume Output= 0
Output Increment Type= 1
Profile and TS Output Increment= 10
XS Output Flag= 0
XS Output Increment= 10
Disregard all LS=0
Disregard all Conn=0
Disregard all Breaches=0
Disregard all Pumps=0

--- West Jones Branch.f01 (steady flow) ---

Flow Title=Multiple
Number of Profiles=7
Profile Names=10-year,25-year,50-year,1pct_min,100-year,1pct_plu,500-year
River Rch & RM= West Jones Branc,Reach-1,4996
     748    1038    1281     784    1564    3121    2331
River Rch & RM= West Jones Branc,Reach-1,3759
    1313    1879    2364    1473    2939    5863    4542
Boundary for River Rch & Prof#=West Jones Branc,Reach-1,1
Up Type=0
Dn Type=3
Dn Slope=0.005
Boundary for River Rch & Prof#=West Jones Branc,Reach-1,2
Up Type=0
Dn Type=3
Dn Slope=0.005
Boundary for River Rch & Prof#=West Jones Branc,Reach-1,3
Up Type=0
Dn Type=3
Dn Slope=0.005
Boundary for River Rch & Prof#=West Jones Branc,Reach-1,4
Up Type=0
Dn Type=3
Dn Slope=0.005
Boundary for River Rch & Prof#=West Jones Branc,Reach-1,5
Up Type=0
Dn Type=3
Dn Slope=0.005
Boundary for River Rch & Prof#=West Jones Branc,Reach-1,6
Up Type=0
Dn Type=3
Dn Slope=0.005
Boundary for River Rch & Prof#=West Jones Branc,Reach-1,7
Up Type=0
Dn Type=3
Dn Slope=0.005

--- West Jones Branch.g01 (geometry) ---

Geom Title=Existing Conditions
Program Version=4.10

River Reach=West Jones Branc,Reach-1
Reach XY= 30
        2392229.        7031710.      2392392.22      7031773.61
      2392744.94      7032159.08      2393063.78      7032159.48
      2393134.94      7032112.26      2393318.57      7032108.62
       2393379.1      7032067.81      2393432.33      7032101.99
      2393530.48      7032013.61      2393744.29      7031959.29
      2393994.27      7032059.62      2394227.75      7032013.36
      2394334.83      7032208.46      2394485.45      7032167.41
      2394526.43      7032251.48      2394341.96      7032346.45
      2394361.68      7032443.73      2394513.78      7032459.48
      2394627.58      7032413.04      2394789.47      7032609.07
      2395027.75      7032563.36      2395075.46      7032611.32
      2395084.26      7032704.52      2395273.55      7032857.56
      2395275.91      7033001.68      2395180.01      7033070.29
      2395181.24      7033304.07      2395251.85      7033433.84
      2395471.21       7033603.8        2395479.        7033760.

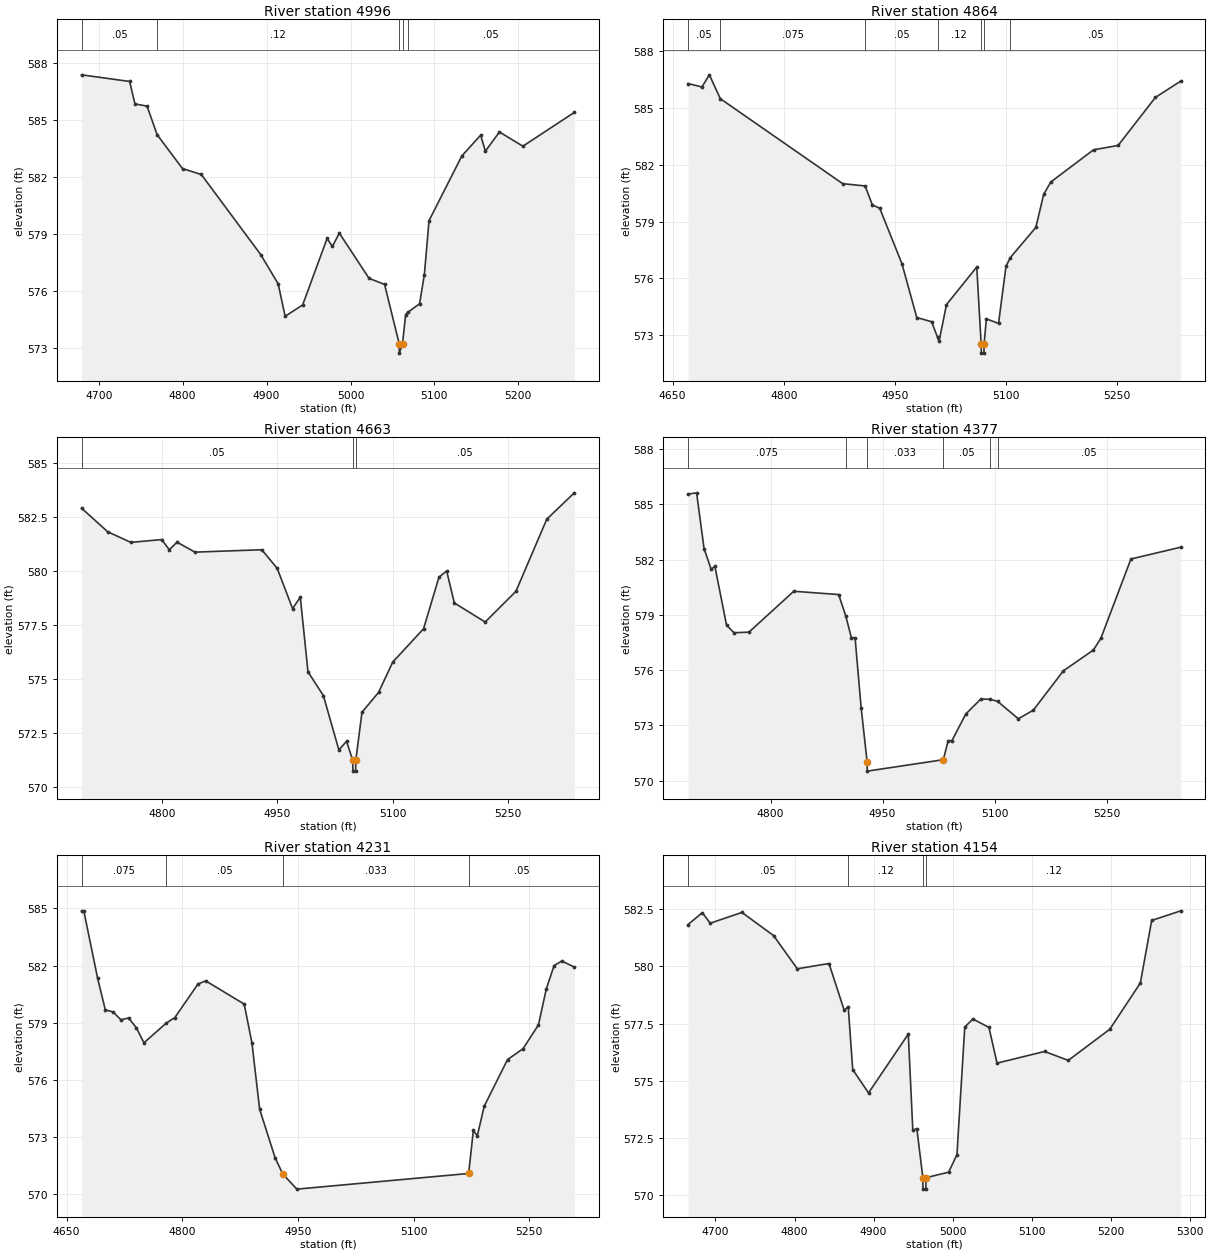
Type RM Length L Ch R = 1 ,4996    ,132,132,132
BEGIN DESCRIPTION:
West Jones Branch 11.0
END DESCRIPTION:
XS GIS Cut Line= 3
      2392405.99      7032286.09      2392621.59      7031999.68
      2392723.87      7031795.11
#Sta/Elev= 30
  4679.5  587.37  4736.8  587.02  4743.1  585.84  4757.6  585.72  4769.5  584.22
  4799.8  582.43  4822.2  582.12    4893   577.9  4913.8  576.36  4922.1  574.65
    4943  575.25  4972.1  578.75  4978.4  578.33  4986.7  579.03  5022.1  576.65
  5040.6  576.33    5058  573.21  5058.2  572.71    5062  573.21  5065.7  574.74
  5068.6  574.87  5082.3  575.31    5088  576.84  5093.6  579.69  5132.7   583.1
  5155.1  584.19  5160.7  583.35  5177.5  584.36  5205.4  583.61  5266.7  585.39
#Mann= 5 ,-1 , 0
  4679.5     .05       0  4769.5     .12       0    5058     .07       0
    5062     .12       0  5068.6     .05       0
Bank Sta=5058,5062
XS Rating Curve= 0 ,0
Exp/Cntr=0.3,0.1

Type RM Length L Ch R = 1 ,4864    ,201,201,201
BEGIN DESCRIPTION:
West Jones Branch 10.2
END DESCRIPTION:
XS GIS Cut Line= 3
      2392689.27      7032438.77      2392701.86      7032053.19
      2392739.64      7031776.14
#Sta/Elev= 30
  4670.8  586.29  4689.6  586.11  4699.6  586.75  4714.4  585.49  4879.7     581
    4910  580.88  4919.7  579.88  4929.7   579.7  4959.7  576.77  4979.7  573.93
  4999.7  573.71  5007.8  572.88  5009.8  572.67  5019.8  574.61  5060.7   576.6
  5066.6  572.55  5066.9  572.05  5070.4  572.05  5070.6  572.55  5073.7  573.86
  5090.1  573.62  5100.2  576.63  5105.9  577.09  5140.5  578.69  5151.1  580.44
  5160.7  581.09  5218.4  582.79  5251.6  583.02    5302  585.56  5336.2  586.42
#Mann= 7 ,-1 , 0
  4670.8     .05       0  4714.4    .075       0    4910     .05       0
  5007.8     .12       0  5066.6    .033       0  5070.6     .12       0
  5105.9     .05       0
Bank Sta=5066.6,5070.6
XS Rating Curve= 0 ,0
Exp/Cntr=0.3,0.1

Type RM Length L Ch R = 1 ,4663    ,286,286,286
BEGIN DESCRIPTION:
West Jones Branch 10.0
END DESCRIPTION:
XS GIS Cut Line= 3
      2392859.25      7032463.98      2392871.84      7032078.37
      2392876.55      7031824.22
#Sta/Elev= 30
  4695.9   582.9  4729.9  581.81  4759.9  581.32  4799.9  581.45  4809.9  580.98
  4819.9  581.33  4843.2  580.87    4930  580.98    4950  580.12    4970  578.26
    4980  578.79    4990  575.34    5010  574.24  5030.1  571.73  5040.1  572.13
  5048.1  571.25  5048.3  570.75  5051.8  570.75  5052.1  571.25  5060.1  573.47
  5081.7  574.39  5100.1  575.79  5140.1  577.33  5160.1  579.71  5170.1     580
  5180.1  578.52  5220.1  577.64  5260.1  579.06  5300.1  582.39  5335.9  583.61
#Mann= 3 ,-1 , 0
  4695.9     .05       0  5048.1     .05       0  5052.1     .05       0
Bank Sta=5048.1,5052.1
XS Rating Curve= 0 ,0
Exp/Cntr=0.3,0.1

Type RM Length L Ch R = 1 ,4377    ,146,146,146
BEGIN DESCRIPTION:
West Jones Branch 9.0
END DESCRIPTION:
XS GIS Cut Line= 3
      2393122.09      7032421.52      2393140.98      7032072.07
      2393109.65      7031763.51
#Sta/Elev= 30
  4689.4  585.55  4700.9  585.62  4710.9  582.59  4720.4  581.47  4725.4  581.63
    4741  578.44    4751  578.03    4771  578.06  4831.1  580.28  4891.2   580.1
  4900.7  578.94  4908.2  577.77  4913.2  577.75  4921.3  573.97  4929.3  571.02
  4929.5  570.52  5031.4  571.14  5037.9  572.17  5042.9  572.17  5061.5  573.62
  5081.6  574.43  5093.8  574.42    5104  574.31  5131.9  573.36    5152  573.83
  5192.2  575.96  5232.4  577.09  5242.5  577.73  5282.7  582.03  5349.5  582.67
#Mann= 6 ,-1 , 0
  4689.4    .075       0  4900.7     .05       0  4929.3    .033       0
  5031.4     .05       0  5093.8     .12       0    5104     .05       0
Bank Sta=4929.3,5031.4
XS Rating Curve= 0 ,0
Exp/Cntr=0.3,0.1

Type RM Length L Ch R = 1 ,4231    ,77,77,77
BEGIN DESCRIPTION:
West Jones Branch 8.3
END DESCRIPTION:
XS GIS Cut Line= 3
       2393276.3      7032440.84       2393286.3      7032088.09
      2393318.71      7031803.92
#Sta/Elev= 30
  4669.4  584.87  4672.3  584.87  4690.2  581.34  4700.2  579.68  4710.3  579.57
  4720.3  579.16  4730.3  579.25  4740.3  578.75  4750.3  577.95  4779.4  578.99
  4790.3  579.27  4820.3  581.03  4830.3   581.2  4880.3  579.98  4890.3  577.95
  4900.3  574.47  4920.3  571.93  4930.3  571.07  4948.6  570.28  5171.3   571.1
  5177.4  573.36  5182.5  573.07  5191.5  574.63  5221.7  577.07  5241.8  577.64
  5261.8  578.89    5272  580.78  5282.1     582  5292.1  582.24  5308.3  581.92
#Mann= 4 ,-1 , 0
  4669.4    .075       0  4779.4     .05       0  4930.3    .033       0
  5171.3     .05       0
Bank Sta=4930.3,5171.3
XS Rating Curve= 0 ,0
Exp/Cntr=0.3,0.1

Type RM Length L Ch R = 1 ,4154    ,68,68,68
BEGIN DESCRIPTION:
West Jones Branch 8.1
END DESCRIPTION:
XS GIS Cut Line= 5
      2393353.43      7032418.09      2393340.86       7032149.2
      2393366.05      7032024.86      2393369.19      7031919.41
      2393347.16      7031799.77
#Sta/Elev= 30
  4665.3  581.82  4683.4  582.34  4693.4  581.88  4733.5  582.35  4773.5  581.34
  4803.5  579.89  4843.6  580.12  4862.9  578.07  4867.9  578.24  4873.6  575.49
  4893.6  574.47  4943.9  577.04  4949.6  572.84  4954.7  572.91  4962.3  570.77
  4962.5  570.27    4966  570.27  4966.3  570.77  4994.9  571.01  5005.4  571.77
  5015.3  577.34  5025.5   577.7  5045.9  577.33  5056.1  575.77  5116.2  576.28
  5146.2  575.89  5198.7  577.25  5237.4  579.27  5251.7     582  5288.5  582.42
#Mann= 4 ,-1 , 0
  4665.3     .05       0  4867.9     .12       0  4962.3    .033       0
  4966.3     .12       0
Bank Sta=4962.3,4966.3
XS Rating Curve= 0 ,0
Exp/Cntr=0.3,0.1

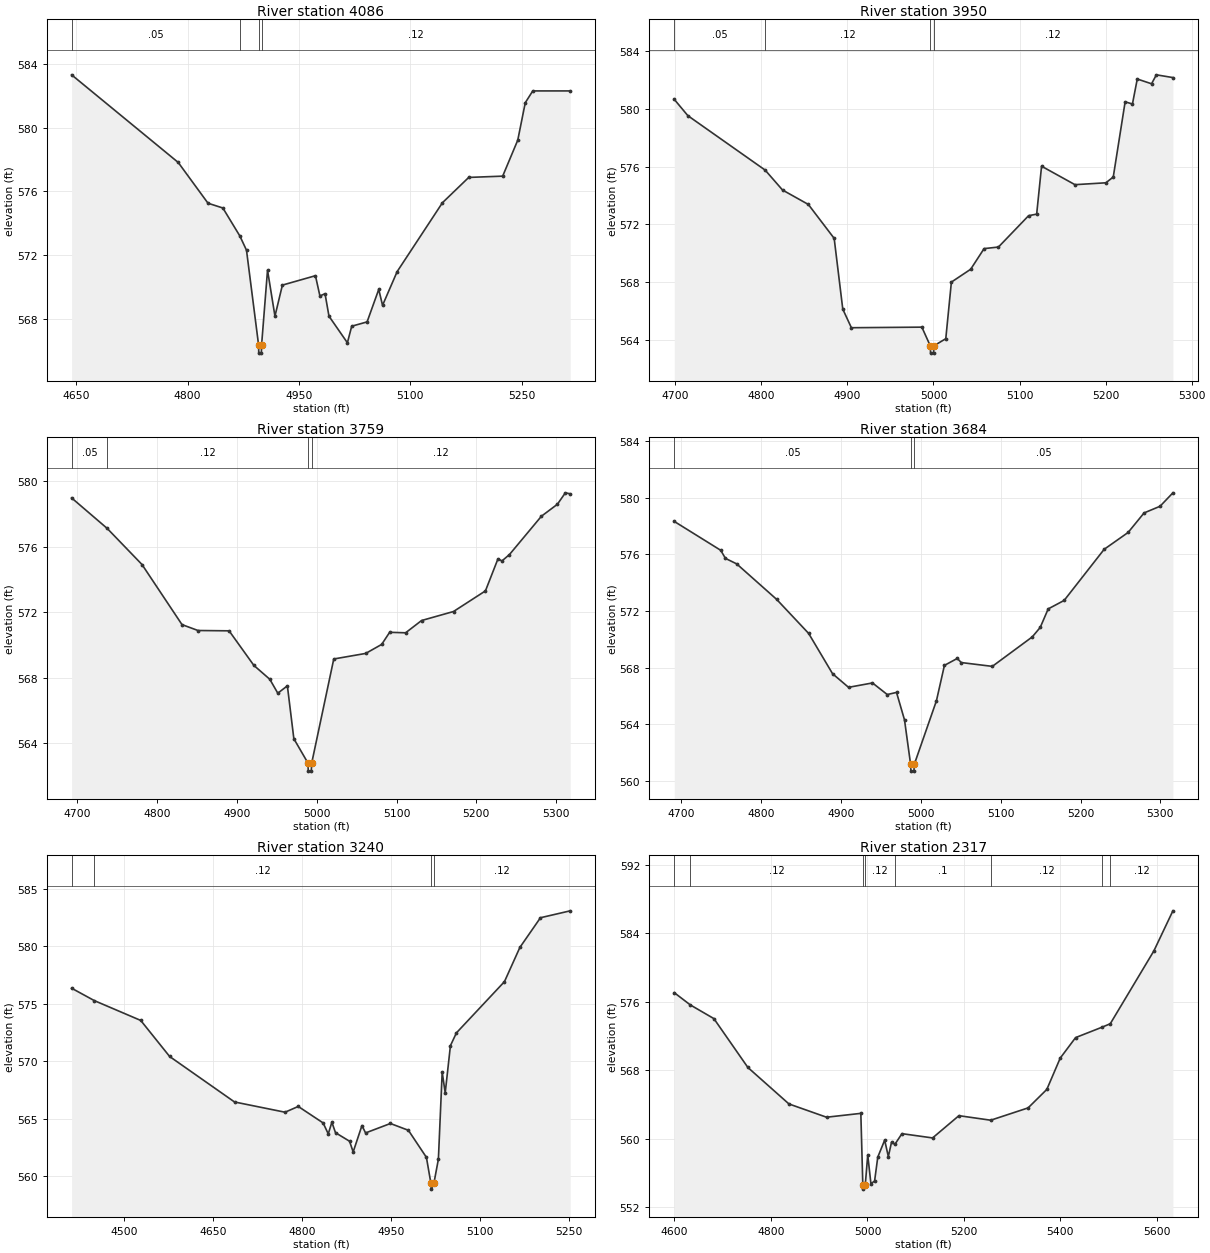
Type RM Length L Ch R = 1 ,4086    ,136,136,136
BEGIN DESCRIPTION:
West Jones Branch 8.0
END DESCRIPTION:
XS GIS Cut Line= 4
      2393416.39      7032443.33      2393398.88       7032115.6
      2393418.89      7032063.07      2393371.35      7031780.35
#Sta/Elev= 30
    4644  583.31  4787.5  577.81  4827.6  575.25  4847.6  574.95  4870.5  573.19
  4879.4   572.3  4895.7  566.34  4895.9  565.84  4899.4  565.84  4899.7  566.34
  4907.7  571.05  4917.7  568.16  4927.7  570.11  4972.2   570.7  4978.2  569.43
  4985.1  569.57  4990.4  568.16  5015.2  566.49    5021  567.53  5041.7   567.8
  5057.4  569.84  5062.5  568.84  5082.2  570.96  5143.1  575.28  5178.5  576.87
  5224.2  576.95  5244.5  579.21  5254.6  581.56  5264.7   582.3  5315.1   582.3
#Mann= 4 ,-1 , 0
    4644     .05       0  4870.5     .12       0  4895.7     .07       0
  4899.7     .12       0
Bank Sta=4895.7,4899.7
XS Rating Curve= 0 ,0
Exp/Cntr=0.3,0.1

Type RM Length L Ch R = 1 ,3950    ,191,191,191
BEGIN DESCRIPTION:
West Jones Branch 7.6
END DESCRIPTION:
XS GIS Cut Line= 3
      2393526.46      7032325.78      2393526.46      7032060.57
      2393383.95      7031780.56
#Sta/Elev= 30
  4698.8  580.66  4714.6  579.53  4804.4  575.76  4824.6  574.38  4854.6  573.38
  4884.6  571.03  4894.6  566.13  4904.6  564.84  4986.5  564.88  4996.3  563.58
  4996.6  563.08  5000.1  563.08  5000.3  563.58  5014.3  564.08  5020.8     568
  5043.2  568.89  5058.8  570.32  5075.5  570.43  5110.5   572.6  5119.9  572.71
  5125.6  576.03  5164.4  574.75  5200.3  574.88  5208.9  575.28  5222.7  580.49
  5231.2  580.34  5236.8  582.07  5253.4  581.74    5259  582.36  5278.2  582.17
#Mann= 4 ,-1 , 0
  4698.8     .05       0  4804.4     .12       0  4996.3     .07       0
  5000.3     .12       0
Bank Sta=4996.3,5000.3
XS Rating Curve= 0 ,0
Exp/Cntr=0.3,0.1

Type RM Length L Ch R = 1 ,3759    ,75,75,75
BEGIN DESCRIPTION:
West Jones Branch 7.3
END DESCRIPTION:
XS GIS Cut Line= 3
      2393666.55      7032268.17      2393676.55      7031998.03
      2393686.53      7031643.89
#Sta/Elev= 30
    4693  578.99  4737.5  577.13  4781.2  574.92  4831.3  571.25  4851.3  570.89
  4890.3  570.87  4921.3  568.76  4941.3  567.91  4951.3  567.06  4963.3  567.51
  4971.4  564.28    4989   562.8  4989.5   562.3  4993.2   562.3  4993.8   562.8
  5021.4  569.15  5061.4  569.49  5081.4  570.04  5091.4  570.78  5111.4  570.75
  5131.4   571.5  5171.4  572.05  5211.4  573.31  5227.1  575.27  5232.1  575.14
  5241.5  575.53  5281.5  577.87  5301.5   578.6  5311.5   579.3  5317.6  579.24
#Mann= 4 ,-1 , 0
    4693     .05       0  4737.5     .12       0    4989     .07       0
  4993.8     .12       0
Bank Sta=4989,4993.8
XS Rating Curve= 0 ,0
Exp/Cntr=0.3,0.1

Type RM Length L Ch R = 1 ,3684    ,444,444,444
BEGIN DESCRIPTION:
West Jones Branch 7.0
END DESCRIPTION:
XS GIS Cut Line= 3
       2393741.6      7032268.18       2393751.6      7031998.03
      2393761.58       7031643.9
#Sta/Elev= 30
  4691.1  578.33  4749.3  576.29  4755.2  575.72  4769.3  575.33  4819.4  572.82
  4859.4  570.42  4889.4  567.57  4909.4  566.61  4939.4  566.92  4957.9   566.1
  4969.5  566.25  4979.5  564.31  4987.1  561.19  4987.6  560.69  4991.3  560.69
  4991.9  561.19  5019.5  565.66  5029.5  568.16  5045.6  568.65  5050.6  568.36
  5089.5  568.09  5139.5  570.17  5149.5  570.84  5159.5  572.15  5179.5  572.75
  5229.6  576.36  5259.6  577.55  5279.6  578.93  5299.6   579.4  5315.7  580.35
#Mann= 3 ,-1 , 0
  4691.1     .05       0  4987.1    .033       0  4991.9     .05       0
Bank Sta=4987.1,4991.9
XS Rating Curve= 0 ,0
Exp/Cntr=0.3,0.1

Type RM Length L Ch R = 1 ,3240    ,923,923,923
BEGIN DESCRIPTION:
West Jones Branch 6.0
END DESCRIPTION:
XS GIS Cut Line= 3
      2393844.14      7032505.88      2394136.85      7032083.08
      2394186.88      7031760.37
#Sta/Elev= 30
  4411.8  576.35  4450.2  575.27  4528.4  573.55  4577.1  570.42  4686.5  566.47
  4771.7  565.58    4794  566.08  4835.9  564.65  4844.6   563.7  4850.7  564.71
  4856.8   563.8  4880.5  563.06  4886.6  562.13  4901.4  564.42  4907.5  563.78
  4949.4   564.6  4979.7  564.01  5010.1  561.66  5017.7   559.4  5018.3   558.9
  5022.7   559.4  5030.3   561.5  5036.7  569.06  5041.8  567.26  5050.6  571.36
  5060.7  572.47  5141.7  576.92  5167.7  579.89  5202.4  582.47  5252.6  583.07
#Mann= 4 ,-1 , 0
  4411.8     .05       0  4450.2     .12       0  5017.7     .07       0
  5022.7     .12       0
Bank Sta=5017.7,5022.7
XS Rating Curve= 0 ,0
Exp/Cntr=0.3,0.1

Type RM Length L Ch R = 1 ,2317    ,429,429,429
BEGIN DESCRIPTION:
West Jones Branch 5.0
END DESCRIPTION:
XS GIS Cut Line= 4
      2394064.33      7032710.95      2394432.04      7032388.28
      2394644.67      7032328.24      2394792.27      7032040.55
#Sta/Elev= 30
  4599.6  577.06  4632.8  575.63  4681.7  574.03  4752.2  568.32  4837.3  564.06
  4915.2  562.51  4986.3  562.96  4990.4  554.61  4991.1  554.11  4995.5  554.61
  5000.6   558.1  5007.2  554.75  5014.8  555.05  5021.4  557.85  5035.7  559.83
  5043.3  557.91  5049.9  559.59  5056.9  559.35  5071.5  560.59    5135  560.09
  5189.6  562.69  5255.5  562.16    5333   563.6  5371.8  565.76  5399.6  569.42
  5431.4  571.81  5486.4  573.03  5503.3  573.43  5593.7  581.94  5633.1  586.62
#Mann= 8 ,-1 , 0
  4599.6     .05       0  4632.8     .12       0  4990.4     .07       0
  4995.5     .12       0  5056.9      .1       0  5255.5     .12       0
  5486.4     .05       0  5503.3     .12       0
Bank Sta=4990.4,4995.5
XS Rating Curve= 0 ,0
Exp/Cntr=0.3,0.1

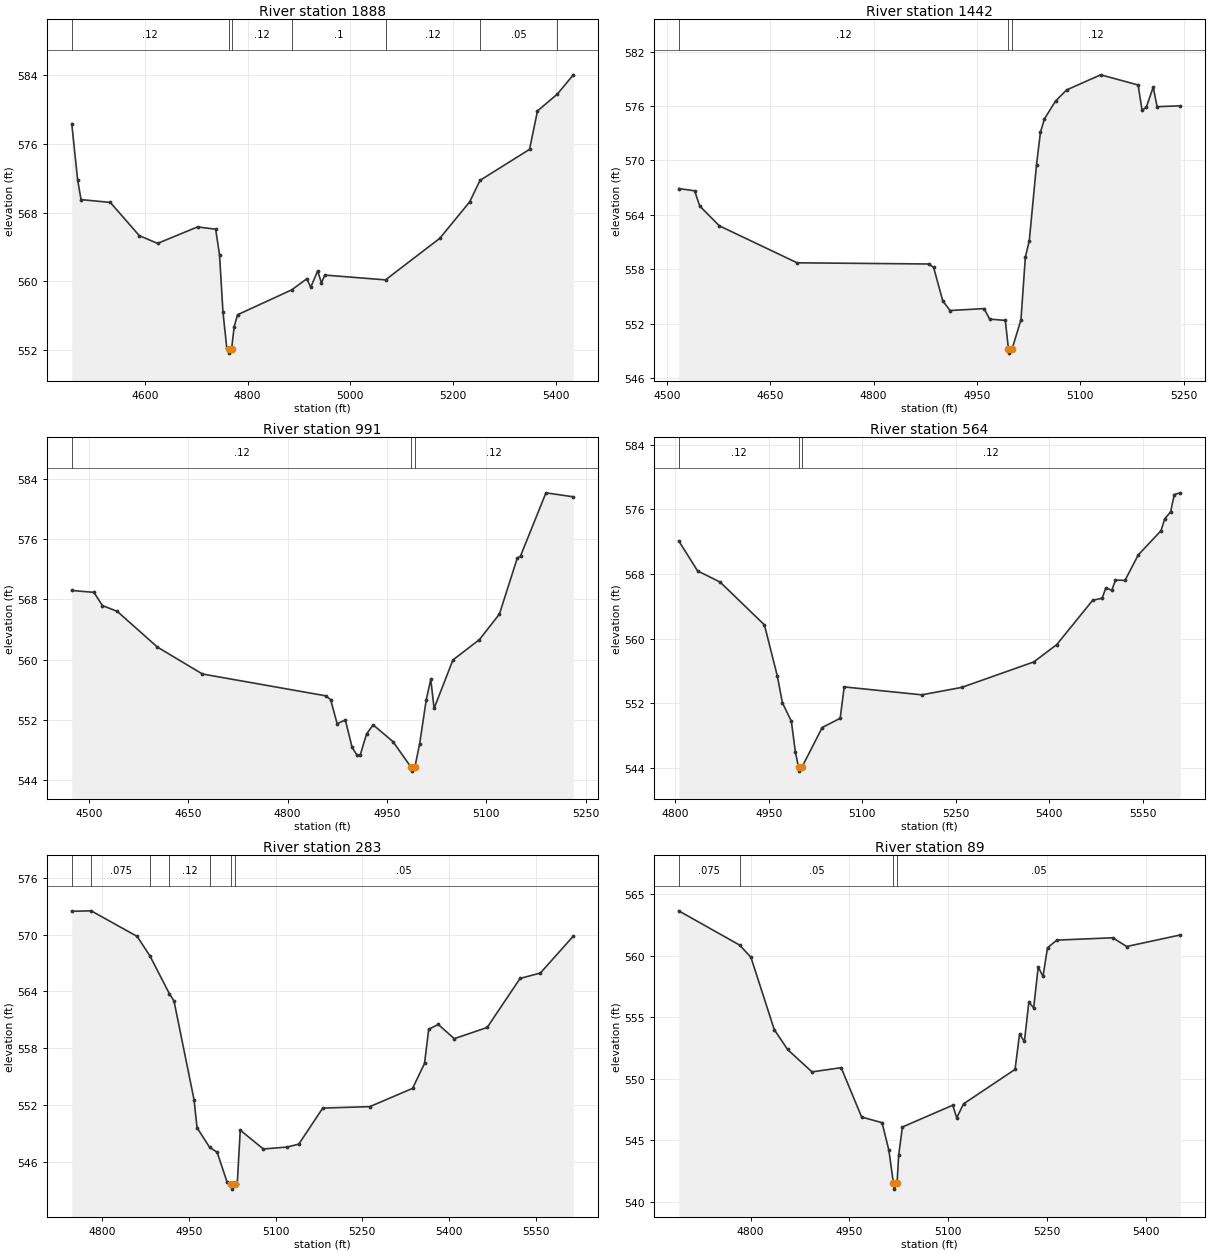
Type RM Length L Ch R = 1 ,1888    ,446,446,446
BEGIN DESCRIPTION:
West Jones Branch 4.0
END DESCRIPTION:
XS GIS Cut Line= 3
        2394342.       7032938.6      2394719.72      7032510.86
      2394929.27       7032164.1
#Sta/Elev= 30
  4457.9  578.36  4469.4  571.79    4476  569.52  4532.9  569.19  4589.4  565.32
  4624.9  564.42  4702.7  566.34  4737.9  566.07  4745.4  563.08  4752.1  556.43
  4759.6  552.18  4763.8  552.14  4764.4  551.64  4768.9  552.14  4773.9  554.74
  4780.5  556.11  4885.9  559.01  4915.2   560.3  4922.8  559.31  4936.3  561.21
  4943.7  559.82  4950.3  560.73  5068.3  560.17  5173.9  565.01  5232.1  569.26
  5252.2  571.76  5348.5  575.37    5364  579.85  5402.5   581.8  5433.7  584.05
#Mann= 7 ,-1 , 0
  4457.9     .12       0  4763.8     .07       0  4768.9     .12       0
  4885.9      .1       0  5068.3     .12       0  5252.2     .05       0
  5402.5     .12       0
Bank Sta=4763.8,4768.9
XS Rating Curve= 0 ,0
Exp/Cntr=0.3,0.1

Type RM Length L Ch R = 1 ,1442    ,451,451,451
BEGIN DESCRIPTION:
West Jones Branch 3.0
END DESCRIPTION:
XS GIS Cut Line= 3
      2394702.17      7032916.15      2394982.39      7032665.95
      2395292.55      7032498.36
#Sta/Elev= 30
  4517.2  566.89  4540.2  566.64  4547.7  564.96  4576.1  562.78    4689   558.7
  4880.4  558.57  4887.2  558.19  4900.5   554.5    4911  553.44  4960.4  553.65
  4968.6  552.49  4991.3  552.35  4995.8  549.24  4996.6  548.74  5001.3  549.24
    5014  552.42  5020.4  559.33  5026.1  561.13  5036.6  569.53  5042.3  573.09
  5048.1  574.57  5064.2  576.54  5080.4  577.77  5129.8  579.43  5184.1  578.31
  5189.8  575.54  5195.9  575.83    5206  578.07  5211.7  575.92  5245.4  576.01
#Mann= 3 ,-1 , 0
  4517.2     .12       0  4995.8     .07       0  5001.3     .12       0
Bank Sta=4995.8,5001.3
XS Rating Curve= 0 ,0
Exp/Cntr=0.3,0.1

Type RM Length L Ch R = 1 ,991     ,427,427,427
BEGIN DESCRIPTION:
West Jones Branch 2.0
END DESCRIPTION:
XS GIS Cut Line= 3
      2394797.28      7033161.26      2395185.02      7032973.65
      2395510.21      7032948.63
#Sta/Elev= 30
  4474.3   569.2  4507.8  568.95  4520.6  567.19  4542.9  566.42  4603.7  561.65
  4671.5  558.07  4857.8  555.16    4865  554.65  4874.8  551.45  4887.2  551.95
  4897.4  548.28    4905  547.23  4909.5  547.23  4919.1  550.07  4929.1   551.3
  4959.2  549.05  4986.5  545.63  4987.3  545.13    4992  545.63  4999.3  548.76
  5009.3  554.66  5016.1  557.36  5021.1  553.49  5049.5  559.94  5089.6  562.66
  5119.7  566.06  5146.5  573.48  5151.5  573.79  5189.9  582.21  5231.2  581.68
#Mann= 3 ,-1 , 0
  4474.3     .12       0  4986.5     .07       0    4992     .12       0
Bank Sta=4986.5,4992
XS Rating Curve= 0 ,0
Exp/Cntr=0.3,0.1

Type RM Length L Ch R = 1 ,564     ,281,281,281
BEGIN DESCRIPTION:
West Jones Branch 1.0
END DESCRIPTION:
XS GIS Cut Line= 3
      2395047.43      7033451.46      2395255.06      7033283.85
      2395710.37      7032998.65
#Sta/Elev= 30
  4805.8  572.09    4836  568.38  4872.1     567  4943.1  561.71  4963.9  555.36
  4971.9  552.09  4986.3   549.8  4992.7  546.02  4997.8  544.13  4998.6  543.63
  5003.3  544.13  5035.8  549.02  5064.6  550.16    5071  554.04  5195.3  553.06
  5259.5  553.98    5375  557.13  5411.6  559.26  5469.3  564.74  5484.6  565.01
  5490.5  566.29    5500  565.98  5505.9  567.25  5521.2  567.21  5542.4  570.35
  5578.9  573.35  5584.8   574.8  5594.3  575.68  5600.2  577.82  5609.9  578.03
#Mann= 3 ,-1 , 0
  4805.8     .12       0  4997.8     .07       0  5003.3     .12       0
Bank Sta=4997.8,5003.3
XS Rating Curve= 0 ,0
Exp/Cntr=0.3,0.1

Type RM Length L Ch R = 1 ,283     ,194,194,194
BEGIN DESCRIPTION:
West Jones Branch 0.5
END DESCRIPTION:
XS GIS Cut Line= 4
      2395137.46        7033529.      2395255.06      7033549.02
      2395737.87      7033418.93      2395924.11      7033255.04
#Sta/Elev= 30
  4747.5  572.45  4781.1   572.5  4860.6   569.8  4882.7  567.74  4916.5  563.73
  4924.3  562.99    4959  552.55  4964.2  549.59    4986  547.52  4998.9  547.01
  5015.9   543.9  5023.5  543.61  5024.3  543.11    5029  543.61  5033.7  543.67
  5038.9  549.34  5078.8  547.35  5119.4  547.55  5140.1  547.86  5181.6  551.67
  5262.9  551.82  5336.9  553.75  5357.6  556.39  5364.8     560  5381.4   560.5
    5409     559  5465.9  560.18  5522.8  565.36  5557.9  565.93  5614.9  569.83
#Mann= 7 ,-1 , 0
  4747.5     .05       0  4781.1    .075       0  4882.7     .05       0
  4916.5     .12       0    4986     .05       0  5023.5    .033       0
    5029     .05       0
Bank Sta=5023.5,5029
XS Rating Curve= 0 ,0
Exp/Cntr=0.3,0.1

Type RM Length L Ch R = 1 ,89      ,38,38,38
BEGIN DESCRIPTION:
West Jones Branch 0.3
END DESCRIPTION:
XS GIS Cut Line= 4
      2395175.05       7033671.6      2395377.64      7033696.61
      2395645.31      7033629.07      2395850.45      7033436.44
#Sta/Elev= 30
  4690.9  563.65  4783.5  560.86  4800.5  559.87  4835.9     554  4856.1  552.38
  4893.2  550.56  4937.5   550.9  4968.6  546.89  4999.6  546.43  5009.9   544.2
  5016.8  541.53  5017.7  541.03  5022.4  541.53  5024.8  543.78  5030.5  546.08
  5106.9  547.85    5113  546.83  5123.3  547.96  5201.5  550.76  5208.4  553.63
  5215.7  553.03  5222.5  556.23  5229.8  555.76  5236.7  559.08    5244  558.32
  5250.8  560.65    5265  561.27    5350  561.46    5371  560.75  5452.5  561.69
#Mann= 4 ,-1 , 0
  4690.9    .075       0  4783.5     .05       0  5016.8     .05       0
  5022.4     .05       0
Bank Sta=5016.8,5022.4
XS Rating Curve= 0 ,0
Exp/Cntr=0.3,0.1

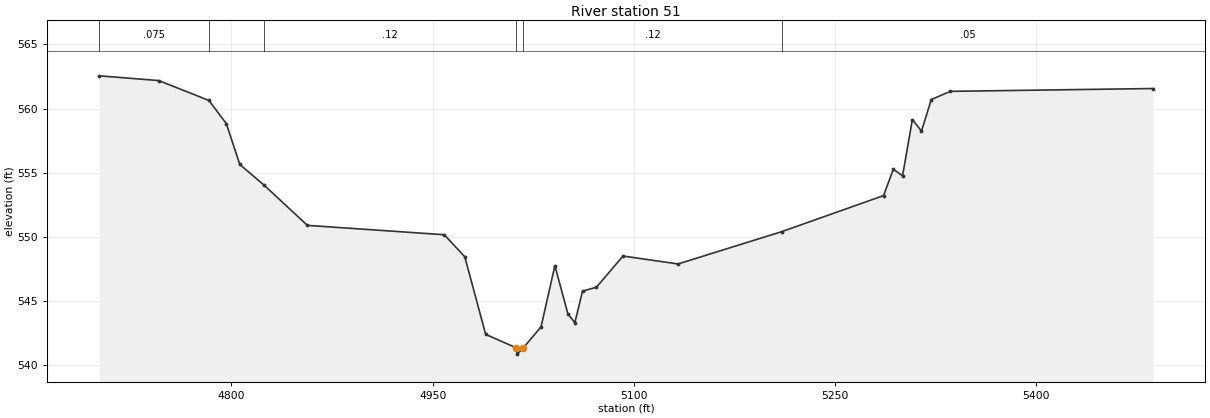
Type RM Length L Ch R = 1 ,51      ,0,0,0
BEGIN DESCRIPTION:
West Jones Branch 0.2
END DESCRIPTION:
XS GIS Cut Line= 4
      2395185.04      7033706.62      2395387.64      7033731.63
      2395655.32      7033664.09      2395864.73      7033442.21
#Sta/Elev= 30
  4701.5  562.55  4745.8  562.18  4783.2  560.63  4796.2  558.82  4806.2  555.64
  4824.5  554.01  4856.6  550.89  4958.6  550.16  4973.9  548.45  4989.5  542.39
  5012.1  541.35    5013  540.85  5017.7  541.35  5030.8  542.98  5041.1  547.75
  5050.8  543.99    5056   543.3  5061.7  545.76  5072.1  546.07  5091.9   548.5
  5132.9  547.88  5210.5  550.41  5286.1  553.21  5293.4  555.26  5300.3  554.76
  5307.6  559.14  5314.4  558.24  5321.7   560.7  5335.9  561.34  5486.8  561.56
#Mann= 6 ,-1 , 0
  4701.5    .075       0  4783.2     .05       0  4824.5     .12       0
  5012.1     .07       0  5017.7     .12       0  5210.5     .05       0
Bank Sta=5012.1,5017.7
XS Rating Curve= 0 ,0
Exp/Cntr=0.3,0.1

Chan Stop Cuts=-1
Use User Specified Reach Order=0
Composite Channel Slope=5