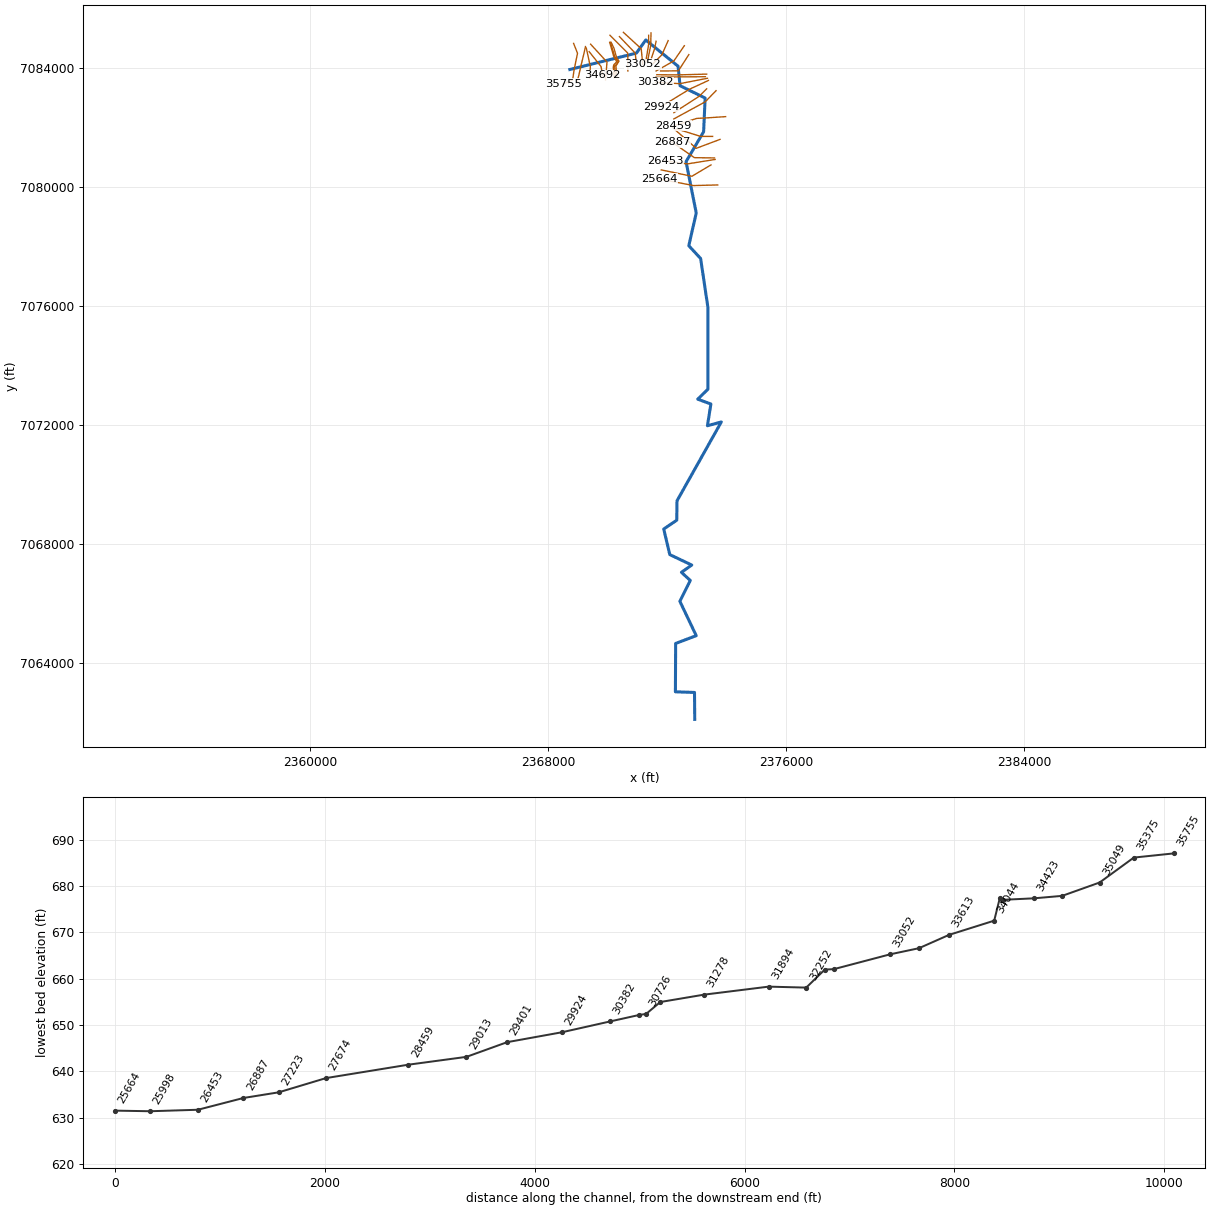
--- Whites Branch.prj (project) ---

Proj Title=Whites Branch Base Level Engineering
Current Plan=p01
Default Exp/Contr=0.3,0.1
English Units
Geom File=g01
Flow File=f01
Plan File=p01
Y Axis Title=Elevation
X Axis Title(PF)=Main Channel Distance
X Axis Title(XS)=Station
BEGIN DESCRIPTION:
Whites Branch
END DESCRIPTION:
DSS Export Rating Curves= 0
DSS Export Rating Curve Sorted= 0
DSS Export Volume Flow Curves= 0
DXF OffsetX= 0
DXF OffsetY= 0
DXF ScaleX= 1
DXF ScaleY= 10

--- Whites Branch.p01 (plan) ---

Plan Title=Multiple Run
Short Identifier=Multiple
Geom File=g01
Flow File=f01
Subcritical Flow
K Sum by GR= 0
Std Step Tol= 0.01
Critical Tol= 0.01
Num of Std Step Trials= 20
Max Error Tol= 0.3
Flow Tol Ratio= 0.001
Split Flow NTrial= 30
Split Flow Tol= 0.02
Split Flow Ratio= 0.02
Log Output Level= 0
Friction Slope Method= 1
Unsteady Friction Slope Method= 2
Unsteady Bridges Friction Slope Method= 1
Parabolic Critical Depth
Global Vel Dist=  1 , 1 , 1
Global Log Level= 0
CheckData=True
Encroach Param= -1, 0, 0, 0
BEGIN DESCRIPTION:
Multiple Run
END DESCRIPTION:

--- Whites Branch.f01 (steady flow) ---

Flow Title=Multiple
Program Version=4.10
Number of Profiles= 7
Profile Names=10-year,25-year,50-year,1pct_min,100-year,1pct_plu,500-year
River Rch & RM=Whites Branch,Reach-1         ,35755
     236     304     357     209     417     832     569
River Rch & RM=Whites Branch,Reach-1         ,32515
     412     551     664     398     794    1584    1136
River Rch & RM=Whites Branch,Reach-1         ,31278
     610     835    1020     620    1236    2466    1817
River Rch & RM=Whites Branch,Reach-1         ,28459
     774    1071    1319     806    1607    3207    2394
River Rch & RM=Whites Branch,Reach-1         ,25664
     956    1339    1662    1022    2040    4070    3081
River Rch & RM=Whites Branch,Reach-1         ,23547
    1117    1576    1966    1215    2424    4836    3695
River Rch & RM=Whites Branch,Reach-1         ,20783
    1196    1690    2110    1304    2602    5193    3971
River Rch & RM=Whites Branch,Reach-1         ,14315
    2203    3204    4078    2566    5119   10214    8094
River Rch & RM=Whites Branch,Reach-1         ,9651
    2871    4210    5388    3406    6796   13560   10847
River Rch & RM=Whites Branch,Reach-1         ,5516
    3033    4452    5700    3604    7191   14348   11482
River Rch & RM=Whites Branch,Reach-1         ,254
    3184    4677    5993    3791    7564   15092   12090
Boundary for River Rch & Prof#=Whites Branch,Reach-1         , 1
Up Type= 0
Dn Type= 3
Dn Slope=0.0005
Boundary for River Rch & Prof#=Whites Branch,Reach-1         , 2
Up Type= 0
Dn Type= 3
Dn Slope=0.0005
Boundary for River Rch & Prof#=Whites Branch,Reach-1         , 3
Up Type= 0
Dn Type= 3
Dn Slope=0.0005
Boundary for River Rch & Prof#=Whites Branch,Reach-1         , 4
Up Type= 0
Dn Type= 3
Dn Slope=0.0005
Boundary for River Rch & Prof#=Whites Branch,Reach-1         , 5
Up Type= 0
Dn Type= 3
Dn Slope=0.0005
Boundary for River Rch & Prof#=Whites Branch,Reach-1         , 6
Up Type= 0
Dn Type= 3
Dn Slope=0.0005
Boundary for River Rch & Prof#=Whites Branch,Reach-1         , 7
Up Type= 0
Dn Type= 3
Dn Slope=0.0005
DSS Import GetInterval= 0
DSS Import GetPeak= 0
DSS Import FillOption= 0

--- Whites Branch.g01 (geometry) ---

Geom Title=Existing Conditions
Program Version=4.10

River Reach=Whites Branch   ,Reach-1
Reach XY= 30
        2368729.        7083960.      2370967.17      7084511.61
      2371282.38       7084952.6      2372368.65      7084070.12
      2372434.16      7083415.41      2373278.01      7082999.76
      2373227.03      7081865.89      2372636.25       7080860.3
      2372979.19      7079135.09      2372728.68      7078034.89
      2373126.94      7077604.15      2373371.44        7075960.
      2373371.72      7073209.95      2373029.51      7072875.89
      2373471.52      7072713.62      2373355.02      7071982.51
      2373822.09      7072110.05      2372332.54      7069458.54
      2372323.63      7068807.62      2371886.05      7068510.07
      2372089.61      7067649.94      2372828.46      7067299.36
      2372480.85       7067054.2      2372779.48      7066780.46
      2372429.03      7066080.05      2372978.64      7064925.17
      2372286.77      7064663.43      2372278.63      7063037.12
      2372920.84      7063016.05        2372929.        7062110.

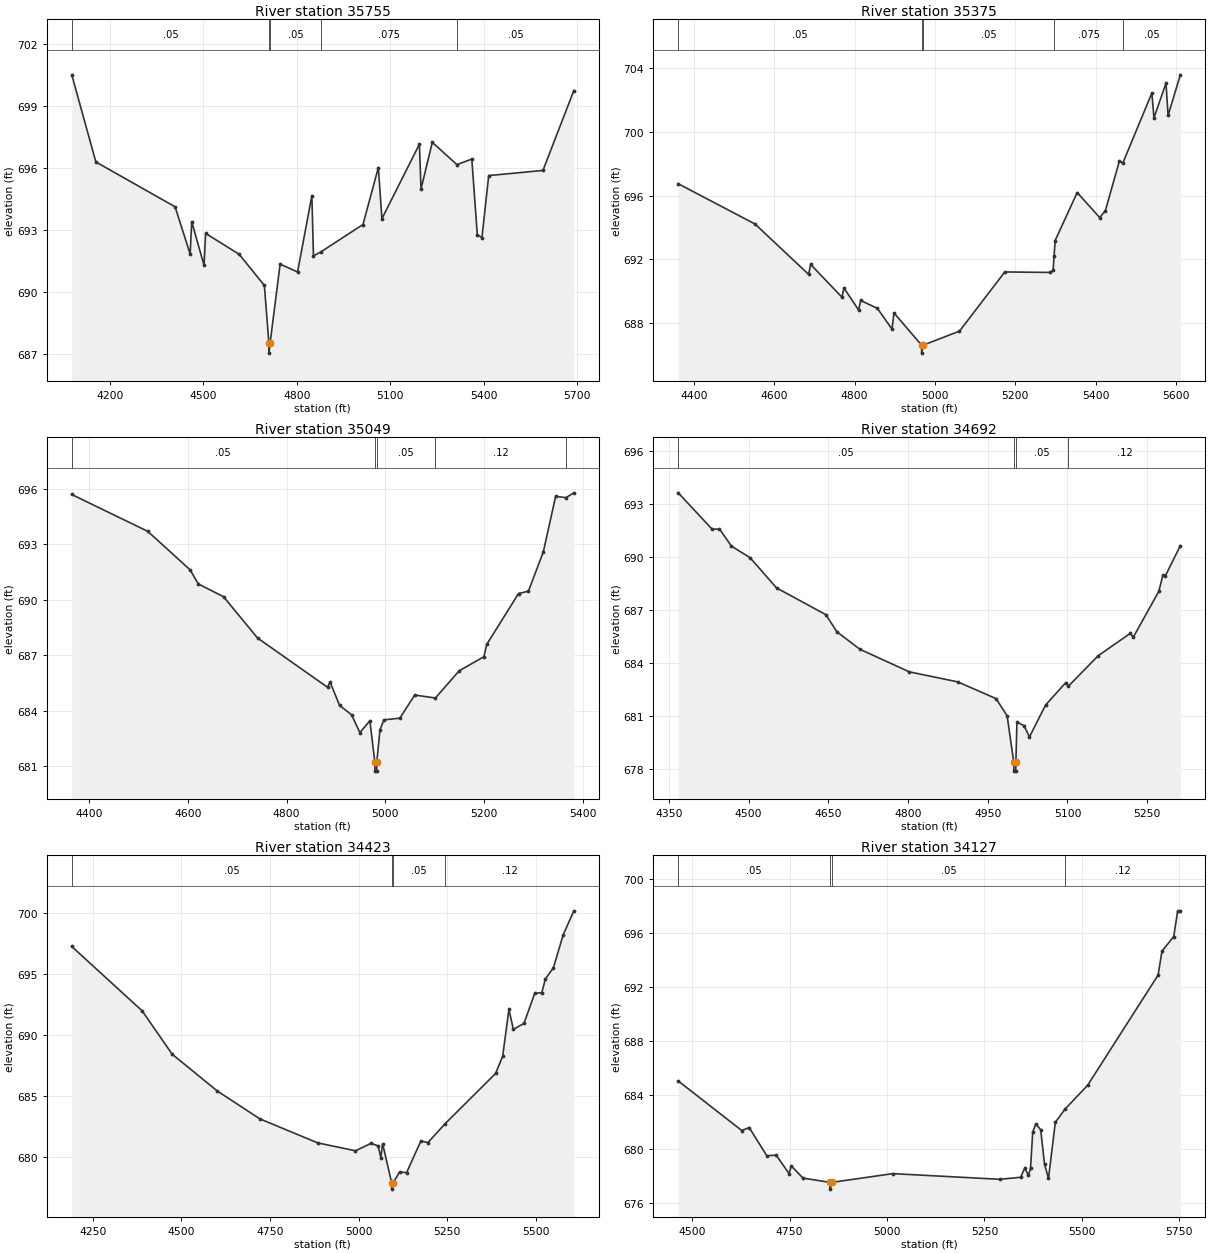
Type RM Length L Ch R = 1 ,35755   ,380,380,380
BEGIN DESCRIPTION:
Whites Branch 77.0
END DESCRIPTION:
XS GIS Cut Line= 6
      2368855.85       7084838.2      2368988.68      7084504.82
      2368931.39      7084233.99      2368870.19        7083928.
      2368821.19      7083607.62      2368507.29      7083474.29
#Sta/Elev= 30
  4077.3   700.5  4154.7  696.28  4409.1  694.11  4457.6  691.82  4462.7  693.39
  4502.2  691.27  4507.3  692.82  4614.9  691.81    4696   690.3  4710.5  687.52
  4710.7  687.02  4714.5  687.52  4746.6  691.33  4802.7  690.95  4848.6  694.65
  4853.7  691.73  4877.2  691.92  5012.8  693.25  5062.2  696.01  5073.6  693.53
  5194.1  697.14  5199.2  694.97  5235.5  697.23  5314.7  696.15  5362.4  696.42
  5380.1  692.75    5395  692.62  5416.7  695.62    5591  695.87  5690.2  699.74
#Mann= 5 ,-1 , 0
  4077.3     .05       0  4710.5     .07       0  4714.5     .05       0
  4877.2    .075       0  5314.7     .05       0
Bank Sta=4710.5,4714.5
XS Rating Curve= 0 ,0
Exp/Cntr=0.3,0.1

Type RM Length L Ch R = 1 ,35375   ,326,326,326
BEGIN DESCRIPTION:
Whites Branch 76.0
END DESCRIPTION:
XS GIS Cut Line= 5
      2369254.74      7084731.37      2369197.37      7084469.01
      2369108.82      7084109.72      2369031.22       7083763.5
      2368966.12      7083516.13
#Sta/Elev= 30
  4361.4  696.74  4552.2  694.22  4685.7  691.06  4690.9  691.68  4768.7  689.63
  4773.8   690.2  4810.2  688.82  4815.3  689.42  4856.8  688.93  4893.2  687.63
  4898.3  688.64  4966.8  686.62  4967.1  686.12  4970.8  686.62  5061.2   687.5
  5173.9  691.21  5286.7  691.18  5294.1  691.32  5296.5   692.2  5299.2  693.18
    5354  696.19  5410.1  694.62  5424.1  695.05  5459.2  698.18  5467.6  698.04
  5539.9  702.43    5545  700.87    5575  703.05  5580.2  701.02  5610.6  703.57
#Mann= 5 ,-1 , 0
  4361.4     .05       0  4966.8     .05       0  4970.8     .05       0
  5296.5    .075       0  5467.6     .05       0
Bank Sta=4966.8,4970.8
XS Rating Curve= 0 ,0
Exp/Cntr=0.3,0.1

Type RM Length L Ch R = 1 ,35049   ,357,357,357
BEGIN DESCRIPTION:
Whites Branch 75.0
END DESCRIPTION:
XS GIS Cut Line= 3
      2369282.96      7084680.56      2369418.81      7084059.55
      2369391.35      7083678.14
#Sta/Elev= 30
  4364.3  695.68  4518.4  693.69  4604.3  691.61  4620.8  690.85    4672  690.16
    4741  687.93  4882.9  685.27    4888  685.55  4907.4  684.29  4931.8  683.78
  4948.4  682.82  4968.8  683.46  4978.8  681.24  4979.1  680.74  4982.6  680.74
  4982.8  681.24  4989.3  682.97  4997.2  683.51  5029.6   683.6  5059.7  684.85
  5101.7  684.69  5149.9  686.16  5200.1  686.92  5205.7  687.58  5270.2  690.33
  5290.3  690.46  5320.4  692.57  5345.5  695.58  5366.4  695.51  5382.4  695.77
#Mann= 5 ,-1 , 0
  4364.3     .05       0  4978.8    .033       0  4982.8     .05       0
  5101.7     .12       0  5366.4     .05       0
Bank Sta=4978.8,4982.8
XS Rating Curve= 0 ,0
Exp/Cntr=0.3,0.1

Type RM Length L Ch R = 1 ,34692   ,269,269,269
BEGIN DESCRIPTION:
Whites Branch 74.0
END DESCRIPTION:
XS GIS Cut Line= 3
      2369379.01      7084559.98        2369779.        7084060.
        2369829.      7083760.03
#Sta/Elev= 30
  4367.8  693.64  4431.8  691.57  4445.4  691.59  4467.8  690.62    4503  689.96
  4552.7  688.25  4645.5  686.73  4666.3  685.76  4709.5  684.77  4802.4  683.49
  4893.6  682.92  4965.7  681.97  4986.5  680.99  4998.9  678.36  4999.1  677.86
  5002.6  677.86  5002.9  678.36  5004.9  680.64  5018.2  680.44  5028.4   679.8
  5058.8  681.61  5096.8  682.88  5101.8  682.68  5157.6   684.4  5218.5  685.68
  5223.5  685.44  5271.7  688.05  5279.3  688.96  5284.3  688.95  5312.2  690.64
#Mann= 4 ,-1 , 0
  4367.8     .05       0  4998.9    .033       0  5002.9     .05       0
  5101.8     .12       0
Bank Sta=4998.9,5002.9
XS Rating Curve= 0 ,0
Exp/Cntr=0.3,0.1

Type RM Length L Ch R = 1 ,34423   ,296,296,296
BEGIN DESCRIPTION:
Whites Branch 73.0
END DESCRIPTION:
XS GIS Cut Line= 3
      2369428.99      7084810.01        2369979.        7084210.
        2369929.      7083610.03
#Sta/Elev= 30
    4191  697.26  4389.3  691.98  4474.3  688.41  4601.4  685.39  4721.6   683.1
  4884.4  681.13  4991.1  680.48  5035.1  681.09  5055.1  680.88  5062.6  679.92
  5067.7  681.06  5093.3  677.83  5093.5  677.33  5097.3  677.83  5115.3  678.73
  5135.4  678.69  5175.5  681.28  5195.6  681.16  5244.1  682.71  5386.3  686.83
  5406.3  688.25  5423.9  692.09  5436.4  690.45  5466.5  690.95  5496.6  693.41
  5516.7  693.47  5526.8   694.6  5549.3  695.51  5576.9  698.22    5607  700.19
#Mann= 4 ,-1 , 0
    4191     .05       0  5093.3    .033       0  5097.3     .05       0
  5244.1     .12       0
Bank Sta=5093.3,5097.3
XS Rating Curve= 0 ,0
Exp/Cntr=0.3,0.1

Type RM Length L Ch R = 1 ,34127   ,29,29,29
BEGIN DESCRIPTION:
Mapping XS 3a9b0843
END DESCRIPTION:
XS GIS Cut Line= 6
      2370068.27       7084872.3      2370207.17       7084393.1
      2370307.87      7084217.76      2370207.17       7084118.8
      2370189.81      7084049.35      2370220.91      7083683.16
#Sta/Elev= 30
  4464.6  685.04  4627.6  681.36  4646.5  681.58  4691.8  679.49  4715.9  679.53
  4749.1  678.16  4754.3  678.74  4784.6  677.83  4854.1  677.51  4854.3  677.01
  4858.1  677.51  5014.8  678.16  5289.2  677.74  5342.9  677.89  5353.2  678.57
  5362.9  678.04  5368.1  678.56  5373.8  681.26  5381.9  681.85  5394.2  681.42
  5404.2  678.84  5414.2  677.81  5431.8  681.97  5456.9  682.96  5514.6  684.72
  5695.3   692.9  5705.3  694.68  5735.4  695.76  5745.4  697.63  5752.3  697.67
#Mann= 4 ,-1 , 0
  4464.6     .05       0  4854.1    .033       0  4858.1     .05       0
  5456.9     .12       0
Bank Sta=4854.1,4858.1
XS Rating Curve= 0 ,0
Exp/Cntr=0.3,0.1

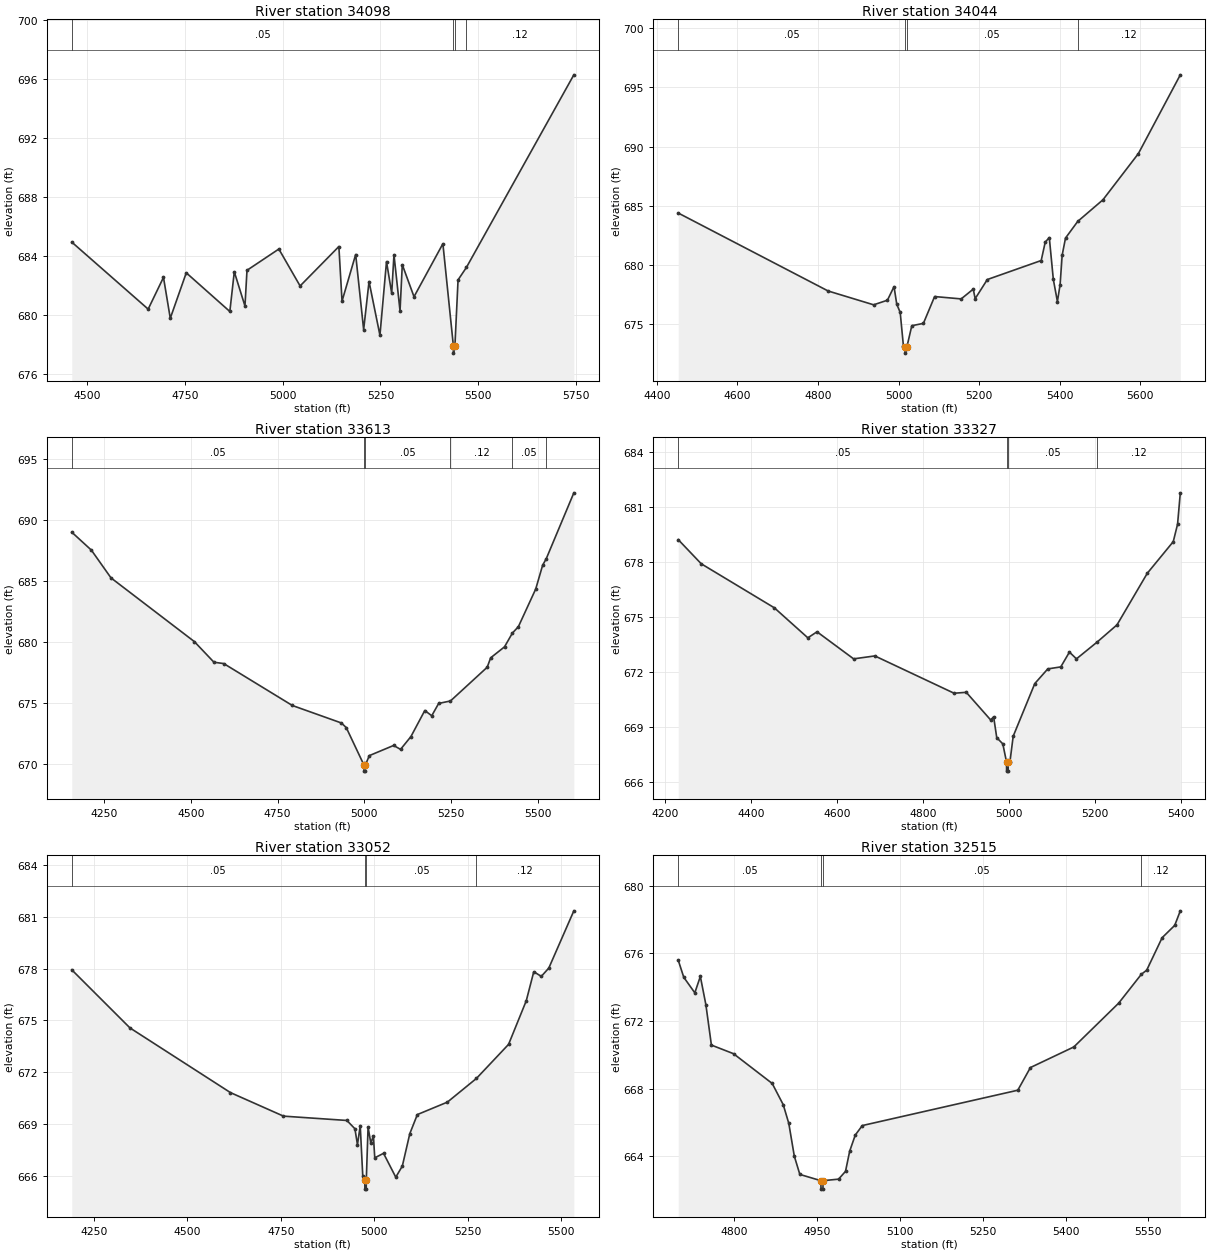
Type RM Length L Ch R = 1 ,34098   ,54,54,54
BEGIN DESCRIPTION:
Mapping XS 3e640cef
END DESCRIPTION:
XS GIS Cut Line= 6
      2370092.59      7084875.74      2370248.84      7084360.12
      2370349.54      7084231.65      2370311.34       7084143.1
      2370234.95      7084084.08      2370262.69      7083704.47
#Sta/Elev= 30
    4460  684.94  4655.5   680.4  4694.7  682.55  4712.1  679.78    4753  682.86
  4864.5  680.24  4875.9  682.93  4903.2  680.61  4908.4  683.03  4989.9  684.47
  5044.3  681.97  5143.5  684.64  5151.6  680.94  5186.5   684.1  5206.9  679.01
  5220.7  682.27  5248.6  678.63  5265.4  683.62  5278.7  681.47  5284.5  684.09
    5300  680.28  5305.8  683.41  5335.8  681.24  5409.7  684.83  5436.5  677.92
  5436.7  677.42  5440.5  677.92  5448.5  682.38  5469.8  683.22  5744.8  696.27
#Mann= 4 ,-1 , 0
    4460     .05       0  5436.5    .033       0  5440.5     .05       0
  5469.8     .12       0
Bank Sta=5436.5,5440.5
XS Rating Curve= 0 ,0
Exp/Cntr=0.3,0.1

Type RM Length L Ch R = 1 ,34044   ,431,431,431
BEGIN DESCRIPTION:
Mapping XS 76b889ea
END DESCRIPTION:
XS GIS Cut Line= 6
      2370118.64      7084872.25      2370214.12      7084672.62
      2370300.92      7084361.85      2370382.52      7084240.33
      2370278.35      7084078.87      2370313.08      7083726.45
#Sta/Elev= 30
  4453.4  684.37  4825.4  677.77  4938.3   676.6  4972.5  676.99  4988.9  678.14
  4995.7  676.64  5004.2  675.96  5012.2  673.11  5016.6  673.01  5016.8  672.51
  5020.6  673.01    5033  674.83  5061.8  675.03  5089.6   677.3  5155.5   677.1
  5185.5  677.93  5190.2  677.12  5220.4  678.74  5354.1  680.35  5364.1  681.91
  5374.2  682.29  5384.2  678.75  5394.3  676.88    5401   678.3  5406.1   680.8
  5414.4  682.25  5444.7  683.66  5507.3  685.49  5595.2   689.4  5699.3  696.07
#Mann= 4 ,-1 , 0
  4453.4     .05       0  5016.6    .033       0  5020.6     .05       0
  5444.7     .12       0
Bank Sta=5016.6,5020.6
XS Rating Curve= 0 ,0
Exp/Cntr=0.3,0.1

Type RM Length L Ch R = 1 ,33613   ,286,286,286
BEGIN DESCRIPTION:
Whites Branch 70.0
END DESCRIPTION:
XS GIS Cut Line= 3
      2370078.97      7085110.03        2370679.        7084510.
        2370679.      7083909.98
#Sta/Elev= 30
    4156  688.99  4212.6  687.52  4269.2  685.25  4509.6  680.04  4566.2  678.35
  4594.5  678.24  4792.4  674.81  4933.9  673.38    4948     673    4999  669.94
  4999.3  669.44  5002.8  669.44    5003  669.94  5014.6  670.71  5084.6  671.54
  5104.6  671.22  5134.6  672.27  5174.6   674.4  5194.6  673.97  5214.6  674.98
  5248.6  675.18  5354.6  677.94  5364.6  678.71  5404.6  679.61  5427.2  680.73
  5444.6  681.26  5494.6  684.34  5514.6  686.29    5525  686.82  5604.6  692.21
#Mann= 6 ,-1 , 0
    4156     .05       0    4999    .033       0    5003     .05       0
  5248.6     .12       0  5427.2     .05       0    5525     .12       0
Bank Sta=4999,5003
XS Rating Curve= 0 ,0
Exp/Cntr=0.3,0.1

Type RM Length L Ch R = 1 ,33327   ,275,275,275
BEGIN DESCRIPTION:
Whites Branch 69.0
END DESCRIPTION:
XS GIS Cut Line= 3
      2370398.27      7085064.89        2370929.        7084510.
      2370966.74      7084113.63
#Sta/Elev= 30
  4231.5  679.23  4284.9  677.91  4454.8   675.5  4532.5  673.86  4553.8  674.19
  4638.8  672.71  4688.1  672.87  4872.1  670.83  4900.4  670.88    4957  669.37
    4964  669.54  4971.2   668.4  4985.3  668.06  4993.9  667.07  4994.1  666.57
  4997.6  666.57  4997.9  667.07  5001.8  667.07  5009.4  668.48  5059.6  671.36
  5089.7  672.16  5119.9  672.27    5140  673.08  5156.3  672.71  5203.9  673.62
  5250.5  674.57  5320.8  677.39  5381.1  679.12  5391.1  680.07  5397.5  681.79
#Mann= 4 ,-1 , 0
  4231.5     .05       0  4993.9     .04       0  4997.9     .05       0
  5203.9     .12       0
Bank Sta=4993.9,4997.9
XS Rating Curve= 0 ,0
Exp/Cntr=0.3,0.1

Type RM Length L Ch R = 1 ,33052   ,537,537,537
BEGIN DESCRIPTION:
Whites Branch 68.0
END DESCRIPTION:
XS GIS Cut Line= 3
      2370528.99      7085210.01        2371129.        7084660.
      2371181.55      7084133.37
#Sta/Elev= 30
  4190.8  677.93  4346.5  674.57  4615.4  670.83  4757.2  669.47  4926.8  669.22
  4948.3  668.74  4955.1  667.82  4962.5  668.92  4969.3  666.01  4974.7  665.75
    4975  665.25  4978.5  665.25  4978.7  665.75  4983.5  668.83  4990.9  667.91
  4997.7  668.33  5001.4  667.06  5024.9  667.32  5057.6  665.94  5075.1  666.58
  5095.2  668.46  5115.3  669.56  5195.7  670.28  5273.4  671.65  5359.4  673.62
  5406.7  676.14  5426.8  677.82  5446.9  677.55    5467  678.03    5534  681.34
#Mann= 4 ,-1 , 0
  4190.8     .05       0  4974.7     .04       0  4978.7     .05       0
  5273.4     .12       0
Bank Sta=4974.7,4978.7
XS Rating Curve= 0 ,0
Exp/Cntr=0.3,0.1

Type RM Length L Ch R = 1 ,32515   ,86,86,86
BEGIN DESCRIPTION:
Whites Branch 67.0
END DESCRIPTION:
XS GIS Cut Line= 3
        2371379.      7085110.03        2371379.        7084810.
        2371279.      7084210.01
#Sta/Elev= 30
  4699.4  675.59  4709.4  674.58  4729.4  673.66  4739.4  674.63  4749.4  672.96
  4759.4  670.57  4799.4  670.06  4869.4   668.3  4889.4  667.04  4899.4  665.94
  4909.4     664  4919.4  662.92  4957.4  662.55  4957.7  662.05  4961.2  662.05
  4961.4  662.55  4989.4  662.64    5002   663.1  5009.6   664.3  5019.7  665.25
  5032.4  665.81  5313.7   667.9  5336.5  669.24  5415.1  670.46  5496.2  673.05
  5537.3  674.76  5546.9     675  5574.8  676.92  5597.6  677.65  5607.7  678.51
#Mann= 4 ,-1 , 0
  4699.4     .05       0  4957.4    .033       0  4961.4     .05       0
  5537.3     .12       0
Bank Sta=4957.4,4961.4
XS Rating Curve= 0 ,0
Exp/Cntr=0.3,0.1

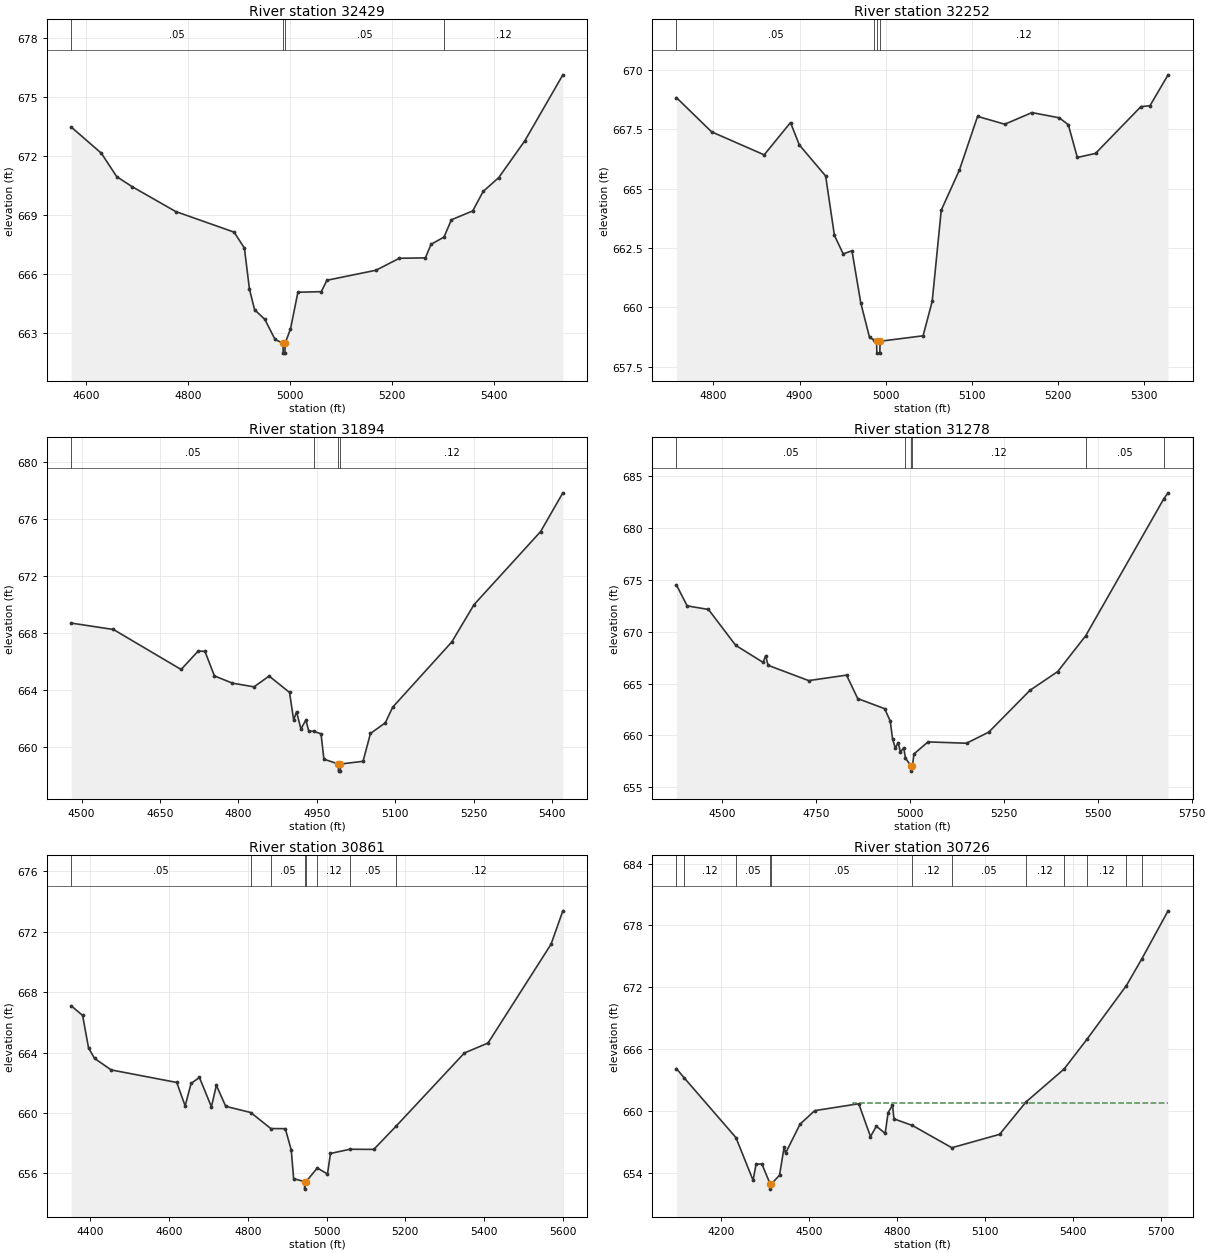
Type RM Length L Ch R = 1 ,32429   ,177,177,177
BEGIN DESCRIPTION:
Mapping XS 94145e5b
END DESCRIPTION:
XS GIS Cut Line= 3
      2371459.09      7085188.85      2371448.67      7084769.55
       2371341.9      7084236.97
#Sta/Elev= 30
  4571.4  673.47  4630.3  672.14  4660.3  670.95  4690.3  670.44  4775.9  669.17
  4890.3  668.12  4910.4  667.31  4920.4  665.21  4930.4  664.17  4950.4  663.68
  4970.4  662.66  4986.1  662.46  4986.3  661.96  4989.8  661.96  4990.1  662.46
  5000.6  663.18  5015.2  665.06  5061.1  665.09    5072  665.67    5168  666.18
  5213.9  666.79  5264.8  666.81  5275.9   667.5  5301.3  667.87  5315.7  668.75
  5357.5   669.2  5377.9  670.19  5408.5   670.9  5459.5  672.77    5534  676.13
#Mann= 4 ,-1 , 0
  4571.4     .05       0  4986.1    .033       0  4990.1     .05       0
  5301.3     .12       0
Bank Sta=4986.1,4990.1
XS Rating Curve= 0 ,0
Exp/Cntr=0.3,0.1

Type RM Length L Ch R = 1 ,32252   ,358,358,358
BEGIN DESCRIPTION:
Whites Branch 66.0
END DESCRIPTION:
XS GIS Cut Line= 3
      2371628.99      7084909.97        2371579.        7084660.
      2371479.02      7084360.05
#Sta/Elev= 30
    4757  668.83  4797.8  667.39  4858.9  666.42  4889.5  667.78  4899.7  666.84
  4930.3  665.53  4940.5  663.03  4950.7  662.25  4960.9  662.38  4971.1  660.19
  4981.3  658.73    4987  658.62  4989.5  658.57  4989.8  658.07  4993.3  658.07
  4993.5  658.57  5043.5   658.8  5054.1  660.25  5064.6  664.09  5085.7  665.78
  5106.8  668.04  5138.4  667.71    5170   668.2  5201.7  667.98  5212.2  667.69
  5222.7  666.31  5243.8  666.48  5296.5  668.45  5307.1  668.49  5328.1  669.79
#Mann= 4 ,-1 , 0
    4757     .05       0    4987     .12       0  4989.5     .07       0
  4993.5     .12       0
Bank Sta=4989.5,4993.5
XS Rating Curve= 0 ,0
Exp/Cntr=0.3,0.1

Type RM Length L Ch R = 1 ,31894   ,616,616,616
BEGIN DESCRIPTION:
Whites Branch 65.0
END DESCRIPTION:
XS GIS Cut Line= 3
       2372034.6      7084932.52        2371829.        7084460.
      2371528.98      7084159.98
#Sta/Elev= 30
  4480.4  668.68    4561  668.23  4690.4  665.42  4723.1  666.72    4736  666.69
    4754  664.97  4788.5  664.46  4829.7   664.2  4858.6  664.96  4897.6  663.81
  4905.5  661.87    4911  662.45  4919.4  661.24  4928.9  661.87  4934.4  661.08
  4943.5  661.08  4957.8   660.9  4963.3  659.12    4991  658.78  4991.2  658.28
  4994.7  658.28    4995  658.78  5038.1  658.97  5052.3  660.93  5080.6  661.67
  5094.7  662.77  5207.8  667.36  5250.3  669.98  5377.5  675.11    5420  677.83
#Mann= 4 ,-1 , 0
  4480.4     .05       0  4943.5     .12       0    4991     .07       0
    4995     .12       0
Bank Sta=4991,4995
XS Rating Curve= 0 ,0
Exp/Cntr=0.3,0.1

Type RM Length L Ch R = 1 ,31278   ,417,417,417
BEGIN DESCRIPTION:
Whites Branch 63.0
END DESCRIPTION:
XS GIS Cut Line= 3
        2372579.        7084760.      2372227.24      7084248.11
      2371628.98      7083909.99
#Sta/Elev= 30
  4378.9  674.51  4407.3  672.49  4464.1  672.14  4536.6  668.68  4609.4  667.04
  4616.4  667.69  4622.5  666.76  4730.8  665.28  4831.5  665.81  4861.3  663.55
    4933  662.57  4947.9  661.37    4954  659.66  4961.3  658.78  4968.9  659.29
    4975   658.4  4983.8   658.8  4988.3  657.81    5003  657.05  5003.3  656.55
    5007  657.05  5010.8   658.2  5048.3  659.37  5150.8  659.24    5210  660.31
  5319.6  664.34  5393.4  666.15  5467.9   669.6  5675.9  682.82  5687.2  683.39
#Mann= 6 ,-1 , 0
  4378.9     .05       0  4988.3     .12       0    5003     .07       0
    5007     .12       0  5467.9     .05       0  5675.9     .12       0
Bank Sta=5003,5007
XS Rating Curve= 0 ,0
Exp/Cntr=0.3,0.1

Type RM Length L Ch R = 1 ,30861   ,135,135,135
BEGIN DESCRIPTION:
Whites Branch 62.0
END DESCRIPTION:
XS GIS Cut Line= 3
      2372729.02      7084460.03      2372379.02      7083914.68
      2371779.04        7083910.
#Sta/Elev= 30
    4352  667.09  4380.8  666.46    4396   664.3  4411.2  663.61  4453.5  662.85
  4619.9  662.02  4641.1  660.47  4656.3  661.96  4677.4  662.35  4707.8  660.41
  4720.4  661.83  4744.2  660.44  4807.7  660.03  4858.6  658.97  4895.4  658.96
  4910.5  657.55  4916.6  655.65  4944.2  655.46  4944.4  654.96  4948.2  655.46
  4976.7  656.36  5002.5  655.96    5010  657.32  5059.4   657.6    5120  657.59
    5176  659.11    5350  663.97    5410  664.63    5570  671.17    5600  673.38
#Mann= 8 ,-1 , 0
    4352     .05       0  4807.7     .12       0  4858.6     .05       0
  4944.2     .07       0  4948.2     .05       0  4976.7     .12       0
  5059.4     .05       0    5176     .12       0
Bank Sta=4944.2,4948.2
XS Rating Curve= 0 ,0
Exp/Cntr=0.3,0.1

Type RM Length L Ch R = 1 ,30726   ,68,68,68
BEGIN DESCRIPTION:
Mapping XS 16a99247
END DESCRIPTION:
XS GIS Cut Line= 3
      2373330.17      7083804.97      2372370.09      7083778.93
      2371654.84      7083784.14
#Sta/Elev= 30
  4048.2   664.1  4074.4  663.21    4251   657.4  4309.5  653.25  4319.5  654.83
  4339.5  654.84  4367.5   652.9  4367.7   652.4  4371.5   652.9  4399.5  653.75
  4415.2  656.47  4420.2   655.9  4469.5  658.71  4519.5  660.02  4669.6  660.69
  4709.6   657.5  4729.6  658.51  4759.6  657.81  4769.6  659.82  4784.6  660.55
  4789.7  659.22  4852.4  658.58    4987  656.42  5149.7  657.72  5239.5  660.86
  5369.5  664.06  5448.7     667  5581.8  672.16  5634.5  674.76  5723.9  679.42
#Mann= 12 ,-1 , 0
  4048.2     .05       0  4074.4     .12       0    4251     .05       0
  4367.5    .033       0  4371.5     .05       0  4852.4     .12       0
    4987     .05       0  5239.5     .12       0  5369.5     .05       0
  5448.7     .12       0  5581.8     .05       0  5634.5     .12       0
#XS Ineff= 2 , 0
       0                  4649.6       0  660.76
Permanent Ineff=
       F       F
Bank Sta=4367.5,4371.5
XS Rating Curve= 0 ,0
Exp/Cntr=0.3,0.1

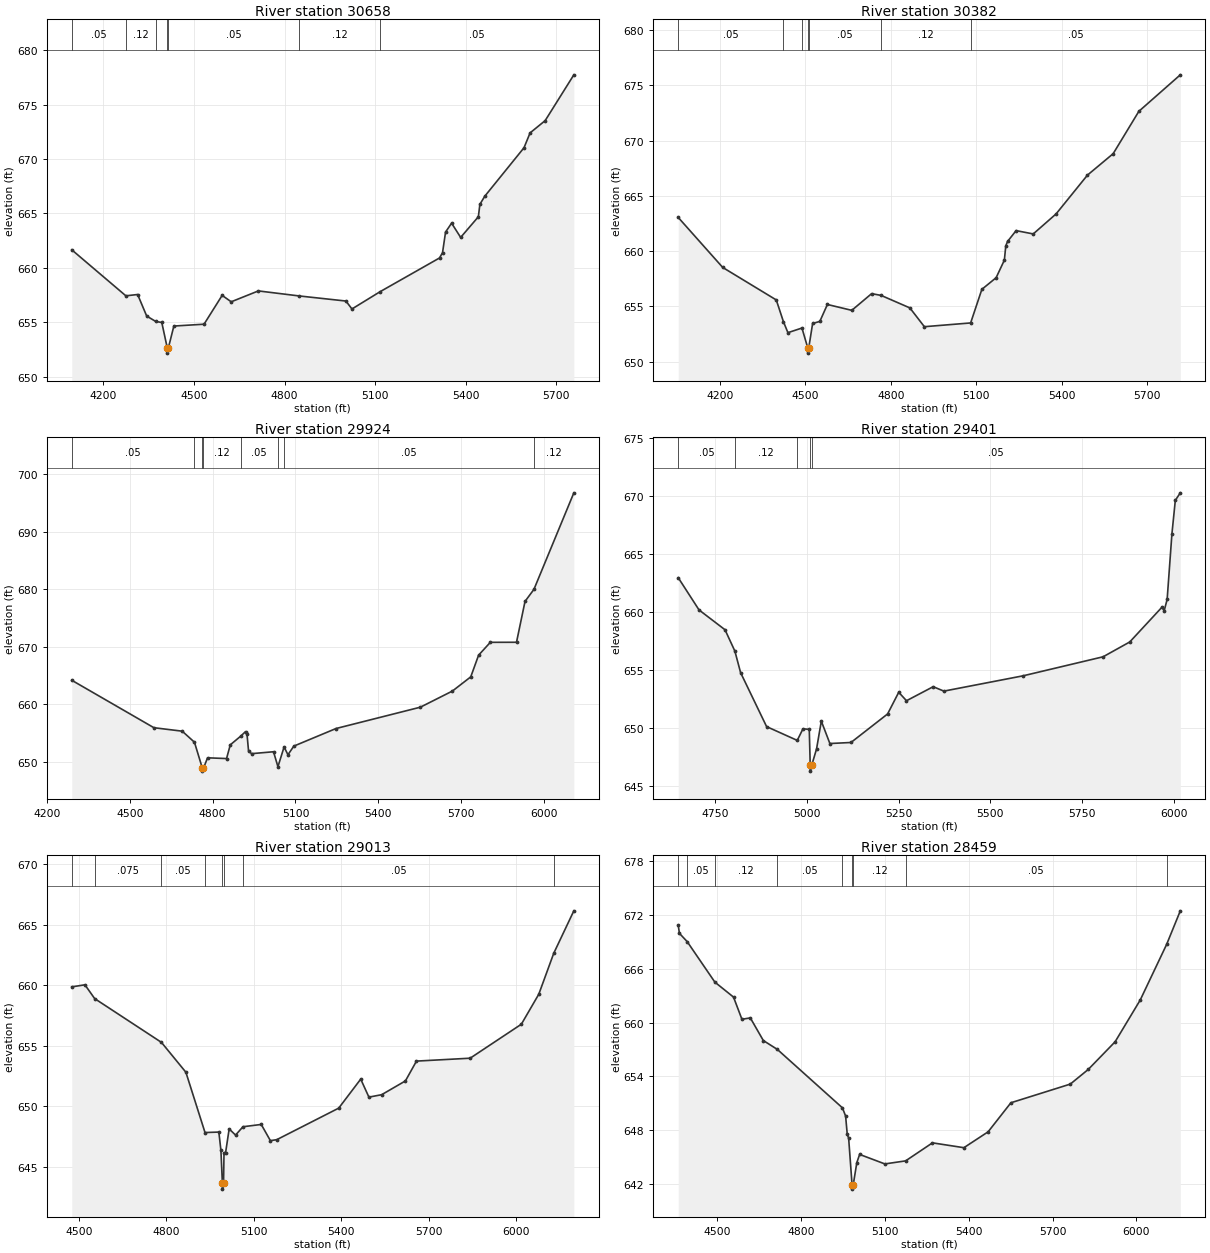
Type RM Length L Ch R = 1 ,30658   ,276,276,276
BEGIN DESCRIPTION:
Mapping XS ce653e03
END DESCRIPTION:
XS GIS Cut Line= 3
      2373287.22       7083717.3      2372373.99      7083712.09
      2371624.03      7083699.93
#Sta/Elev= 30
  4095.1  661.66  4274.3  657.43  4313.3  657.55  4343.3  655.57  4373.4  655.07
  4393.3  654.98  4411.3  652.66  4411.6  652.16  4415.3  652.66  4433.3  654.65
  4533.3  654.82  4593.3  657.47  4623.3  656.88  4713.3  657.88  4847.8  657.42
  5003.3  656.95  5023.3  656.22  5117.2  657.82  5313.4  660.91  5323.4   661.4
  5333.4  663.29  5353.4  664.11  5383.4   662.8  5442.1   664.7  5447.1  665.84
  5463.4  666.59  5593.4  671.05  5613.4  672.41  5663.4  673.54  5758.4  677.75
#Mann= 7 ,-1 , 0
  4095.1     .05       0  4274.3     .12       0  4373.4     .05       0
  4411.3     .07       0  4415.3     .05       0  4847.8     .12       0
  5117.2     .05       0
#XS Ineff= 2 , 0
       0                  4713.3       0  657.88
Permanent Ineff=
       F       F
Bank Sta=4411.3,4415.3
XS Rating Curve= 0 ,0
Exp/Cntr=0.3,0.1

Type RM Length L Ch R = 1 ,30382   ,458,458,458
BEGIN DESCRIPTION:
Whites Branch 61.0
END DESCRIPTION:
XS GIS Cut Line= 3
      2373356.63      7083664.78      2372428.52      7083484.81
      2371613.75      7083525.88
#Sta/Elev= 30
  4054.6  663.04  4210.6  658.52  4398.5  655.58  4423.4  653.63  4439.3  652.62
  4488.6  653.04  4508.6  651.27  4508.8  650.77  4512.6  651.27    4526  653.45
  4551.3  653.64  4577.8  655.17  4663.4  654.64    4733  656.15  4766.3  655.99
  4867.1  654.86    4918  653.16  5080.3   653.5  5119.7  656.54  5169.7  657.59
  5198.6  659.18  5203.6  660.47  5209.8  660.87  5239.8  661.85  5299.9  661.55
    5380  663.36  5490.1  666.87  5580.3  668.81  5670.4  672.64  5815.8  675.94
#Mann= 7 ,-1 , 0
  4054.6     .05       0  4423.4     .12       0  4488.6     .05       0
  4508.6     .07       0  4512.6     .05       0  4766.3     .12       0
  5080.3     .05       0
#XS Ineff= 2 , 0
       0                    4733       0  656.15
Permanent Ineff=
       F       F
Bank Sta=4508.6,4512.6
XS Rating Curve= 0 ,0
Exp/Cntr=0.3,0.1

Type RM Length L Ch R = 1 ,29924   ,523,523,523
BEGIN DESCRIPTION:
Whites Branch 60.0
END DESCRIPTION:
XS GIS Cut Line= 3
      2373390.01      7083591.84       2372745.6      7083293.32
      2371800.64      7082714.19
#Sta/Elev= 30
  4289.8   664.2  4587.3  655.97  4689.9  655.37  4734.2  653.45  4762.8  648.94
  4763.1  648.44  4766.8  648.94  4781.6  650.75  4850.4  650.62    4864     653
  4901.5   654.5  4919.1  655.29  4924.6   654.8  4930.1  651.93  4941.1  651.47
  5020.6   651.8  5036.5   649.2  5058.8  652.63  5072.8  651.28  5094.1  652.78
  5246.9  655.83  5552.4  659.53  5668.5  662.33  5734.9  664.79  5763.3  668.55
  5805.8  670.78  5900.6  670.79  5931.5  677.88  5963.8  679.97  6108.3  696.71
#Mann= 8 ,-1 , 0
  4289.8     .05       0  4734.2     .12       0  4762.8    .033       0
  4766.8     .12       0  4901.5     .05       0  5036.5     .12       0
  5058.8     .05       0  5963.8     .12       0
Bank Sta=4762.8,4766.8
XS Rating Curve= 0 ,0
Exp/Cntr=0.3,0.1

Type RM Length L Ch R = 1 ,29401   ,388,388,388
BEGIN DESCRIPTION:
Whites Branch 59.0
END DESCRIPTION:
XS GIS Cut Line= 3
        2373329.        7083310.        2373079.        7083060.
      2372228.98      7082509.99
#Sta/Elev= 30
  4650.7  662.98  4707.3   660.2    4778  658.49  4804.8  656.65  4820.4  654.79
  4891.1  650.14  4974.5  648.95  4990.1  649.95  5007.2   649.9  5009.8   646.8
  5010.1   646.3  5013.8   646.8    5027  648.21    5040  650.61  5063.3  648.68
  5120.7  648.77  5220.3  651.23  5250.6   653.1  5271.7  652.37  5344.3  653.58
  5373.5   653.2    5589  654.52  5806.6  656.16  5879.2  657.44  5966.9  660.44
  5972.8  660.13  5980.9  661.11  5993.9  666.77  6003.1  669.65  6016.7   670.3
#Mann= 5 ,-1 , 0
  4650.7     .05       0  4804.8     .12       0  4974.5     .05       0
  5009.8    .033       0  5013.8     .05       0
Bank Sta=5009.8,5013.8
XS Rating Curve= 0 ,0
Exp/Cntr=0.3,0.1

Type RM Length L Ch R = 1 ,29013   ,554,554,554
BEGIN DESCRIPTION:
Whites Branch 58.0
END DESCRIPTION:
XS GIS Cut Line= 3
      2373644.82      7083248.11      2373279.03      7082871.38
      2372226.44      7082298.47
#Sta/Elev= 30
  4474.9  659.86  4520.1  660.03  4553.5  658.89  4782.7  655.27  4866.6   652.8
  4932.3  647.81  4979.8  647.85  4986.9  646.33  4991.9  643.63  4992.2  643.13
  4995.9  643.63  4997.5  646.14  5002.9  646.14  5015.2  648.11  5037.1   647.6
  5062.6  648.29  5125.3  648.48  5156.7  647.14  5178.6  647.22  5391.3  649.83
  5466.8  652.23  5494.9  650.74  5538.6  650.94  5620.2  652.08  5658.2  653.72
  5842.5  653.96  6018.2  656.77    6078  659.25  6129.4  662.64  6198.4  666.15
#Mann= 8 ,-1 , 0
  4474.9     .05       0  4553.5    .075       0  4782.7     .05       0
  4932.3     .12       0  4991.9     .07       0  4995.9     .12       0
  5062.6     .05       0  6129.4     .12       0
Bank Sta=4991.9,4995.9
XS Rating Curve= 0 ,0
Exp/Cntr=0.3,0.1

Type RM Length L Ch R = 1 ,28459   ,785,785,785
BEGIN DESCRIPTION:
Mapping XS c2ee8ad8
END DESCRIPTION:
XS GIS Cut Line= 4
      2373966.21      7082375.41      2373343.86      7082333.74
       2372994.9      7082315.51       2372212.5      7082063.38
#Sta/Elev= 30
  4361.7  670.86  4365.9  669.96  4393.6  669.04  4492.7  664.52  4559.4  662.85
  4589.4  660.38  4619.5  660.53  4665.9  658.01    4716  657.02  4948.9   650.5
  4960.2  649.58    4966  647.54    4971  647.13  4983.2  641.94  4983.6  641.44
  4987.5  641.94  5000.3   644.4  5010.3  645.31  5100.5  644.25  5174.7  644.59
  5270.7   646.6  5383.1  646.06  5469.7  647.83  5551.2  651.07  5763.5  653.15
  5827.6  654.78  5923.8  657.87  6013.5  662.52  6107.9  668.72  6156.9  672.47
#Mann= 9 ,-1 , 0
  4361.7     .12       0  4393.6     .05       0  4492.7     .12       0
    4716     .05       0  4948.9     .12       0  4983.2     .07       0
  4987.5     .12       0  5174.7     .05       0  6107.9     .12       0
Bank Sta=4983.2,4987.5
XS Rating Curve= 0 ,0
Exp/Cntr=0.3,0.1

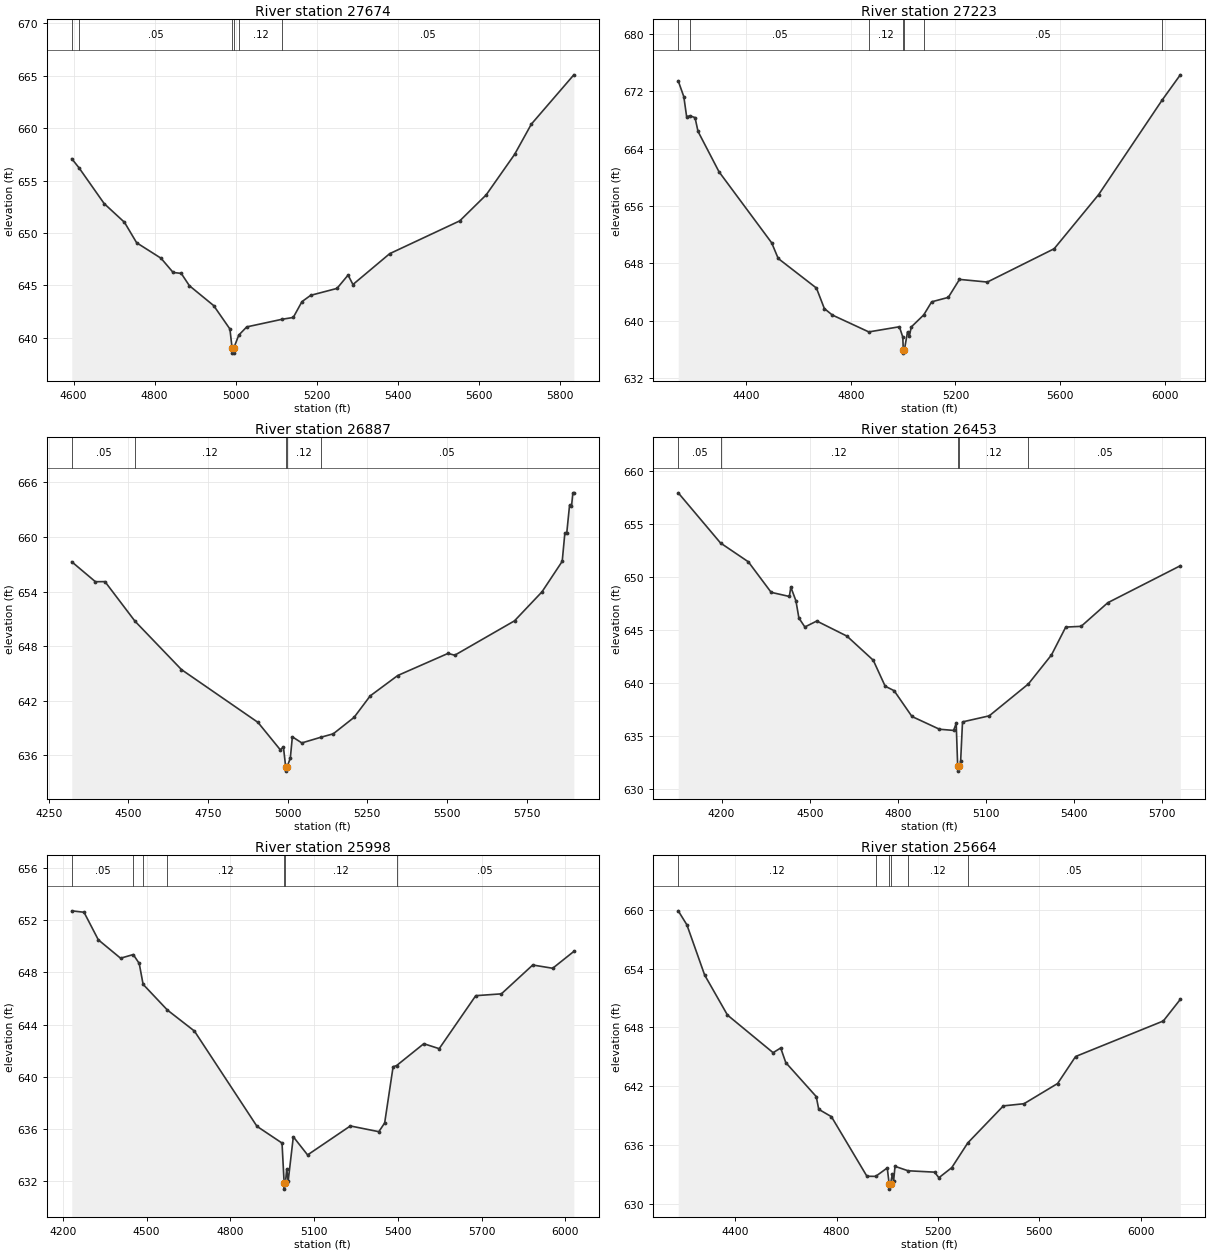
Type RM Length L Ch R = 1 ,27674   ,451,451,451
BEGIN DESCRIPTION:
Whites Branch 55.0
END DESCRIPTION:
XS GIS Cut Line= 3
      2373529.05        7081710.        2373129.        7081710.
        2372329.        7081960.
#Sta/Elev= 30
  4595.6  657.08  4613.4  656.22  4675.6   652.8  4725.6  651.02  4755.6  649.07
  4815.6   647.6  4845.6  646.24  4865.6  646.15  4885.6  644.98  4945.6  643.08
  4985.6  640.85  4990.9  639.05  4991.3  638.55  4994.9  638.55  4995.3  639.05
  5007.5  640.27  5027.1  641.05  5114.6  641.78  5141.8  641.95  5163.3  643.46
  5184.8  644.06  5249.7  644.72    5277  645.99    5289  645.09  5379.6  648.03
  5552.5  651.16  5617.5  653.63  5687.6  657.49    5729  660.38  5833.8  665.08
#Mann= 6 ,-1 , 0
  4595.6     .12       0  4613.4     .05       0  4990.9    .033       0
  4995.3     .05       0  5007.5     .12       0  5114.6     .05       0
Bank Sta=4990.9,4995.3
XS Rating Curve= 0 ,0
Exp/Cntr=0.3,0.1

Type RM Length L Ch R = 1 ,27223   ,336,336,336
BEGIN DESCRIPTION:
Whites Branch 54.0
END DESCRIPTION:
XS GIS Cut Line= 3
      2373778.98      7081609.99        2372979.        7081310.
        2372179.        7082010.
#Sta/Elev= 30
  4141.2  673.47  4162.5  671.27  4173.2   668.5  4186.9  668.59  4205.3  668.35
  4216.8  666.42  4296.9  660.79  4498.1  650.87    4523  648.69    4669  644.56
  4699.2   641.7  4729.5   640.8    4869  638.44  4985.8  639.16  4998.9   637.7
  5000.5  635.98  5000.9  635.48    5005  635.98  5016.9  638.45  5023.6  637.82
  5031.2  639.13  5078.9  640.82    5109  642.64  5172.6  643.26  5215.3  645.77
  5321.6   645.4  5576.9  650.05  5746.8  657.61  5988.7  670.77  6058.6  674.32
#Mann= 7 ,-1 , 0
  4141.2     .12       0  4186.9     .05       0    4869     .12       0
  5000.5     .07       0    5005     .12       0  5078.9     .05       0
  5988.7     .12       0
Bank Sta=5000.5,5005
XS Rating Curve= 0 ,0
Exp/Cntr=0.3,0.1

Type RM Length L Ch R = 1 ,26887   ,434,434,434
BEGIN DESCRIPTION:
Whites Branch 53.0
END DESCRIPTION:
XS GIS Cut Line= 3
      2373593.23      7080986.39       2372915.8      7080996.26
      2372179.02      7081509.99
#Sta/Elev= 30
  4322.5  657.27  4396.7  655.08  4426.7  655.09  4520.9  650.74  4666.8  645.42
  4906.8  639.62  4976.8  636.61  4986.8  636.91  4993.7  634.76  4994.1  634.26
  4998.2  634.76  5008.3  635.65  5014.8  638.03  5044.5  637.36  5103.9  637.98
  5143.1  638.36  5208.5  640.17  5259.1  642.53  5345.5  644.77  5503.4   647.2
  5524.4     647    5712  650.78  5798.3  653.97  5861.7  657.32  5869.9  660.39
    5876  660.45  5884.7  663.47  5890.8  663.35  5895.2  664.85  5898.2  664.85
#Mann= 5 ,-1 , 0
  4322.5     .05       0  4520.9     .12       0  4993.7     .07       0
  4998.2     .12       0  5103.9     .05       0
Bank Sta=4993.7,4998.2
XS Rating Curve= 0 ,0
Exp/Cntr=0.3,0.1

Type RM Length L Ch R = 1 ,26453   ,455,455,455
BEGIN DESCRIPTION:
Mapping XS 23291738
END DESCRIPTION:
XS GIS Cut Line= 3
      2373614.65       7080935.3      2372671.98      7080784.26
       2371924.6      7080888.43
#Sta/Elev= 30
  4052.3   657.9  4196.3  653.18    4291  651.41  4368.6  648.54  4430.6  648.15
  4435.6  649.03    4453  647.74  4463.1  646.12  4483.4  645.28  4523.9  645.84
  4626.7  644.42  4716.3  642.15  4756.8  639.71  4787.2  639.29    4848  636.86
  4941.7  635.66  4989.8  635.55  4998.6  636.21  5003.6  632.22  5004.1  631.72
  5008.4  632.22  5013.7  632.63  5020.1  636.35    5111  636.92  5244.3  639.92
    5323  642.65  5371.5  645.27    5424  645.34  5514.6  647.56  5761.6  651.04
#Mann= 5 ,-1 , 0
  4052.3     .05       0  4196.3     .12       0  5003.6     .07       0
  5008.4     .12       0  5244.3     .05       0
Bank Sta=5003.6,5008.4
XS Rating Curve= 0 ,0
Exp/Cntr=0.3,0.1

Type RM Length L Ch R = 1 ,25998   ,334,334,334
BEGIN DESCRIPTION:
Mapping XS c7f3f807
END DESCRIPTION:
XS GIS Cut Line= 3
      2373476.68      7080753.02      2372833.44       7080370.2
      2371804.81      7080583.74
#Sta/Elev= 30
  4231.6  652.72  4275.5  652.61  4326.7   650.5  4406.5  649.09  4451.9  649.37
  4473.3  648.69  4487.2  647.09  4574.2  645.12  4671.1  643.51  4895.3  636.21
    4985  634.93  4992.5   631.9    4993   631.4  4997.3   631.9  5001.9  632.95
    5007  632.01  5025.5  635.41  5076.6  634.02  5229.8  636.24  5331.9   635.8
  5352.8  636.47    5383  640.77  5395.8  640.87    5493  642.54  5548.2  642.16
  5679.2  646.22  5771.1  646.36  5883.4  648.57  5954.9  648.32  6030.7  649.61
#Mann= 7 ,-1 , 0
  4231.6     .05       0  4451.9     .12       0  4487.2     .05       0
  4574.2     .12       0  4992.5     .07       0  4997.3     .12       0
  5395.8     .05       0
Bank Sta=4992.5,4997.3
XS Rating Curve= 0 ,0
Exp/Cntr=0.3,0.1

Type RM Length L Ch R = 1 ,25664   ,404,404,404
BEGIN DESCRIPTION:
Mapping XS 996a8d75
END DESCRIPTION:
XS GIS Cut Line= 3
       2373703.2      7080078.53      2372893.34       7080057.7
      2371743.16      7080276.29
#Sta/Elev= 30
  4175.3  659.88  4209.5  658.45  4279.5  653.34  4369.6  649.26  4549.6  645.43
  4579.6  645.91  4599.6  644.42  4719.7  640.96  4729.7  639.66  4779.7  638.91
  4919.8  632.84  4954.3  632.83    5000  633.69  5007.6  632.03  5008.3  631.53
  5012.8  632.03  5019.9  633.04    5025  632.35  5030.6  633.85  5082.1   633.4
  5186.8  633.26  5203.6  632.69  5254.5  633.72  5317.7  636.24  5458.1  640.01
  5539.5  640.23  5672.1  642.29  5743.1  645.04  6089.2  648.66  6156.2  650.86
#Mann= 6 ,-1 , 0
  4175.3     .12       0  4954.3      .1       0  5007.6     .07       0
  5012.8      .1       0  5082.1     .12       0  5317.7     .05       0
Bank Sta=5007.6,5012.8
XS Rating Curve= 0 ,0
Exp/Cntr=0.3,0.1