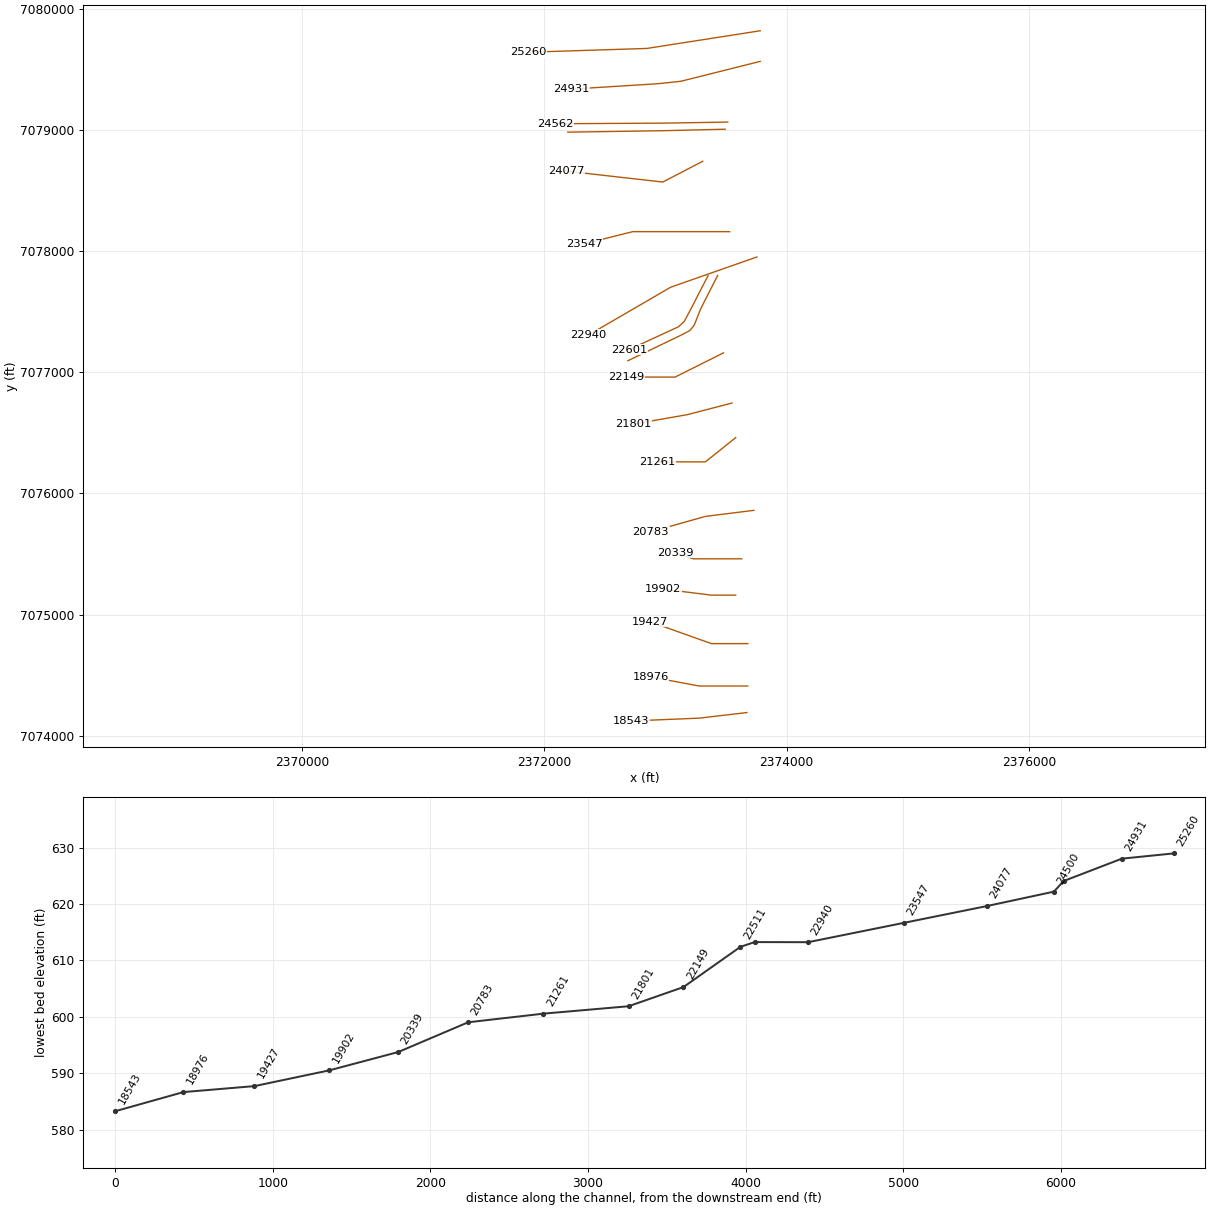
HEC-RAS study Whites Branch.prj: Whites Branch Base Level Engineering

--- Whites Branch.g01 (geometry) --- (continued)

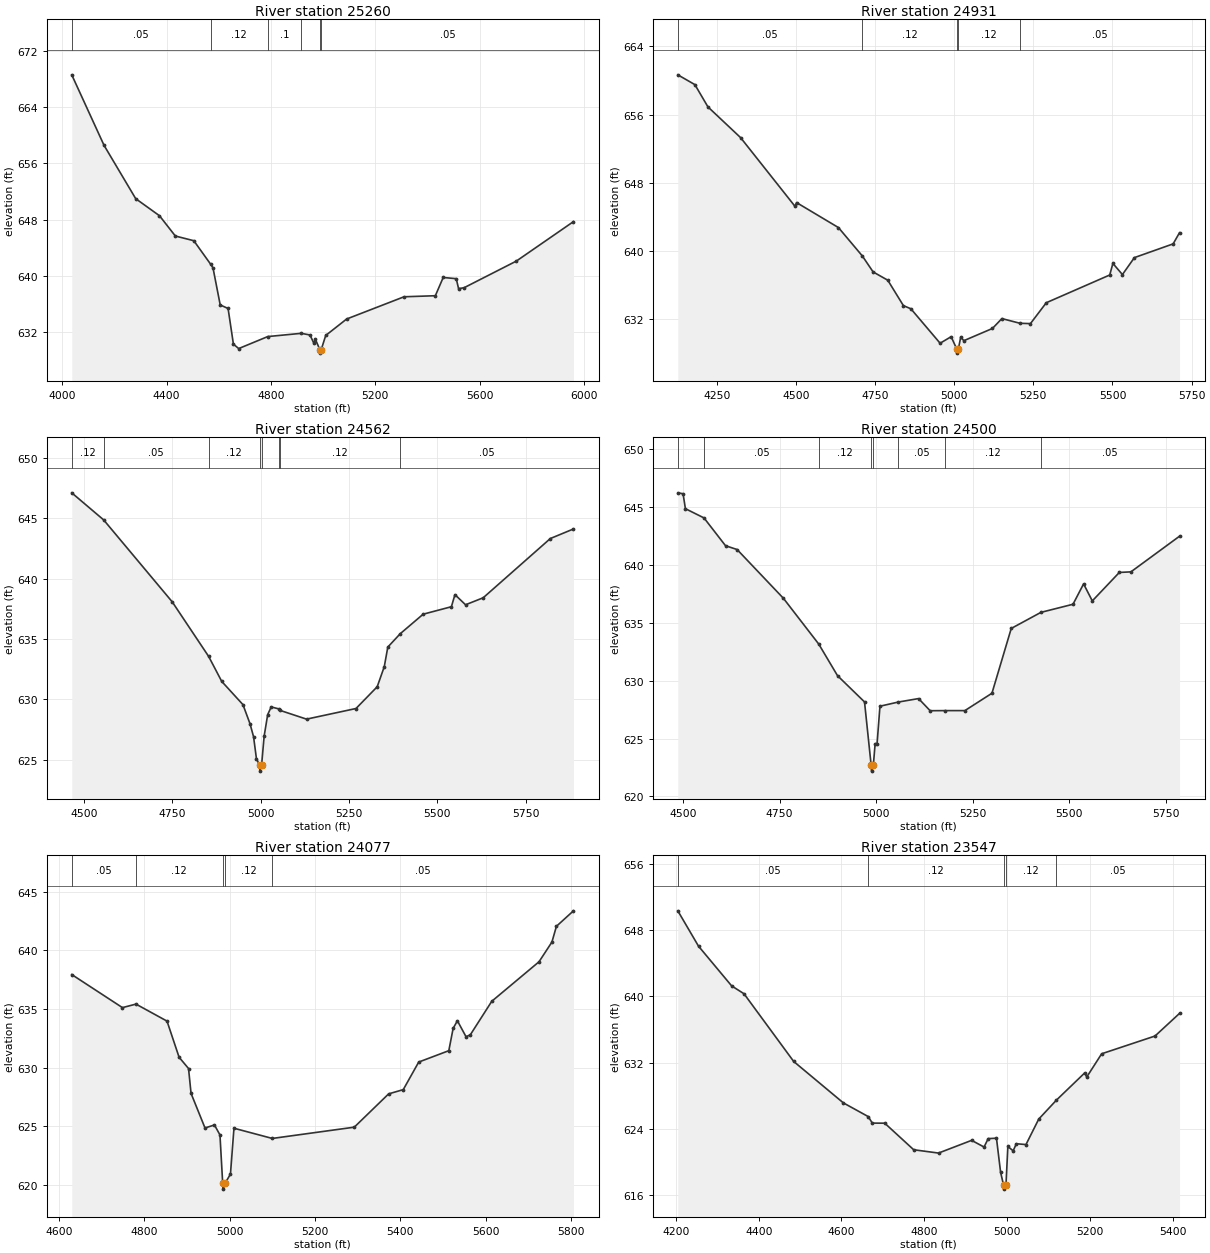
Type RM Length L Ch R = 1 ,25260   ,329,329,329
BEGIN DESCRIPTION:
Mapping XS 56855ac3
END DESCRIPTION:
XS GIS Cut Line= 3
      2373781.32      7079818.11      2372846.46      7079672.29
      2371869.92      7079641.04
#Sta/Elev= 30
  4036.3  668.62  4160.1  658.57  4281.5  650.97  4372.6  648.54  4433.4  645.65
  4504.2  644.98  4568.5  641.64  4577.8   641.1  4605.4  635.83  4635.6  635.32
    4656  630.24  4676.3  629.61  4787.7  631.32  4915.9  631.78  4949.5  631.55
  4964.8  630.34  4969.8  630.97  4987.3  629.46    4988  628.96  4992.6  629.46
  5009.9  631.48    5090  633.82  5310.1  636.99  5430.1  637.14  5460.2  639.74
  5510.2  639.57  5519.1  638.15  5540.2  638.28  5740.3  642.07  5959.5   647.7
#Mann= 6 ,-1 , 0
  4036.3     .05       0  4568.5     .12       0  4787.7      .1       0
  4915.9     .05       0  4987.3    .033       0  4992.6     .05       0
Bank Sta=4987.3,4992.6
XS Rating Curve= 0 ,0
Exp/Cntr=0.3,0.1

Type RM Length L Ch R = 1 ,24931   ,369,369,369
BEGIN DESCRIPTION:
Mapping XS 2fc16df6
END DESCRIPTION:
XS GIS Cut Line= 4
      2373781.35      7079565.51      2373127.71      7079401.45
       2372932.4      7079380.62      2372218.91      7079336.35
#Sta/Elev= 30
  4126.6  660.66  4180.6  659.51  4221.8   656.9  4324.9   653.3  4496.7  645.25
  4501.9  645.68  4634.2  642.75  4709.5  639.43  4743.7  637.55    4790  636.58
  4839.4   633.6    4863  633.23  4955.4  629.19  4990.3  629.96  5007.6  628.53
  5008.4  628.03  5013.2  628.53  5020.4   629.9  5030.4  629.49  5120.6  630.92
  5150.6  632.08  5207.7  631.53  5240.8  631.49  5290.9  633.94  5491.3  637.19
  5501.3  638.55  5531.4  637.24  5569.3  639.23  5691.7  640.84  5711.8  642.15
#Mann= 5 ,-1 , 0
  4126.6     .05       0  4709.5     .12       0  5007.6     .07       0
  5013.2     .12       0  5207.7     .05       0
Bank Sta=5007.6,5013.2
XS Rating Curve= 0 ,0
Exp/Cntr=0.3,0.1

Type RM Length L Ch R = 1 ,24562   ,62,62,62
BEGIN DESCRIPTION:
Mapping XS bcfb515a
END DESCRIPTION:
XS GIS Cut Line= 3
      2373513.41      7079064.52      2372987.35      7079055.84
       2372093.6      7079050.63
#Sta/Elev= 30
  4465.6  647.09  4555.9  644.85    4750  638.07    4853  633.56  4890.1  631.49
  4950.1  629.57  4970.1  627.99  4980.1  626.92  4988.4  625.08  4997.3  624.57
  4998.1  624.07  5002.9  624.57  5010.1  626.96  5020.1  628.74  5030.1  629.38
  5051.3  629.22  5053.6  629.11  5130.1  628.37  5270.1  629.25  5330.1  631.05
  5350.1  632.71  5360.1  634.33  5395.4  635.44  5460.1  637.05  5540.1  637.67
  5550.1  638.67  5580.1  637.83  5630.1  638.41  5820.1  643.31  5885.5   644.1
#Mann= 8 ,-1 , 0
  4465.6     .12       0  4555.9     .05       0    4853     .12       0
  4997.3     .07       0  5002.9     .12       0  5051.3     .05       0
  5053.6     .12       0  5395.4     .05       0
Bank Sta=4997.3,5002.9
XS Rating Curve= 0 ,0
Exp/Cntr=0.3,0.1

Type RM Length L Ch R = 1 ,24500   ,423,423,423
BEGIN DESCRIPTION:
Whites Branch 48.0
END DESCRIPTION:
XS GIS Cut Line= 3
      2373492.58      7079005.49      2372979.02      7078993.34
      2372193.11       7078981.2
#Sta/Elev= 30
  4486.3  646.24  4499.9  646.16    4506  644.87  4554.2  644.07  4609.9  641.67
  4639.9  641.34    4760  637.12  4851.4  633.17    4900  630.44    4970  628.17
  4987.2  622.69  4988.1  622.19  4992.8  622.69  4997.5  624.56  5002.5  624.56
    5010   627.8  5057.6  628.16    5110  628.46    5140  627.41  5177.4  627.42
    5230  627.42  5300.1  628.92  5350.1  634.52    5427  635.91  5510.1  636.61
  5537.5  638.37  5560.1   636.9  5630.1  639.36  5660.1  639.41    5786  642.49
#Mann= 8 ,-1 , 0
  4486.3     .12       0  4554.2     .05       0  4851.4     .12       0
  4987.2     .07       0  4992.8     .12       0  5057.6     .05       0
  5177.4     .12       0    5427     .05       0
Bank Sta=4987.2,4992.8
XS Rating Curve= 0 ,0
Exp/Cntr=0.3,0.1

Type RM Length L Ch R = 1 ,24077   ,530,530,530
BEGIN DESCRIPTION:
Whites Branch 47.0
END DESCRIPTION:
XS GIS Cut Line= 3
      2373306.95      7078740.97       2372977.1      7078569.54
      2372178.95      7078660.01
#Sta/Elev= 30
  4630.5  637.94  4749.2  635.12  4780.9  635.42  4853.6  633.97  4881.9  630.89
    4904  629.93  4909.9  627.81  4942.6  624.86  4964.7  625.12  4977.6  624.27
    4984  620.15  4984.8  619.65  4989.6  620.15  5002.2  620.93  5010.4  624.84
  5100.2  623.97  5292.2  624.93  5372.7  627.77  5406.9  628.13  5443.1  630.48
  5513.6  631.45  5523.7  633.35  5533.7     634  5553.9  632.64  5563.9   632.8
  5614.2  635.66  5724.9  639.03  5755.1  640.71  5765.6  642.05  5805.5  643.37
#Mann= 5 ,-1 , 0
  4630.5     .05       0  4780.9     .12       0    4984     .07       0
  4989.6     .12       0  5100.2     .05       0
Bank Sta=4984,4989.6
XS Rating Curve= 0 ,0
Exp/Cntr=0.3,0.1

Type RM Length L Ch R = 1 ,23547   ,607,607,607
BEGIN DESCRIPTION:
Whites Branch 46.0
END DESCRIPTION:
XS GIS Cut Line= 3
      2373529.02        7078160.        2372729.        7078160.
      2372329.03      7078060.01
#Sta/Elev= 30
  4204.5  650.38  4254.5   646.1  4334.5  641.29  4364.5  640.33  4484.5  632.13
  4604.5  627.11  4664.6  625.45  4674.5  624.66  4704.5  624.65  4774.5  621.43
  4834.5  621.03  4914.5  622.57  4944.5  621.76  4954.5  622.78  4974.5  622.83
  4984.5   618.7  4991.6  617.16  4992.5  616.66  4997.5  617.16    5002  621.83
  5014.8   621.3  5022.6  622.16  5045.8  622.06  5076.7  625.15  5119.5  627.45
  5187.5  630.73  5192.6  630.24  5228.7  633.06  5357.6  635.21  5416.8  637.95
#Mann= 5 ,-1 , 0
  4204.5     .05       0  4664.6     .12       0  4991.6     .07       0
  4997.5     .12       0  5119.5     .05       0
Bank Sta=4991.6,4997.5
XS Rating Curve= 0 ,0
Exp/Cntr=0.3,0.1

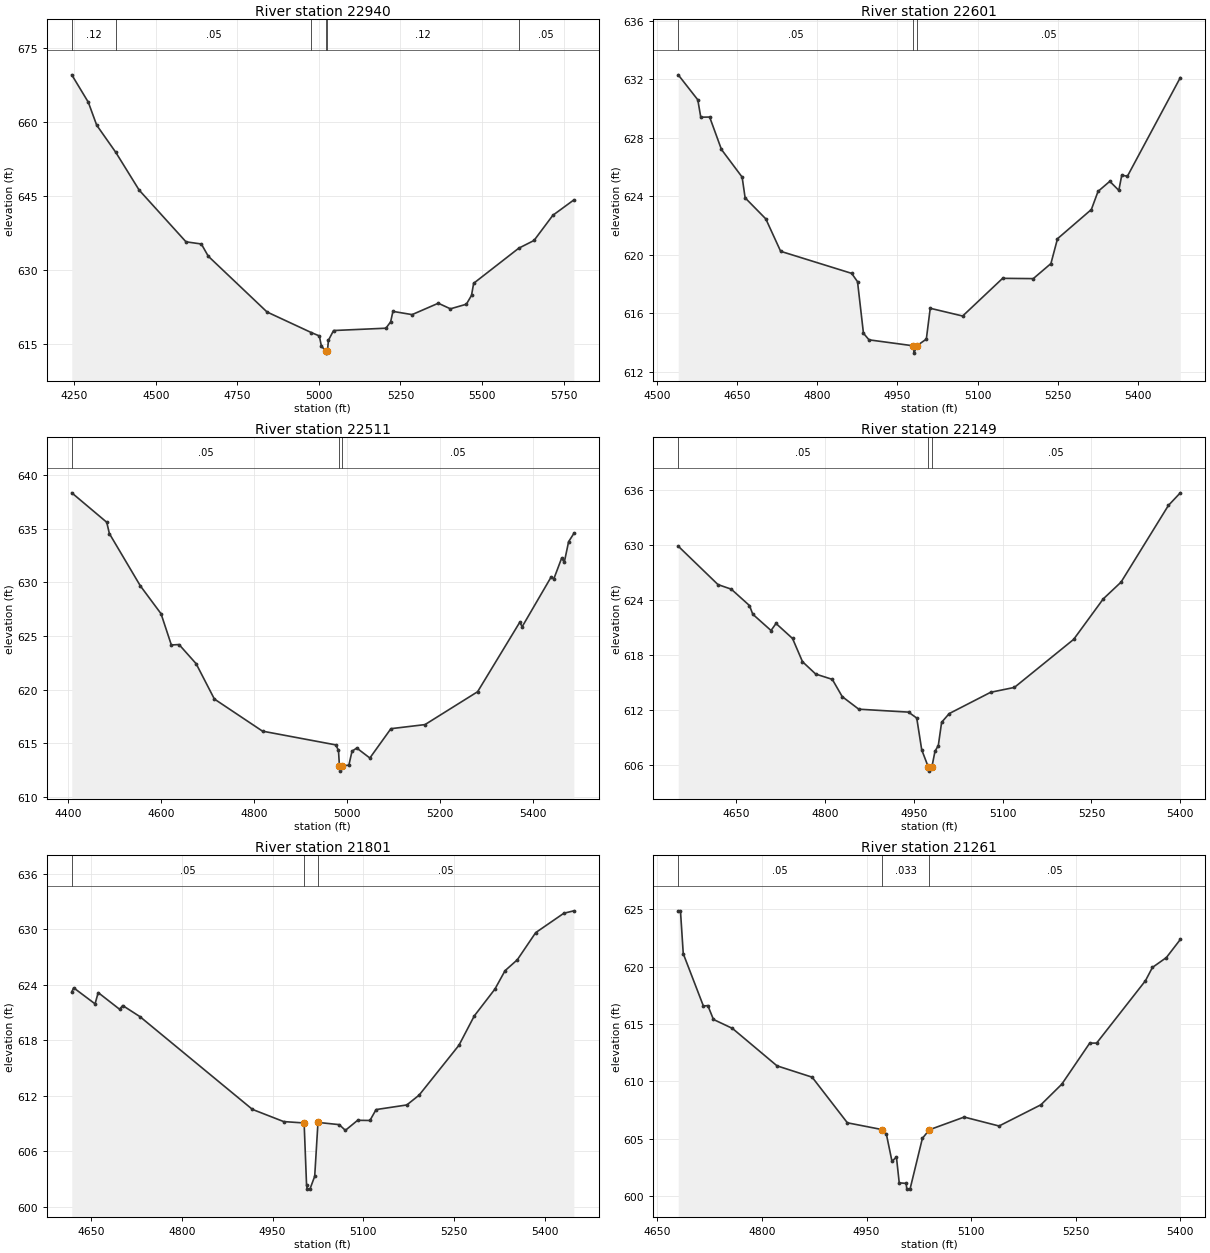
Type RM Length L Ch R = 1 ,22940   ,339,339,339
BEGIN DESCRIPTION:
Mapping XS 138f674a
END DESCRIPTION:
XS GIS Cut Line= 3
      2373753.97      7077951.03      2373042.21      7077701.48
      2372363.45      7077306.81
#Sta/Elev= 30
  4242.2  669.52  4292.9  663.98  4318.6  659.34  4377.1  653.85  4448.8  646.21
  4592.4  635.75  4639.5  635.31  4660.7  632.84  4840.9  621.56  4976.6   617.4
  5001.2  616.72  5007.6  614.64  5020.3  613.74  5021.3  613.24  5026.2  613.74
  5029.2  615.85  5044.9  617.81  5205.4  618.28  5219.9  619.57  5226.9  621.68
  5285.7  621.03    5366  623.33  5403.2   622.2    5452  623.13  5467.8  624.91
  5474.4  627.36  5612.7  634.46  5659.5  636.02  5717.3  641.12  5781.6  644.22
#Mann= 6 ,-1 , 0
  4242.2     .12       0  4377.1     .05       0  4976.6     .12       0
  5020.3     .07       0  5026.2     .12       0  5612.7     .05       0
Bank Sta=5020.3,5026.2
XS Rating Curve= 0 ,0
Exp/Cntr=0.3,0.1

Type RM Length L Ch R = 1 ,22601   ,90,90,90
BEGIN DESCRIPTION:
Mapping XS 42cff239
END DESCRIPTION:
XS GIS Cut Line= 5
      2373351.02      7077797.11      2373199.11      7077502.84
      2373154.84      7077420.38      2373107.09      7077375.24
      2372699.14      7077186.88
#Sta/Elev= 30
  4539.7  632.31  4576.3   630.6  4581.9  629.41  4598.5  629.42  4620.6   627.2
  4659.3  625.31  4664.9  623.89  4703.6  622.45  4731.4  620.23  4864.3  618.72
  4875.3  618.15  4886.4  614.62  4896.8  614.17  4979.9  613.76    4981  613.26
  4986.3  613.76  5004.1  614.22  5011.4  616.33  5072.1   615.8  5146.9  618.38
  5204.3  618.36  5237.3  619.39  5249.6  621.09    5313  623.09  5325.5  624.33
  5347.5  625.02  5364.4   624.4  5369.9  625.44  5380.5  625.37  5479.5  632.12
#Mann= 3 ,-1 , 0
  4539.7     .05       0  4979.9     .04       0  4986.3     .05       0
Bank Sta=4979.9,4986.3
XS Rating Curve= 0 ,0
Exp/Cntr=0.3,0.1

Type RM Length L Ch R = 1 ,22511   ,362,362,362
BEGIN DESCRIPTION:
Mapping XS 2b6c4410
END DESCRIPTION:
XS GIS Cut Line= 6
      2373430.02      7077798.43      2373290.69      7077524.98
        2373236.      7077386.96      2373200.84      7077343.99
      2373137.04      7077310.13      2372688.84      7077094.47
#Sta/Elev= 30
    4408  638.32  4483.3  635.58  4488.9  634.53  4555.6  629.66  4600.1  627.07
  4622.3  624.16  4638.9   624.2  4675.6  622.42  4714.9  619.13  4818.5  616.14
  4976.3  614.86    4982  614.34    4984  612.92    4985  612.42  4990.4  612.92
  5004.3  612.97  5011.1  614.27  5021.3  614.57  5049.5  613.64  5094.8  616.37
  5168.2  616.75  5281.4  619.81  5371.9  626.26  5377.4  625.87  5439.8   630.5
  5445.3   630.3  5462.4  632.26  5467.9  631.85  5477.2  633.77  5488.5  634.54
#Mann= 3 ,-1 , 0
    4408     .05       0    4984     .04       0  4990.4     .05       0
Bank Sta=4984,4990.4
XS Rating Curve= 0 ,0
Exp/Cntr=0.3,0.1

Type RM Length L Ch R = 1 ,22149   ,348,348,348
BEGIN DESCRIPTION:
Whites Branch 43.0
END DESCRIPTION:
XS GIS Cut Line= 3
      2373479.04      7077160.02        2373079.        7076960.
      2372678.96        7076960.
#Sta/Elev= 30
  4552.7  629.88  4619.8  625.68  4642.2  625.18  4672.9  623.39  4678.5  622.44
  4709.3  620.66  4717.7  621.43  4745.6  619.79  4762.4  617.25  4784.7   615.9
  4812.7  615.32  4829.5  613.43  4857.4  612.06  4941.3  611.74  4955.2  611.09
  4963.6  607.62  4974.4  605.79  4975.4  605.29  4980.9  605.79    4986  607.46
  4991.6  608.09  4997.2  610.63    5010  611.58    5080  613.91    5120  614.44
    5220  619.69    5270  624.12    5300  625.95    5380  634.34    5400  635.71
#Mann= 3 ,-1 , 0
  4552.7     .05       0  4974.4     .04       0  4980.9     .05       0
Bank Sta=4974.4,4980.9
XS Rating Curve= 0 ,0
Exp/Cntr=0.3,0.1

Type RM Length L Ch R = 1 ,21801   ,540,540,540
BEGIN DESCRIPTION:
Whites Branch 42.0
END DESCRIPTION:
XS GIS Cut Line= 3
       2373548.1      7076745.51      2373178.39      7076649.38
      2372736.87      7076572.32
#Sta/Elev= 30
    4618  623.24  4621.1  623.69  4656.5  621.95  4661.7  623.17    4697  621.37
  4702.2  621.77  4730.7  620.57  4916.7  610.53  4968.4  609.21  5002.2  609.06
  5006.2   602.4  5007.3   601.9  5011.8   601.9  5019.7  603.29  5025.1  609.12
  5060.3  608.88  5070.4  608.26  5090.7  609.35    5111  609.33  5121.2  610.51
    5172  611.01  5192.3  612.07  5258.2  617.47  5283.6  620.65  5317.7  623.55
  5334.4  625.54  5354.7  626.72  5385.1  629.66  5431.7  631.76  5448.2  632.02
#Mann= 3 ,-1 , 0
    4618     .05       0  5002.2     .04       0  5025.1     .05       0
Bank Sta=5002.2,5025.1
XS Rating Curve= 0 ,0
Exp/Cntr=0.3,0.1

Type RM Length L Ch R = 1 ,21261   ,478,478,478
BEGIN DESCRIPTION:
Whites Branch 41.0
END DESCRIPTION:
XS GIS Cut Line= 3
      2373579.04      7076460.03        2373329.        7076260.
        2372929.        7076260.
#Sta/Elev= 30
  4679.9  624.88  4683.1  624.88  4687.1  621.14    4716  616.57  4722.4  616.61
  4730.4   615.4  4757.6  614.62  4821.6  611.35    4872  610.36  4922.5  606.38
  4972.1  605.79  4978.5  605.38  4986.5  603.02  4992.9  603.39  4996.9  601.14
  5006.8  601.09  5007.8  600.59  5012.4  600.59  5030.1  605.02  5040.1  605.77
  5090.1  606.88  5140.1   606.1  5200.1  607.95  5230.1  609.75  5270.1  613.33
  5280.1  613.34  5350.1  618.78  5360.1  619.94  5380.1   620.8  5400.1  622.38
#Mann= 3 ,-1 , 0
  4679.9     .05       0  4972.1    .033       0  5040.1     .05       0
Bank Sta=4972.1,5040.1
XS Rating Curve= 0 ,0
Exp/Cntr=0.3,0.1

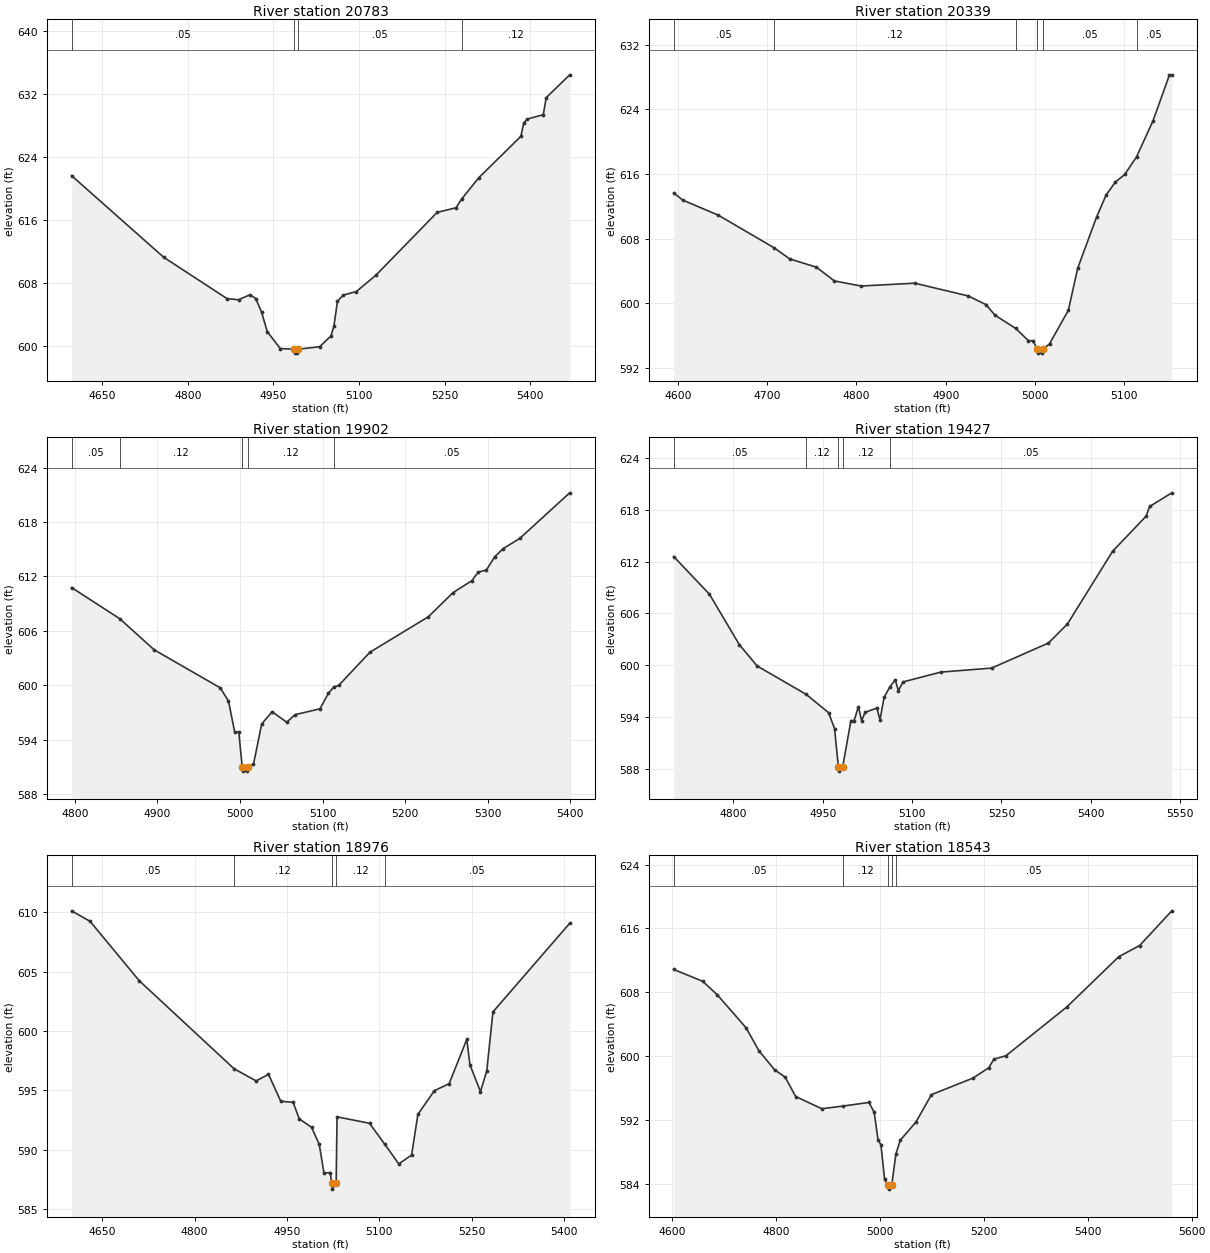
Type RM Length L Ch R = 1 ,20783   ,444,444,444
BEGIN DESCRIPTION:
Whites Branch 40.0
END DESCRIPTION:
XS GIS Cut Line= 3
      2373729.03        7075860.        2373329.        7075810.
      2372877.57      7075683.02
#Sta/Elev= 30
  4596.7  621.61    4758  611.24  4868.8  605.99    4889  605.84  4909.1  606.48
  4919.2  605.99  4929.3  604.28  4939.4  601.78  4962.1  599.64  4986.3  599.56
  4987.4  599.06  4992.2  599.06  4993.3  599.56    5031  599.87  5050.9  601.25
  5056.1  602.52  5062.2  605.66  5072.6  606.44  5095.4  606.89  5129.4  608.95
  5236.7  616.94  5269.9  617.53  5279.5  618.63    5310  621.37  5383.3   626.6
  5388.5  628.32  5394.6   628.8  5422.6  629.36  5427.7  631.52  5468.8  634.42
#Mann= 4 ,-1 , 0
  4596.7     .05       0  4986.3    .033       0  4993.3     .05       0
  5279.5     .12       0
Bank Sta=4986.3,4993.3
XS Rating Curve= 0 ,0
Exp/Cntr=0.3,0.1

Type RM Length L Ch R = 1 ,20339   ,437,437,437
BEGIN DESCRIPTION:
Whites Branch 39.0
END DESCRIPTION:
XS GIS Cut Line= 3
      2373629.03        7075460.        2373229.        7075460.
      2373079.04      7075509.99
#Sta/Elev= 30
  4595.2  613.66  4605.2  612.77  4645.2  610.89  4707.7  606.85  4725.2  605.47
  4755.2  604.44  4775.2  602.74  4805.2  602.11  4865.2  602.46  4925.2  600.88
  4945.2   599.8  4955.2  598.49  4978.2  596.87  4992.7  595.33  4997.9  595.33
  5002.3  594.29  5003.4  593.79  5008.2  593.79  5009.3  594.29  5016.3  594.94
  5037.4   599.1  5047.9  604.32    5069  610.65  5079.6  613.37  5090.1     615
  5100.6  615.94  5113.8  618.12  5132.3   622.6  5150.7  628.29  5153.3  628.29
#Mann= 6 ,-1 , 0
  4595.2     .05       0  4707.7     .12       0  4978.2     .05       0
  5002.3    .033       0  5009.3     .05       0  5113.8     .05       0
Bank Sta=5002.3,5009.3
XS Rating Curve= 0 ,0
Exp/Cntr=0.3,0.1

Type RM Length L Ch R = 1 ,19902   ,475,475,475
BEGIN DESCRIPTION:
Whites Branch 38.0
END DESCRIPTION:
XS GIS Cut Line= 3
        2373579.        7075160.        2373379.        7075160.
      2372979.01        7075210.
#Sta/Elev= 30
    4796  610.78  4854.3  607.35    4896  603.92    4976  599.73    4986  598.27
  4993.5  594.86  4998.5  594.86  5002.5  591.05  5003.6  590.55  5008.5  590.55
  5009.6  591.05  5016.2  591.29  5026.2  595.75  5038.8  597.09  5056.5  595.94
  5066.5  596.77  5096.8  597.42  5106.9  599.12  5113.5  599.83  5119.4  599.99
  5157.2  603.65  5227.8  607.55    5258  610.23  5280.7  611.54  5288.3  612.48
  5298.3  612.72  5308.4  614.18  5318.5  615.07  5338.6  616.19  5399.1  621.22
#Mann= 5 ,-1 , 0
    4796     .05       0  4854.3     .12       0  5002.5     .07       0
  5009.6     .12       0  5113.5     .05       0
Bank Sta=5002.5,5009.6
XS Rating Curve= 0 ,0
Exp/Cntr=0.3,0.1

Type RM Length L Ch R = 1 ,19427   ,451,451,451
BEGIN DESCRIPTION:
Whites Branch 37.0
END DESCRIPTION:
XS GIS Cut Line= 3
      2373679.01        7074760.        2373379.        7074760.
      2372873.99      7074939.57
#Sta/Elev= 30
    4700  612.59    4760  608.23    4810  602.41    4840  599.93  4922.4  596.64
    4960  594.52    4970  592.68  4976.4  588.26  4977.6  587.76  4983.6  588.26
  4997.5   593.6  5002.7   593.6  5010.1  595.22  5015.4  593.59  5021.2  594.56
    5041  595.06  5046.3  593.71  5053.1  596.28  5062.9  597.52  5071.8  598.32
  5077.1  597.07  5084.9  598.08  5148.6  599.22  5233.5  599.68    5329  602.58
  5360.9  604.79  5436.6  613.19    5493  617.27  5498.8  618.38    5536  619.96
#Mann= 5 ,-1 , 0
    4700     .05       0  4922.4     .12       0  4976.4     .07       0
  4983.6     .12       0  5062.9     .05       0
Bank Sta=4976.4,4983.6
XS Rating Curve= 0 ,0
Exp/Cntr=0.3,0.1

Type RM Length L Ch R = 1 ,18976   ,433,433,433
BEGIN DESCRIPTION:
Whites Branch 36.0
END DESCRIPTION:
XS GIS Cut Line= 3
        2373679.        7074410.        2373279.        7074410.
      2372876.44      7074485.05
#Sta/Elev= 30
    4600  610.11    4630  609.23    4710  604.23    4864  596.83    4900   595.8
    4920  596.36    4940  594.09    4960     594    4970  592.61    4990   591.9
  5002.5  590.46  5010.2  588.05  5020.3  588.09  5022.8   587.2  5023.9   586.7
    5030   587.2  5031.4  592.78  5084.2  592.24  5109.2  590.46  5131.8  588.82
  5152.6  589.57  5162.8  592.99  5189.6  594.98  5213.6  595.57  5242.3   599.3
  5247.4  597.16  5264.5   594.9  5274.7  596.64  5284.8  601.61  5409.5  609.06
#Mann= 5 ,-1 , 0
    4600     .05       0    4864     .12       0  5022.8     .07       0
    5030     .12       0  5109.2     .05       0
Bank Sta=5022.8,5030
XS Rating Curve= 0 ,0
Exp/Cntr=0.3,0.1

Type RM Length L Ch R = 1 ,18543   ,436,436,436
BEGIN DESCRIPTION:
Whites Branch 35.0
END DESCRIPTION:
XS GIS Cut Line= 3
      2373672.01      7074191.25      2373278.53      7074144.91
      2372717.21      7074121.81
#Sta/Elev= 30
  4603.8  610.86  4659.7  609.37  4687.4   607.7  4742.8  603.56  4767.9  600.65
  4798.1  598.26  4818.3  597.35  4838.4  594.92  4888.8  593.39  4929.6  593.73
  4979.4  594.18  4989.5  592.93  4996.9  589.45  5002.3   588.9  5009.5  584.52
  5015.9  583.81    5017  583.31  5023.2  583.81  5031.1   587.7  5039.6  589.45
  5069.6  591.71  5099.6  595.16  5179.7  597.24  5209.7  598.53  5219.7   599.6
  5242.9  600.04  5359.8  606.15  5459.9  612.46    5500  613.86  5561.8  618.21
#Mann= 5 ,-1 , 0
  4603.8     .05       0  4929.6     .12       0  5015.9     .07       0
  5023.2     .12       0  5031.1     .05       0
Bank Sta=5015.9,5023.2
XS Rating Curve= 0 ,0
Exp/Cntr=0.3,0.1