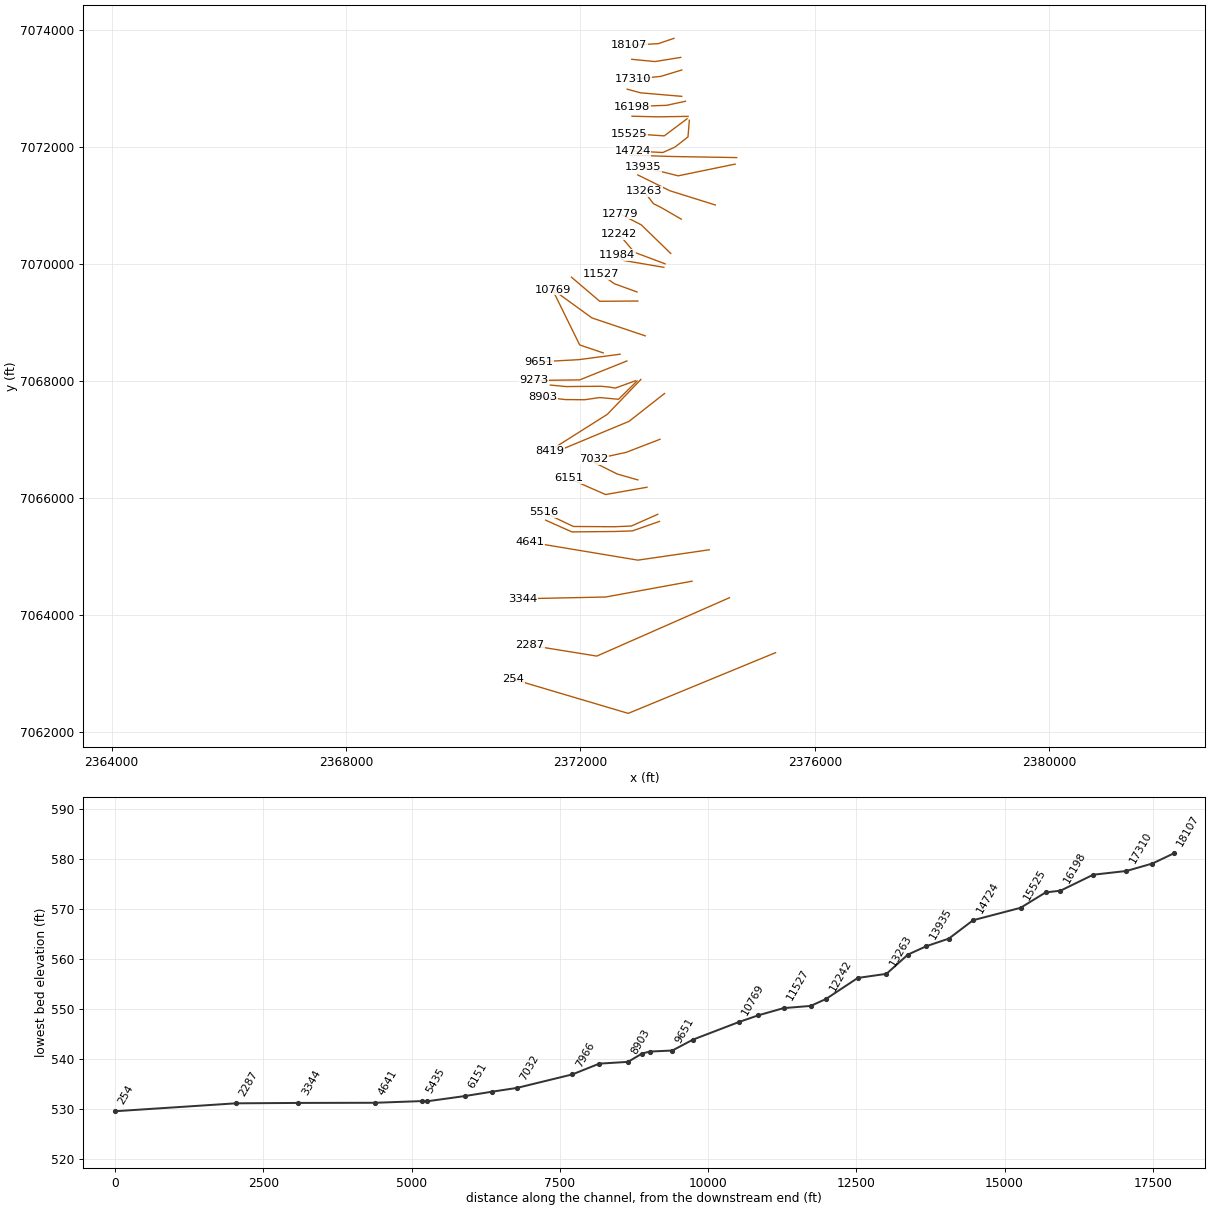
HEC-RAS study Whites Branch.prj: Whites Branch Base Level Engineering

--- Whites Branch.g01 (geometry) --- (continued)

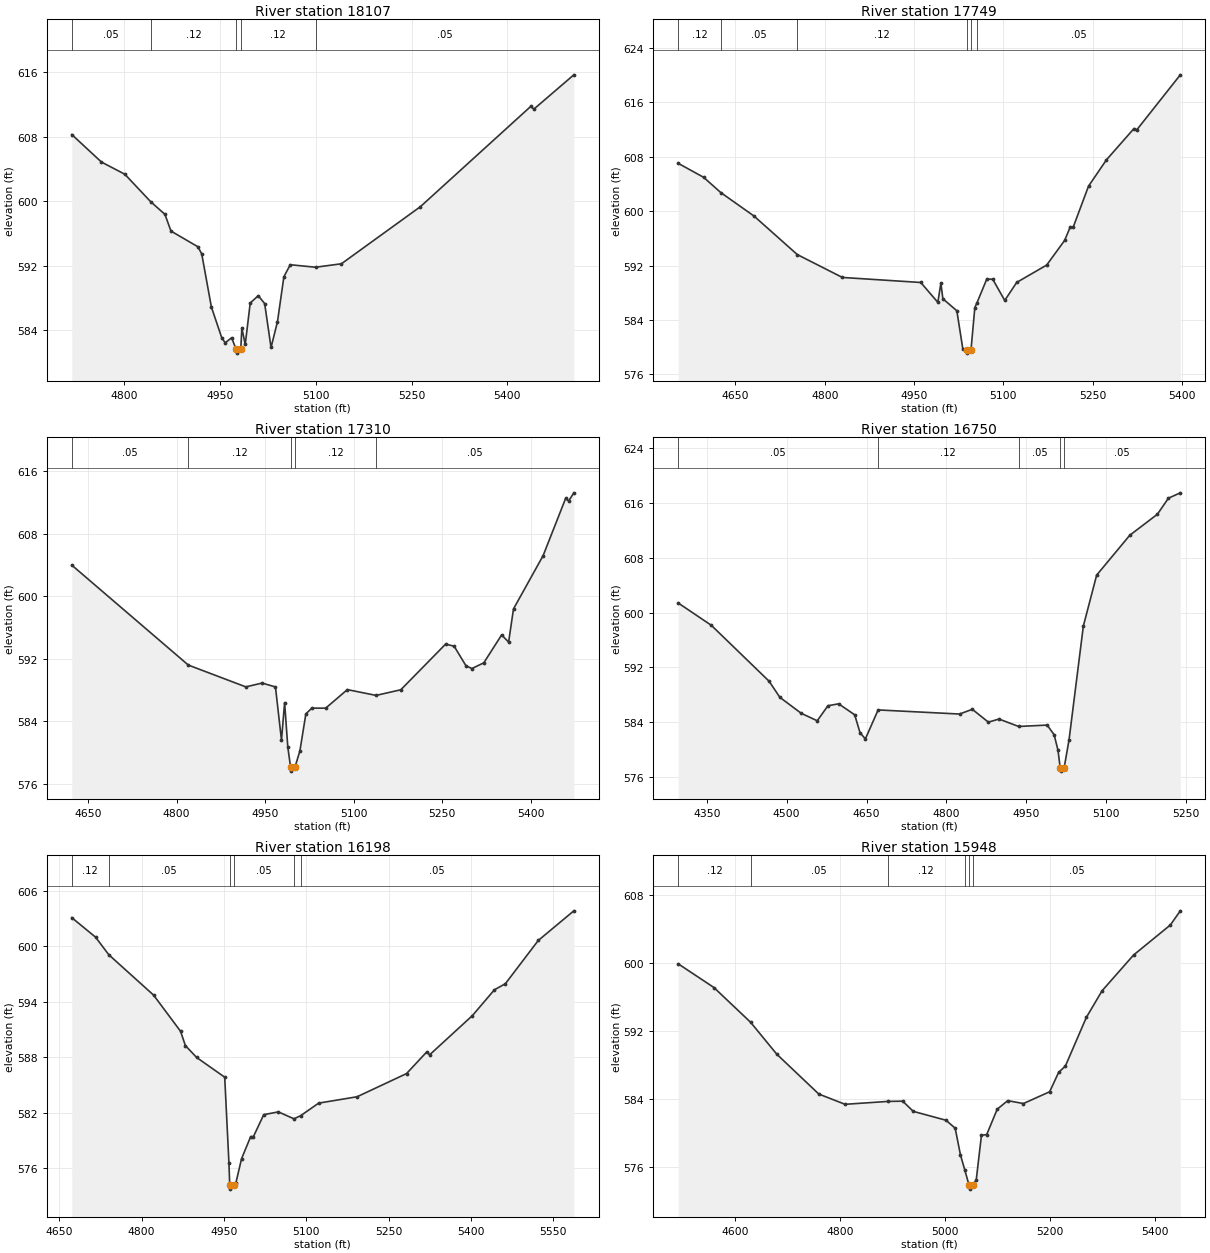
Type RM Length L Ch R = 1 ,18107   ,358,358,358
BEGIN DESCRIPTION:
Whites Branch 34.0
END DESCRIPTION:
XS GIS Cut Line= 3
      2373596.06      7073850.54        2373329.        7073760.
      2372825.72      7073731.19
#Sta/Elev= 30
    4718  608.28  4764.4  604.87  4801.1  603.35  4841.6  599.94  4863.9  598.37
  4873.3   596.3  4915.5  594.35  4921.5  593.46  4936.6  586.87  4952.9  583.04
  4958.2  582.43  4968.3  583.06  4975.2  581.65  4976.3  581.15  4982.6  581.65
  4984.3  584.25  4989.6  582.23  4997.4  587.37    5010  588.28    5020   587.3
    5030  581.85  5040.1  585.06  5050.1  590.63  5060.1  592.12  5099.7  591.81
  5140.2  592.24  5263.9  599.33  5436.5  611.76  5441.6  611.44  5504.1  615.69
#Mann= 5 ,-1 , 0
    4718     .05       0  4841.6     .12       0  4975.2     .07       0
  4982.6     .12       0  5099.7     .05       0
Bank Sta=4975.2,4982.6
XS Rating Curve= 0 ,0
Exp/Cntr=0.3,0.1

Type RM Length L Ch R = 1 ,17749   ,439,439,439
BEGIN DESCRIPTION:
Whites Branch 33.0
END DESCRIPTION:
XS GIS Cut Line= 3
      2373711.04      7073525.01      2373270.84      7073453.95
      2372875.61      7073492.47
#Sta/Elev= 30
  4554.1  607.04  4596.7  604.99  4625.6  602.74  4681.2   599.3  4753.9  593.63
  4829.7  590.26  4961.3  589.52    4990   586.6  4995.1  589.42  4998.4  587.13
  5021.9  585.36    5032  579.71  5038.3  579.63  5039.5  579.13  5045.7  579.63
  5052.1  585.84  5055.3  586.45  5072.2  590.03  5082.2  589.99  5102.3  586.88
  5122.4  589.53  5172.7  592.08  5202.8   595.7  5212.4   597.7  5217.4  597.69
    5243  603.69  5273.1  607.56  5319.2  612.15  5324.3     612  5397.1  620.06
#Mann= 6 ,-1 , 0
  4554.1     .12       0  4625.6     .05       0  4753.9     .12       0
  5038.3     .07       0  5045.7     .12       0  5055.3     .05       0
Bank Sta=5038.3,5045.7
XS Rating Curve= 0 ,0
Exp/Cntr=0.3,0.1

Type RM Length L Ch R = 1 ,17310   ,560,560,560
BEGIN DESCRIPTION:
Whites Branch 32.0
END DESCRIPTION:
XS GIS Cut Line= 3
      2373729.01        7073310.       2373367.9      7073199.97
      2372897.25      7073153.92
#Sta/Elev= 30
  4622.5     604  4819.9  591.21  4917.3  588.42  4944.9  588.91  4967.5  588.41
  4977.7   581.6    4983  586.41  4988.4  580.74  4993.1  578.14  4994.2  577.64
  5000.5  578.14  5008.9  580.23    5019  584.96    5029   585.7  5052.6   585.7
  5089.3  588.07  5137.9  587.33  5179.8  588.05  5255.8   593.9  5270.2  593.62
  5290.3  591.11  5300.3  590.77  5320.4   591.5  5350.6  595.07  5362.4  594.15
  5370.7   598.4  5420.9  605.22    5459  612.54    5464   612.2  5472.9  613.25
#Mann= 5 ,-1 , 0
  4622.5     .05       0  4819.9     .12       0  4993.1     .07       0
  5000.5     .12       0  5137.9     .05       0
Bank Sta=4993.1,5000.5
XS Rating Curve= 0 ,0
Exp/Cntr=0.3,0.1

Type RM Length L Ch R = 1 ,16750   ,552,552,552
BEGIN DESCRIPTION:
Whites Branch 31.0
END DESCRIPTION:
XS GIS Cut Line= 3
      2373728.97        7072860.      2373028.01      7072919.82
      2372797.48      7072982.48
#Sta/Elev= 30
  4296.5  601.39  4358.5  598.15  4467.1  589.99  4487.2  587.65  4527.3  585.32
  4557.4  584.23  4577.5  586.42  4597.6   586.7  4627.7   585.1  4637.7   582.5
  4647.7  581.58  4671.7  585.81  4824.5  585.21  4848.5   585.9  4878.6  584.03
  4898.6  584.48  4935.4   583.4    4989   583.6  5002.1  582.19  5009.3  579.93
  5013.4  577.39  5014.5  576.89  5020.9  577.39  5030.1  581.48  5056.9  598.03
  5081.9  605.46  5144.1  611.27  5195.9  614.33  5216.6  616.67  5238.9  617.45
#Mann= 5 ,-1 , 0
  4296.5     .05       0  4671.7     .12       0  4935.4     .05       0
  5013.4     .04       0  5020.9     .05       0
Bank Sta=5013.4,5020.9
XS Rating Curve= 0 ,0
Exp/Cntr=0.3,0.1

Type RM Length L Ch R = 1 ,16198   ,250,250,250
BEGIN DESCRIPTION:
Whites Branch 30.0
END DESCRIPTION:
XS GIS Cut Line= 3
      2373791.33      7072776.31      2373471.48      7072706.88
      2372884.29      7072685.18
#Sta/Elev= 30
  4672.7  603.12    4716  601.01  4740.2   599.1  4821.9  594.72    4871   590.8
  4879.7  589.26  4900.2  587.97  4951.4  585.83  4959.1  576.52  4960.5   574.2
  4961.6   573.7    4968   574.2  4971.8  574.38  4982.1     577  4998.7  579.39
  5003.7  579.39  5022.5  581.77  5049.2  582.07  5077.6  581.32  5089.8  581.66
  5122.6  583.02  5192.6  583.71  5282.7  586.22  5319.7  588.58  5324.7  588.25
  5402.8  592.51  5442.8   595.3  5462.8  595.96  5522.8  600.65  5587.6  603.86
#Mann= 6 ,-1 , 0
  4672.7     .12       0  4740.2     .05       0  4960.5    .033       0
    4968     .05       0  5077.6     .12       0  5089.8     .05       0
Bank Sta=4960.5,4968
XS Rating Curve= 0 ,0
Exp/Cntr=0.3,0.1

Type RM Length L Ch R = 1 ,15948   ,423,423,423
BEGIN DESCRIPTION:
Whites Branch 29.0
END DESCRIPTION:
XS GIS Cut Line= 3
      2373836.97      7072518.08        2373329.        7072510.
      2372879.96      7072520.25
#Sta/Elev= 30
  4491.9  599.92  4559.9  597.13  4629.9  593.03  4679.9  589.26  4759.9  584.57
  4809.9  583.36  4891.5   583.7  4919.9  583.73  4939.9  582.53  5002.4  581.48
  5019.9  580.54  5029.9  577.41  5038.2  575.62  5046.2  573.86  5047.4  573.36
  5053.7  573.86    5060  574.43    5070  579.71    5080  579.79    5100  582.78
    5120  583.79    5150  583.45    5200  584.84  5217.1  587.12    5230  587.87
    5270  593.61    5300  596.75    5360  600.96  5430.1   604.5  5449.1  606.17
#Mann= 6 ,-1 , 0
  4491.9     .12       0  4629.9     .05       0  4891.5     .12       0
  5038.2     .05       0  5046.2     .07       0  5053.7     .05       0
Bank Sta=5046.2,5053.7
XS Rating Curve= 0 ,0
Exp/Cntr=0.3,0.1

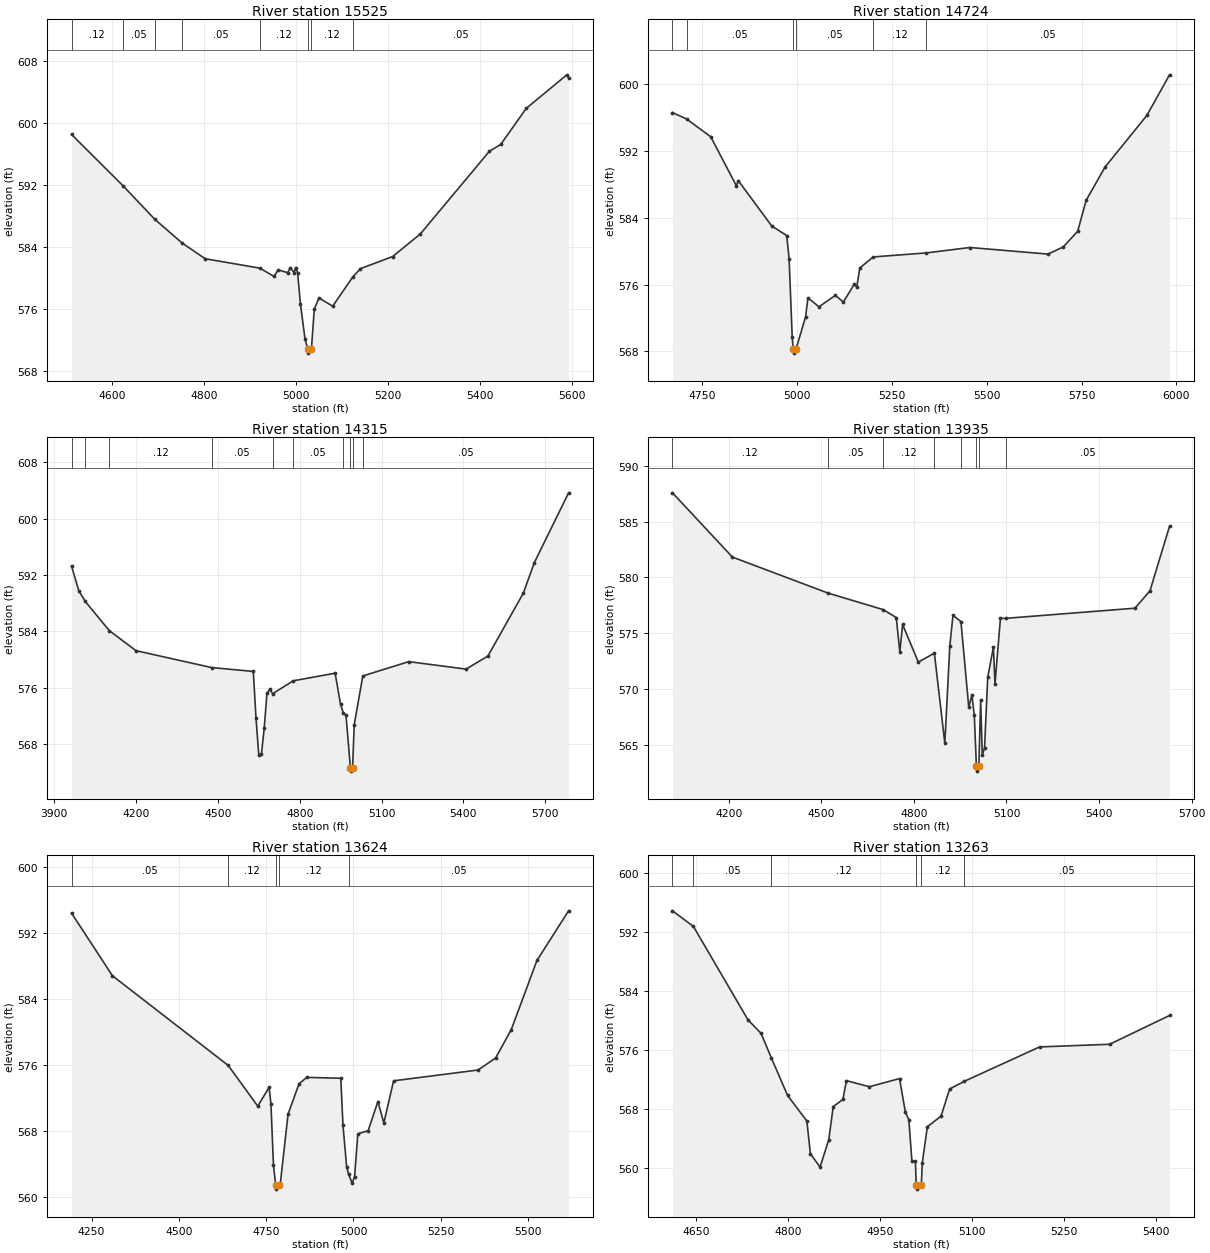
Type RM Length L Ch R = 1 ,15525   ,801,801,801
BEGIN DESCRIPTION:
Whites Branch 28.0
END DESCRIPTION:
XS GIS Cut Line= 3
      2373819.58      7072476.83      2373429.35      7072184.81
      2372837.31      7072225.05
#Sta/Elev= 30
  4512.6  598.56  4624.6  591.92  4693.3  587.61  4752.6  584.54  4803.1  582.49
    4922  581.27  4953.2  580.19  4961.5  581.05  4982.3  580.69  4988.6  581.33
  4996.9  580.68  4999.8  581.35  5004.1  580.68  5010.4  576.63  5020.4  572.07
  5026.6  570.78  5027.8  570.28  5034.2  570.78  5040.4  575.94  5050.5  577.42
  5080.5  576.35  5124.3  580.14  5140.7   581.2  5210.8  582.77    5271  585.69
  5421.3  596.39  5445.8  597.26  5501.5  601.94  5589.6  606.27  5593.4  605.87
#Mann= 8 ,-1 , 0
  4512.6     .12       0  4624.6     .05       0  4693.3     .12       0
  4752.6     .05       0    4922     .12       0  5026.6     .07       0
  5034.2     .12       0  5124.3     .05       0
Bank Sta=5026.6,5034.2
XS Rating Curve= 0 ,0
Exp/Cntr=0.3,0.1

Type RM Length L Ch R = 1 ,14724   ,409,409,409
BEGIN DESCRIPTION:
Mapping XS 061fa042
END DESCRIPTION:
XS GIS Cut Line= 5
      2373858.05      7072450.52      2373834.61      7072166.64
      2373610.65      7071992.16      2373404.92      7071901.02
      2372889.34      7071927.06
#Sta/Elev= 30
  4671.9  596.61  4709.1  595.84  4772.8  593.71  4840.3  587.84  4845.3  588.46
  4933.3  583.04  4972.9  581.88  4979.3  579.13  4987.4  569.76    4990   568.3
  4991.1   567.8  4997.6   568.3  5022.7  572.14    5029  574.42    5058  573.35
  5101.4  574.72  5122.2  573.91  5151.2  576.07  5157.5  575.69  5165.6     578
  5200.9  579.32  5340.6   579.8  5455.8  580.45  5661.8  579.66  5701.9  580.52
  5739.9   582.4    5762  586.09    5812  590.09  5922.2  596.27  5981.9  601.13
#Mann= 6 ,-1 , 0
  4671.9     .12       0  4709.1     .05       0    4990    .033       0
  4997.6     .05       0  5200.9     .12       0  5340.6     .05       0
Bank Sta=4990,4997.6
XS Rating Curve= 0 ,0
Exp/Cntr=0.3,0.1

Type RM Length L Ch R = 1 ,14315   ,380,380,380
BEGIN DESCRIPTION:
Whites Branch 26.0
END DESCRIPTION:
XS GIS Cut Line= 3
      2374665.48      7071814.17      2373553.34      7071832.91
      2372843.31      7071855.81
#Sta/Elev= 30
  3963.2  593.27  3989.7  589.77  4013.2  588.25  4101.6  584.09  4199.7  581.24
  4476.9  578.84  4629.8  578.29  4639.8  571.61  4649.8  566.47  4659.8   566.6
  4669.8  570.24  4679.8  575.16  4689.8  575.75  4700.9  575.13  4776.2  576.96
  4929.8  578.04  4949.8   573.6    4960  572.37  4969.8  572.05  4985.8  564.63
    4987  564.13  4993.9  564.63  4999.8  570.71  5031.3  577.65  5199.9  579.68
    5410  578.62  5490.1  580.48  5620.1  589.42  5660.1  593.73  5785.9  603.66
#Mann= 10 ,-1 , 0
  3963.2     .12       0  4013.2     .05       0  4101.6     .12       0
  4476.9     .05       0  4700.9     .12       0  4776.2     .05       0
    4960     .12       0  4985.8     .07       0  4993.9     .12       0
  5031.3     .05       0
Bank Sta=4985.8,4993.9
XS Rating Curve= 0 ,0
Exp/Cntr=0.3,0.1

Type RM Length L Ch R = 1 ,13935   ,311,311,311
BEGIN DESCRIPTION:
Whites Branch 25.0
END DESCRIPTION:
XS GIS Cut Line= 3
      2374639.22      7071702.89      2373667.54      7071502.71
       2373067.5      7071652.72
#Sta/Elev= 30
  4017.7   587.6  4211.9  581.83  4521.4   578.6  4700.7  577.11  4742.8   576.4
  4754.4   573.3  4763.3  575.78  4814.3   572.4  4866.3   573.2  4900.2  565.12
  4916.4  573.87  4926.6   576.6  4952.4  576.04  4977.7  568.36  4987.9  569.44
  4995.7  567.61  5002.4  563.11  5003.6  562.61  5010.5  563.11  5016.3  569.01
  5021.5  564.03  5028.9  564.71  5039.2  571.03  5057.6  573.73  5062.7  570.43
  5080.4  576.33  5097.4  576.33  5516.3  577.24  5564.9   578.8  5628.3   584.6
#Mann= 8 ,-1 , 0
  4017.7     .12       0  4521.4     .05       0  4700.7     .12       0
  4866.3     .05       0  4952.4     .12       0  5002.4     .07       0
  5010.5     .12       0  5097.4     .05       0
Bank Sta=5002.4,5010.5
XS Rating Curve= 0 ,0
Exp/Cntr=0.3,0.1

Type RM Length L Ch R = 1 ,13624   ,361,361,361
BEGIN DESCRIPTION:
Mapping XS 9ab41ca9
END DESCRIPTION:
XS GIS Cut Line= 3
      2374300.71      7071004.98      2373527.28      7071247.17
      2372977.77      7071518.02
#Sta/Elev= 30
  4192.7   594.4  4309.8   586.8  4641.5  575.92  4725.9  570.99  4758.4  573.27
  4763.6  571.28  4770.8  563.91  4777.2  561.43  4778.4  560.93  4785.5  561.43
  4790.8  561.72  4812.7  570.03  4844.2  573.71  4866.2  574.48  4963.6  574.37
  4969.9  568.67  4980.4  563.62  4985.7   562.8    4996  561.64  5003.2  562.46
  5012.4  567.64  5041.9  568.01  5069.9  571.55  5086.8  568.94  5114.8  574.06
  5356.3  575.37  5406.8  576.82  5451.7  580.27  5525.2  588.65  5615.8  594.67
#Mann= 5 ,-1 , 0
  4192.7     .05       0  4641.5     .12       0  4777.2     .04       0
  4785.5     .12       0  4985.7     .05       0
Bank Sta=4777.2,4785.5
XS Rating Curve= 0 ,0
Exp/Cntr=0.3,0.1

Type RM Length L Ch R = 1 ,13263   ,484,484,484
BEGIN DESCRIPTION:
Whites Branch 24.0
END DESCRIPTION:
XS GIS Cut Line= 4
      2373719.96      7070762.81        2373379.        7070960.
       2373246.3      7071026.35      2373082.96      7071240.67
#Sta/Elev= 30
  4610.8   594.9    4645  592.78  4734.1  580.09  4755.6  578.24  4772.3  574.91
  4798.7  569.83  4830.3  566.33    4836  561.91  4851.8  560.08    4866  563.79
  4873.3   568.3  4889.1  569.28  4894.9  571.83  4932.2     571  4981.6  572.11
    4991   567.6  4996.8  566.49  5001.8  560.89  5007.5  560.89  5008.9  557.59
  5010.2  557.09  5017.2  557.59  5018.6  560.58    5027  565.56  5049.4  567.01
  5063.4  570.69  5087.1  571.73  5210.3  576.41  5324.6  576.77  5422.5  580.68
#Mann= 6 ,-1 , 0
  4610.8     .12       0    4645     .05       0  4772.3     .12       0
  5008.9     .07       0  5017.2     .12       0  5087.1     .05       0
Bank Sta=5008.9,5017.2
XS Rating Curve= 0 ,0
Exp/Cntr=0.3,0.1

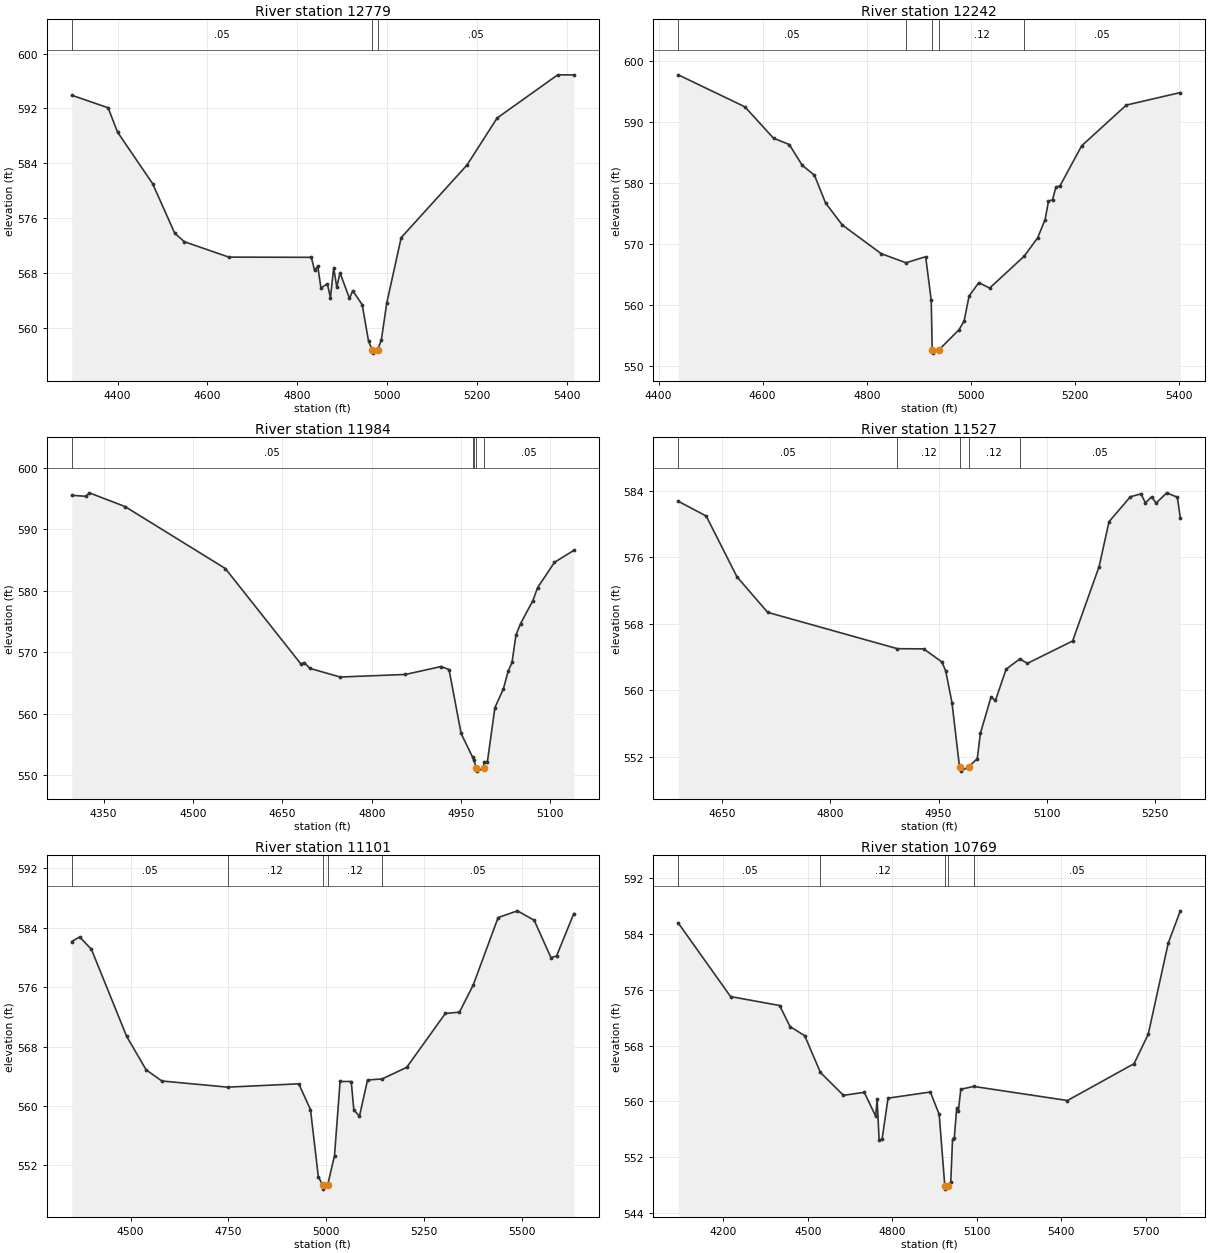
Type RM Length L Ch R = 1 ,12779   ,537,537,537
BEGIN DESCRIPTION:
Whites Branch 23.0
END DESCRIPTION:
XS GIS Cut Line= 3
      2373540.35      7070177.06      2373036.81      7070666.19
      2372667.02      7070855.88
#Sta/Elev= 30
    4298  593.93  4378.9   592.1    4400  588.53  4477.9  581.03  4527.3  573.77
  4548.6  572.54  4647.6  570.29  4831.3  570.26  4838.5  568.34  4845.5  568.98
  4852.7  565.76  4866.8   566.4  4873.8  564.36    4881  568.74  4887.9   565.9
  4895.1  567.99  4916.2  564.26  4923.4  565.39  4944.5  563.34  4958.7  557.98
  4966.7  556.77  4968.4  556.27    4979  556.77    4987  558.16  4999.1  563.57
  5031.3  573.14  5177.8  583.74  5244.8   590.6  5379.7  596.91  5415.6   596.9
#Mann= 3 ,-1 , 0
    4298     .05       0  4966.7    .033       0    4979     .05       0
Bank Sta=4966.7,4979
XS Rating Curve= 0 ,0
Exp/Cntr=0.3,0.1

Type RM Length L Ch R = 1 ,12242   ,258,258,258
BEGIN DESCRIPTION:
Mapping XS 18632cc9
END DESCRIPTION:
XS GIS Cut Line= 3
      2373443.98      7069999.98      2372917.95      7070197.89
      2372657.61      7070505.09
#Sta/Elev= 30
  4437.8  597.77  4565.8  592.52  4620.9  587.36  4651.2  586.32    4676  582.91
  4699.5  581.29  4720.9  576.72    4753  573.11  4827.8   568.4  4875.3   566.9
  4913.2   567.9  4923.9  560.75  4925.8  552.56  4927.6  552.06  4938.2  552.56
  4977.3   555.9  4987.1  557.35  4996.6  561.42  5015.3  563.65  5036.1  562.74
  5102.5  567.98  5128.4     571  5142.7     574  5149.2  576.99    5157  577.27
  5163.5  579.34  5171.3  579.53  5212.9  586.11  5298.7   592.8  5402.5  594.86
#Mann= 5 ,-1 , 0
  4437.8     .05       0  4875.3     .12       0  4925.8     .07       0
  4938.2     .12       0  5102.5     .05       0
Bank Sta=4925.8,4938.2
XS Rating Curve= 0 ,0
Exp/Cntr=0.3,0.1

Type RM Length L Ch R = 1 ,11984   ,457,457,457
BEGIN DESCRIPTION:
Mapping XS 4f833097
END DESCRIPTION:
XS GIS Cut Line= 3
      2373423.15      7069940.08      2372738.26      7070057.27
      2372623.82       7070150.9
#Sta/Elev= 30
  4296.6  595.53  4320.9  595.36    4326  595.93    4386   593.7  4554.4  583.62
  4681.4  568.08  4686.5  568.33  4696.5  567.38  4747.2  565.98  4856.6   566.4
  4916.7  567.69  4929.8   567.2  4950.1   556.8  4969.5  552.92  4971.4  552.46
  4975.6  551.18  4977.4  550.68    4988  551.18  4988.5   552.2  4994.2   552.2
  5006.8     561  5021.1  564.07    5029  566.91  5035.5  568.36  5042.2  572.83
  5049.8  574.65  5070.6  578.42  5078.5  580.52  5106.8  584.63  5139.3  586.58
#Mann= 5 ,-1 , 0
  4296.6     .05       0  4969.5     .12       0  4971.4     .05       0
  4975.6    .033       0    4988     .05       0
Bank Sta=4975.6,4988
XS Rating Curve= 0 ,0
Exp/Cntr=0.3,0.1

Type RM Length L Ch R = 1 ,11527   ,426,426,426
BEGIN DESCRIPTION:
Whites Branch 20.0
END DESCRIPTION:
XS GIS Cut Line= 3
      2372965.43      7069519.44        2372579.        7069660.
      2372347.36      7069824.99
#Sta/Elev= 30
  4589.3  582.76  4628.1  580.97  4670.6  573.66  4713.2  569.37    4893  564.99
  4929.4  564.97  4954.6  563.39  4959.9  562.31  4968.6  558.47    4979  550.74
  4980.7  550.24  4991.5  550.74  5003.6  551.74  5007.9  554.78  5022.6  559.16
  5028.8  558.76  5043.5  562.51  5062.6  563.77    5073  563.22  5135.7  565.92
  5172.4  574.89  5186.1  580.29  5215.7  583.29  5230.4  583.65  5236.6  582.55
  5245.2   583.3  5251.3  582.53  5266.1  583.77  5280.8  583.24  5284.9  580.76
#Mann= 5 ,-1 , 0
  4589.3     .05       0    4893     .12       0    4979     .07       0
  4991.5     .12       0  5062.6     .05       0
Bank Sta=4979,4991.5
XS Rating Curve= 0 ,0
Exp/Cntr=0.3,0.1

Type RM Length L Ch R = 1 ,11101   ,332,332,332
BEGIN DESCRIPTION:
Whites Branch 19.0
END DESCRIPTION:
XS GIS Cut Line= 3
      2372979.28      7069364.94        2372329.        7069360.
      2371847.34      7069771.18
#Sta/Elev= 30
  4349.7  582.14    4370  582.75    4400  581.08    4490  569.37    4540  564.85
    4580  563.36  4748.4  562.53    4930  562.98    4960  559.51    4980   550.5
  4991.2   549.3    4993   548.8  5003.7   549.3  5021.4  553.31  5035.7   563.3
  5064.2  563.29  5070.8  559.48  5085.1   558.6  5105.9  563.49  5143.2  563.64
  5205.9  565.19  5304.7  572.45  5340.9  572.63    5376  576.28  5439.7  585.36
  5489.1  586.27  5531.9     585  5574.8  579.97    5589  580.18  5633.3  585.91
#Mann= 5 ,-1 , 0
  4349.7     .05       0  4748.4     .12       0  4991.2     .07       0
  5003.7     .12       0  5143.2     .05       0
Bank Sta=4991.2,5003.7
XS Rating Curve= 0 ,0
Exp/Cntr=0.3,0.1

Type RM Length L Ch R = 1 ,10769   ,767,767,767
BEGIN DESCRIPTION:
Whites Branch 18.0
END DESCRIPTION:
XS GIS Cut Line= 3
      2373105.18      7068769.87      2372195.58      7069076.52
      2371528.97      7069560.02
#Sta/Elev= 30
  4040.1  585.56    4226  575.02  4400.3  573.74  4437.1  570.73  4489.5  569.41
  4545.1  564.15    4627  560.87  4700.9  561.31  4741.3   557.9  4746.6  560.28
  4753.7  554.43  4764.2  554.61  4785.3  560.47  4935.5  561.35    4967  558.15
  4986.9  547.94  4988.7  547.44  4999.4  547.94  5008.1  548.44  5014.4  554.55
  5020.6  554.73  5029.1  559.01  5035.2   558.7  5043.8  561.74  5089.5  562.15
  5422.6  560.13  5659.2  565.41  5709.4   569.6  5780.6  582.68  5823.5   587.3
#Mann= 5 ,-1 , 0
  4040.1     .05       0  4545.1     .12       0  4986.9     .07       0
  4999.4     .12       0  5089.5     .05       0
Bank Sta=4986.9,4999.4
XS Rating Curve= 0 ,0
Exp/Cntr=0.3,0.1

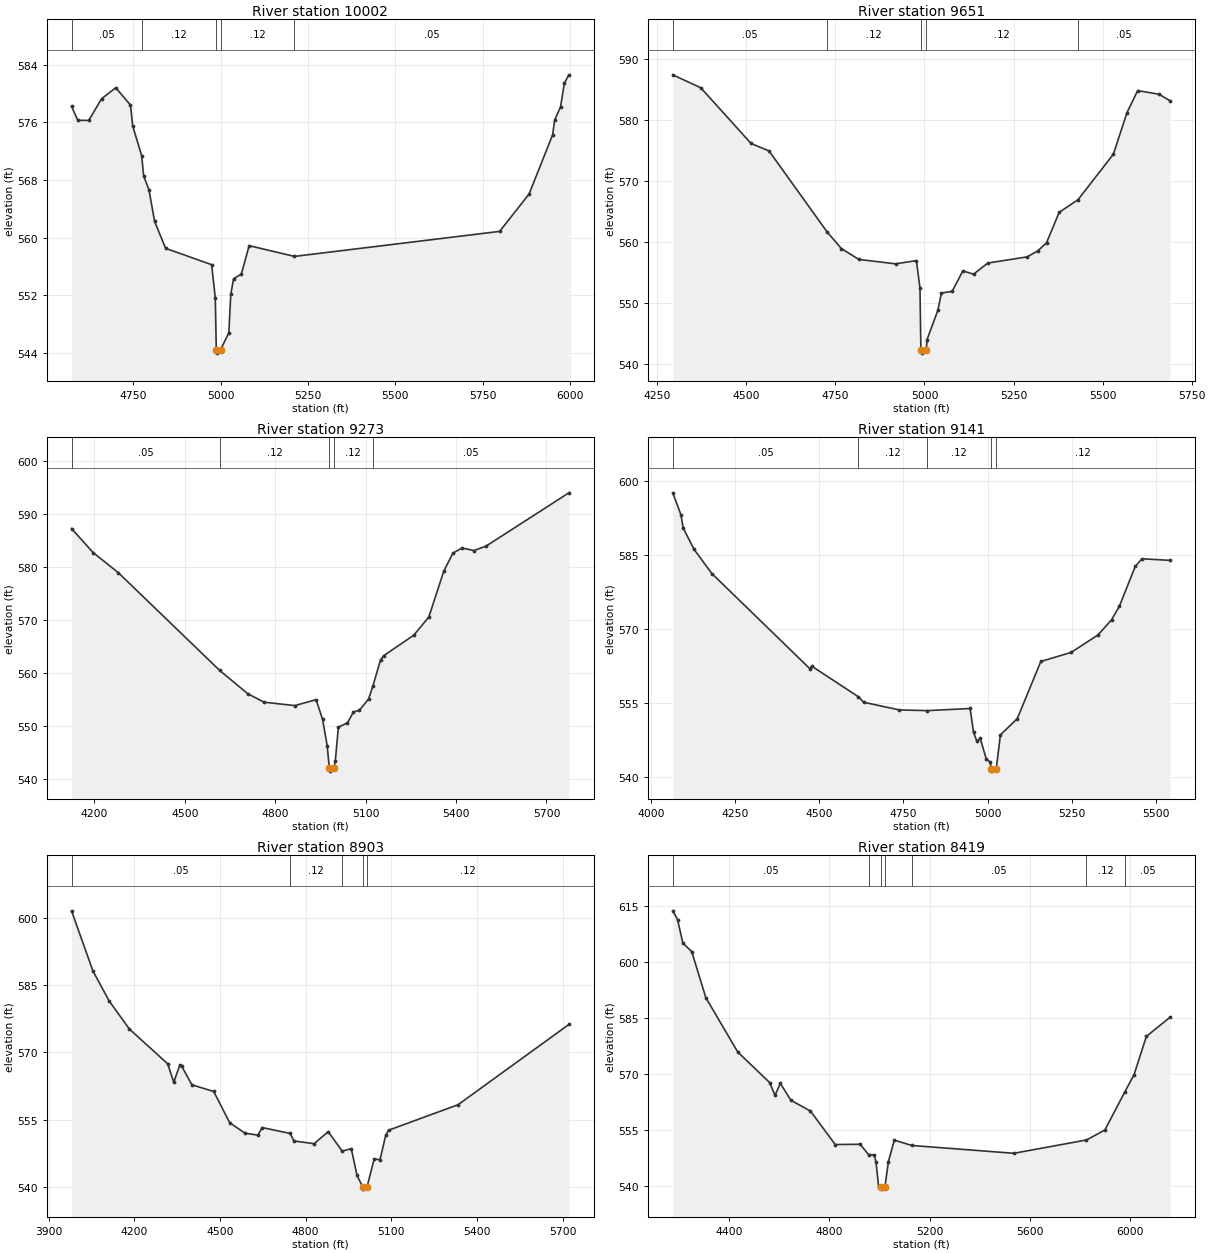
Type RM Length L Ch R = 1 ,10002   ,351,351,351
BEGIN DESCRIPTION:
Whites Branch 17.0
END DESCRIPTION:
XS GIS Cut Line= 3
      2372388.89      7068478.56      2371986.77      7068614.68
      2371545.96      7069511.46
#Sta/Elev= 30
  4573.1   578.2    4591  576.26  4622.4  576.24  4659.1  579.25  4699.7  580.78
  4741.9  578.38  4748.2  575.47  4773.9  571.36  4779.6  568.53  4794.7  566.64
    4811  562.23  4842.4   558.5  4974.2  556.23  4984.7  551.62  4987.5  544.46
  4989.3  543.96  5000.1  544.46  5023.4  546.78    5029   552.1    5037  554.28
  5059.3  554.93  5081.6  558.87  5211.3  557.38  5798.8  560.85  5883.1  566.04
  5950.6  574.27  5956.1  576.28    5973  578.12  5984.2  581.43  5996.9  582.57
#Mann= 5 ,-1 , 0
  4573.1     .05       0  4773.9     .12       0  4987.5     .07       0
  5000.1     .12       0  5211.3     .05       0
Bank Sta=4987.5,5000.1
XS Rating Curve= 0 ,0
Exp/Cntr=0.3,0.1

Type RM Length L Ch R = 1 ,9651    ,378,378,378
BEGIN DESCRIPTION:
Whites Branch 16.0
END DESCRIPTION:
XS GIS Cut Line= 3
      2372676.94      7068456.43      2371969.51      7068363.12
      2371288.06      7068326.22
#Sta/Elev= 30
  4293.5  587.34  4372.1  585.22  4513.3   576.1  4563.8  574.87  4726.1  561.66
  4766.9  558.88  4815.9  557.11    4919  556.39  4977.3  556.92  4987.4  552.45
  4989.9  542.27  4991.9  541.77  5005.2  542.27  5007.1  543.97  5037.6  548.79
  5047.6  551.61  5077.7  551.89  5107.7  555.23  5137.8   554.7  5177.8  556.52
    5288  557.53    5318  558.51  5342.6  559.84  5378.1  564.82    5431  566.89
  5530.3  574.35  5568.4  581.14  5598.4  584.76  5658.5  584.16  5689.5  583.08
#Mann= 5 ,-1 , 0
  4293.5     .05       0  4726.1     .12       0  4989.9     .07       0
  5005.2     .12       0    5431     .05       0
Bank Sta=4989.9,5005.2
XS Rating Curve= 0 ,0
Exp/Cntr=0.3,0.1

Type RM Length L Ch R = 1 ,9273    ,132,132,132
BEGIN DESCRIPTION:
Whites Branch 15.0
END DESCRIPTION:
XS GIS Cut Line= 3
      2372791.76      7068341.06      2371988.26      7068018.21
      2371204.36      7068007.79
#Sta/Elev= 30
  4124.5  587.32    4196  582.79  4279.3  579.01  4616.2  560.54  4709.4  556.15
  4763.3  554.56  4865.3  553.92  4935.8  555.04  4957.3  551.33  4972.8  546.32
  4979.7  542.06  4981.7  541.56    4995  542.06  4999.7  543.54  5009.7  549.85
  5039.7  550.66  5059.7   552.7  5079.7  553.05  5109.7  555.13  5123.9  557.55
  5149.7  562.54  5159.7  563.32  5259.7  567.19  5309.7  570.61  5359.7  579.31
  5389.7  582.67  5419.7  583.64  5459.7  583.17  5499.7     584  5774.4  594.05
#Mann= 5 ,-1 , 0
  4124.5     .05       0  4616.2     .12       0  4979.7     .07       0
    4995     .12       0  5123.9     .05       0
Bank Sta=4979.7,4995
XS Rating Curve= 0 ,0
Exp/Cntr=0.3,0.1

Type RM Length L Ch R = 1 ,9141    ,238,238,238
BEGIN DESCRIPTION:
Mapping XS a3cbdf7e
END DESCRIPTION:
XS GIS Cut Line= 6
      2372938.09      7068002.76      2372594.33      7067877.75
      2372483.22      7067896.85      2372353.02        7067909.
      2371754.06       7067903.8      2371486.12      7067929.58
#Sta/Elev= 30
  4064.8  597.56    4089  593.12  4095.8  590.42  4127.7  586.14  4180.9   581.2
  4472.4   561.9  4477.5  562.45  4616.3  556.23    4632  555.12  4738.1  553.57
    4821  553.43  4948.2  553.86  4958.2  549.06  4968.2  547.22  4978.2   547.8
    4996  543.67  5008.2  542.95  5010.5  541.67  5012.5  541.17  5025.8  541.67
  5038.2  548.52  5088.2   551.8  5158.2  563.39  5248.2  565.22  5328.4  568.78
  5368.6  571.86  5391.9  574.63  5438.9  582.67    5459   584.2  5542.3  583.87
#Mann= 5 ,-1 , 0
  4064.8     .05       0  4616.3     .12       0    4821     .12       0
  5010.5     .07       0  5025.8     .12       0
Bank Sta=5010.5,5025.8
XS Rating Curve= 0 ,0
Exp/Cntr=0.3,0.1

Type RM Length L Ch R = 1 ,8903    ,484,484,484
BEGIN DESCRIPTION:
Whites Branch 14.0
END DESCRIPTION:
XS GIS Cut Line= 6
      2372965.86      7067999.28      2372649.89      7067686.78
      2372330.45       7067716.3      2372070.23      7067678.98
      2371745.38      7067681.57      2371359.98      7067724.97
#Sta/Elev= 30
  3980.1   601.5  4055.2  588.08  4111.7  581.44  4182.4  575.19  4316.8  567.42
    4338  563.33  4359.2   567.1  4366.3  566.83  4401.6  562.74  4478.1  561.25
  4534.1  554.28  4587.6  551.97  4633.1  551.52  4647.7  553.22  4745.5  551.91
  4759.1  550.23  4829.7  549.62    4879  552.31    4928  547.96  4959.8  548.52
    4980  542.55  4999.6     540  5001.6   539.5  5014.9     540  5040.3  546.26
  5060.3  546.02  5080.3  551.46  5090.3  552.62    5334  558.31  5721.8  576.18
#Mann= 5 ,-1 , 0
  3980.1     .05       0  4745.5     .12       0    4928     .12       0
  4999.6     .07       0  5014.9     .12       0
Bank Sta=4999.6,5014.9
XS Rating Curve= 0 ,0
Exp/Cntr=0.3,0.1

Type RM Length L Ch R = 1 ,8419    ,453,453,453
BEGIN DESCRIPTION:
Whites Branch 13.0
END DESCRIPTION:
XS GIS Cut Line= 3
      2373030.91      7068024.87      2372459.13      7067430.29
      2371479.02      7066810.01
#Sta/Elev= 30
  4175.1  613.63  4194.1  611.29  4215.2  605.03  4250.7  602.71  4307.1  590.38
  4434.4  575.85  4561.8  567.66  4583.1  564.23  4604.2  567.47  4646.7  562.92
  4724.4  560.06  4823.4  551.08  4922.5  551.16  4956.9  548.37  4979.1  548.33
  4986.3  546.39  4996.7  539.65  5006.3  539.65  5008.3  539.15  5021.6  539.65
  5035.7  546.53  5059.3  552.27  5128.2  550.84  5536.1  548.74    5826   552.3
  5899.6  554.97    5979  565.16  6015.8  569.75  6065.2  580.02  6159.9  585.16
#Mann= 7 ,-1 , 0
  4175.1     .05       0  4956.9     .12       0  5006.3     .07       0
  5021.6     .12       0  5128.2     .05       0    5826     .12       0
    5979     .05       0
Bank Sta=5006.3,5021.6
XS Rating Curve= 0 ,0
Exp/Cntr=0.3,0.1

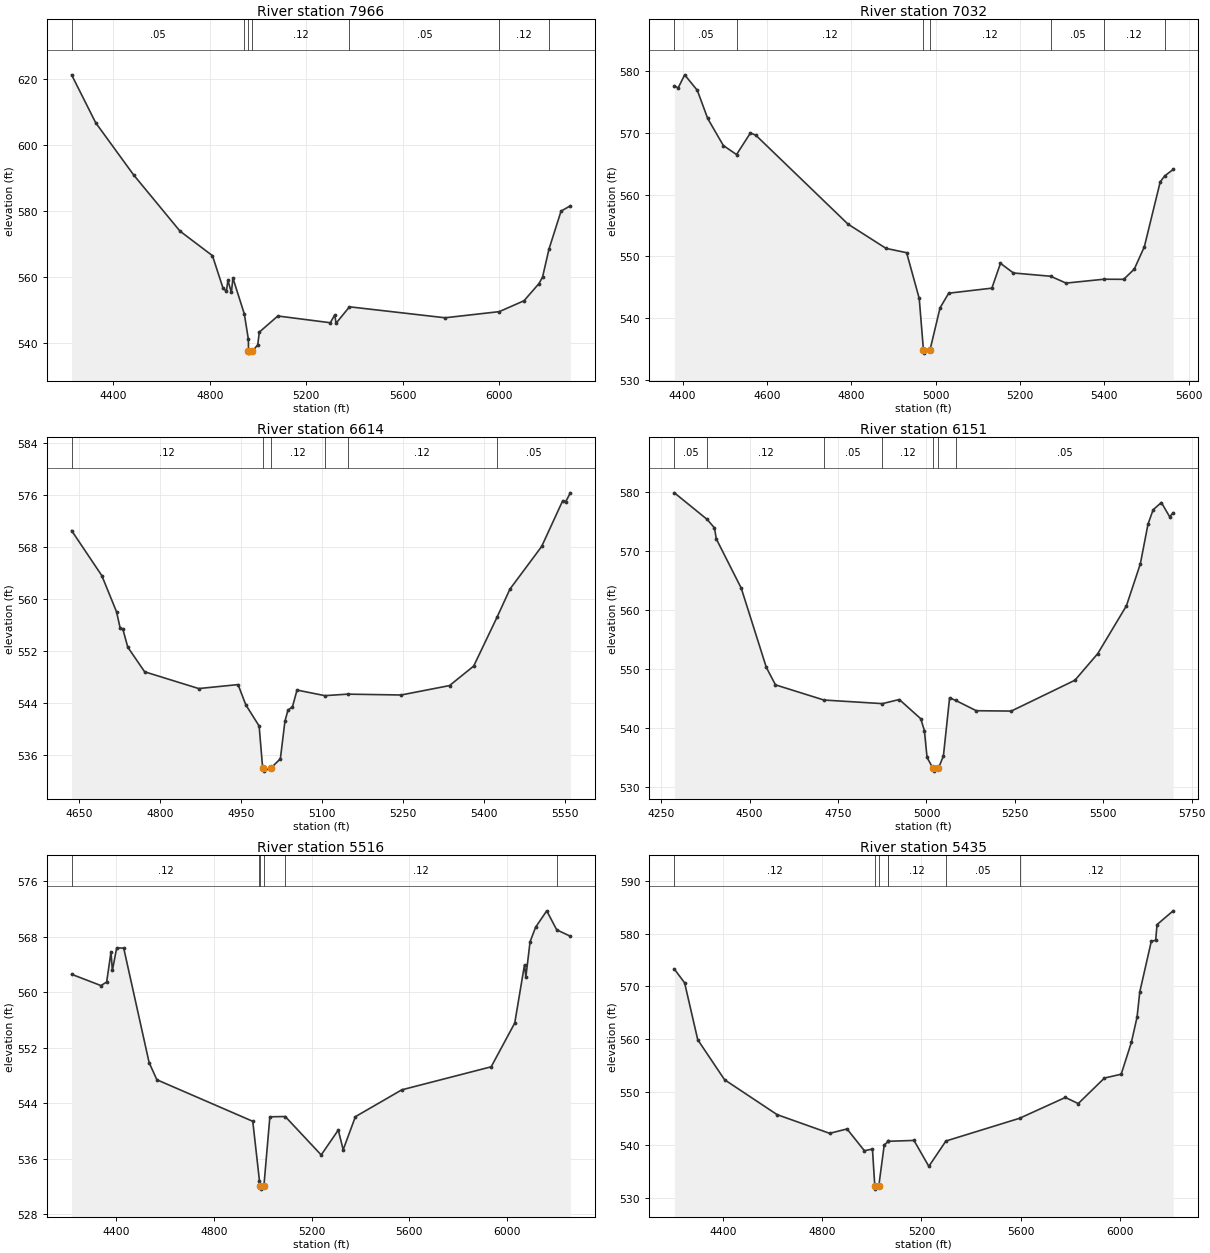
Type RM Length L Ch R = 1 ,7966    ,934,934,934
BEGIN DESCRIPTION:
Whites Branch 12.0
END DESCRIPTION:
XS GIS Cut Line= 3
      2373434.55      7067785.29        2372829.        7067310.
        2371629.        7066810.
#Sta/Elev= 30
  4226.7  621.24  4326.7  606.73    4484  590.96  4676.5  573.93  4811.2   566.5
  4854.6  556.79    4869  555.67  4875.4  559.04  4889.8  555.38  4896.2  559.72
  4943.6  548.83  4960.4  541.14  4960.8   537.5  4962.8     537  4976.2   537.5
  4999.2  539.51  5005.7  543.36  5082.6  548.24  5300.4   546.2  5318.8  548.58
  5324.2  546.04  5379.9  551.02  5776.5   547.7  6001.5  549.56  6104.2  552.85
  6166.5  558.07  6181.1  560.01  6207.8  568.47    6258  579.99  6296.5  581.59
#Mann= 7 ,-1 , 0
  4226.7     .05       0  4943.6     .12       0  4960.8     .07       0
  4976.2     .12       0  5379.9     .05       0  6001.5     .12       0
  6207.8     .05       0
Bank Sta=4960.8,4976.2
XS Rating Curve= 0 ,0
Exp/Cntr=0.3,0.1

Type RM Length L Ch R = 1 ,7032    ,418,418,418
BEGIN DESCRIPTION:
Whites Branch 10.0
END DESCRIPTION:
XS GIS Cut Line= 3
      2373357.28      7067003.61      2372779.48      7066780.46
        2372229.        7066660.
#Sta/Elev= 30
  4380.6  577.66  4389.5  577.31    4405  579.44    4435  576.92  4459.6  572.36
  4496.7  567.97    4528  566.51    4561  570.02  4574.1  569.62  4792.3  555.23
  4882.6  551.29  4931.4  550.59  4961.3  543.17  4971.3   534.8  4973.3   534.3
  4986.8   534.8  5010.7  541.65  5031.2  544.02  5133.6  544.84    5154  548.87
  5184.7   547.3    5273  546.77  5309.5  545.66  5399.9  546.29  5446.2  546.27
  5471.4  547.93  5495.2  551.55  5532.8  562.06  5543.2  563.03  5563.5  564.09
#Mann= 7 ,-1 , 0
  4380.6     .05       0    4528     .12       0  4971.3     .07       0
  4986.8     .12       0    5273     .05       0  5399.9     .12       0
  5543.2     .05       0
Bank Sta=4971.3,4986.8
XS Rating Curve= 0 ,0
Exp/Cntr=0.3,0.1

Type RM Length L Ch R = 1 ,6614    ,463,463,463
BEGIN DESCRIPTION:
Whites Branch 9.0
END DESCRIPTION:
XS GIS Cut Line= 3
      2372979.04      7066309.99        2372629.        7066410.
      2372128.97      7066660.02
#Sta/Elev= 30
  4636.3  570.58  4692.2  563.65  4719.5  558.07    4726  555.63  4731.2  555.39
  4740.3  552.63  4771.5  548.84  4871.6  546.26  4944.4  546.87  4958.7  543.76
  4983.4  540.49  4989.9  534.05  4991.9  533.55  5005.5  534.05  5022.7  535.45
  5031.1   541.2  5036.7  542.93  5045.1  543.45  5053.5  546.03  5104.9  545.17
  5147.4   545.4  5246.3  545.27  5335.8  546.72  5380.5  549.72  5423.5   557.2
  5447.6  561.57  5506.3  568.13  5545.4   575.2    5551  575.05  5559.4  576.39
#Mann= 6 ,-1 , 0
  4636.3     .12       0  4989.9     .07       0  5005.5     .12       0
  5104.9     .05       0  5147.4     .12       0  5423.5     .05       0
Bank Sta=4989.9,5005.5
XS Rating Curve= 0 ,0
Exp/Cntr=0.3,0.1

Type RM Length L Ch R = 1 ,6151    ,635,635,635
BEGIN DESCRIPTION:
Whites Branch 8.0
END DESCRIPTION:
XS GIS Cut Line= 3
      2373135.17      7066184.83        2372429.        7066060.
        2371794.      7066338.49
#Sta/Elev= 30
  4287.1   579.8  4379.7   575.3  4400.5  573.86  4405.6     572  4476.2  563.65
  4547.2  550.22    4573  547.28    4710  544.71  4875.5   544.1  4923.1   544.8
  4983.9  541.54  4994.1  539.54  5001.7  534.98  5018.2  533.17  5020.2  532.67
  5033.9  533.17  5047.9  535.23  5065.4  545.09  5082.4  544.65  5140.9   542.9
  5239.9  542.84  5419.8  548.06  5484.5  552.58  5565.5  560.67  5604.8  567.76
  5626.6  574.51  5641.1  576.94  5664.4  578.16  5687.8  575.74  5697.6  576.43
#Mann= 7 ,-1 , 0
  4287.1     .05       0  4379.7     .12       0    4710     .05       0
  4875.5     .12       0  5018.2     .07       0  5033.9     .12       0
  5082.4     .05       0
Bank Sta=5018.2,5033.9
XS Rating Curve= 0 ,0
Exp/Cntr=0.3,0.1

Type RM Length L Ch R = 1 ,5516    ,81,81,81
BEGIN DESCRIPTION:
Whites Branch 7.0
END DESCRIPTION:
XS GIS Cut Line= 5
      2373317.97      7065721.96      2372868.24       7065522.4
      2372578.61      7065510.24      2371880.39      7065514.58
      2371373.31      7065754.71
#Sta/Elev= 30
  4218.1  562.61  4338.3  560.98  4361.6   561.5  4379.4  565.83  4384.9  563.16
  4402.7  566.42  4431.4  566.38  4535.4  549.87  4567.1   547.4  4959.6  541.41
    4987  532.82  4989.5  532.13  4991.5  531.63  5005.2  532.13  5029.6  542.06
  5092.4   542.1  5239.6  536.56  5309.6  540.15  5329.6  537.31  5379.6  542.08
  5569.6  545.95  5935.3  549.27  6031.8  555.58  6071.7  563.98  6077.3  562.24
  6094.5   567.3  6117.2   569.4  6162.7  571.76  6203.6  569.02  6259.3   568.1
#Mann= 6 ,-1 , 0
  4218.1     .12       0    4987     .12       0  4989.5     .07       0
  5005.2     .12       0  5092.4     .12       0  6203.6     .05       0
Bank Sta=4989.5,5005.2
XS Rating Curve= 0 ,0
Exp/Cntr=0.3,0.1

Type RM Length L Ch R = 1 ,5435    ,794,794,794
BEGIN DESCRIPTION:
Whites Branch 6.0
END DESCRIPTION:
XS GIS Cut Line= 5
      2373347.89      7065600.85       2372885.6      7065439.06
      2372578.95        7065429.      2371853.14      7065422.05
      2371406.11      7065622.12
#Sta/Elev= 30
  4203.4  573.27  4244.6  570.69  4297.6  559.92  4405.8  552.36  4617.7  545.76
  4829.9  542.22  4899.9  543.05  4969.9  538.94  5002.5  539.24  5012.1  532.17
  5014.1  531.67  5027.8  532.17    5050  540.03  5066.7  540.71    5067  540.72
    5170  540.88    5230  535.98  5298.9  540.77  5596.1  545.07  5780.9  549.01
  5832.7  547.85  5938.5  552.68    6006   553.4    6047   559.4    6070  564.18
  6081.1  568.98  6127.5  578.53  6145.2  578.75  6150.7   581.7  6215.6   584.3
#Mann= 7 ,-1 , 0
  4203.4     .12       0  5012.1     .07       0  5027.8     .12       0
  5066.7     .05       0    5067     .12       0  5298.9     .05       0
  5596.1     .12       0
Bank Sta=5012.1,5027.8
XS Rating Curve= 0 ,0
Exp/Cntr=0.3,0.1

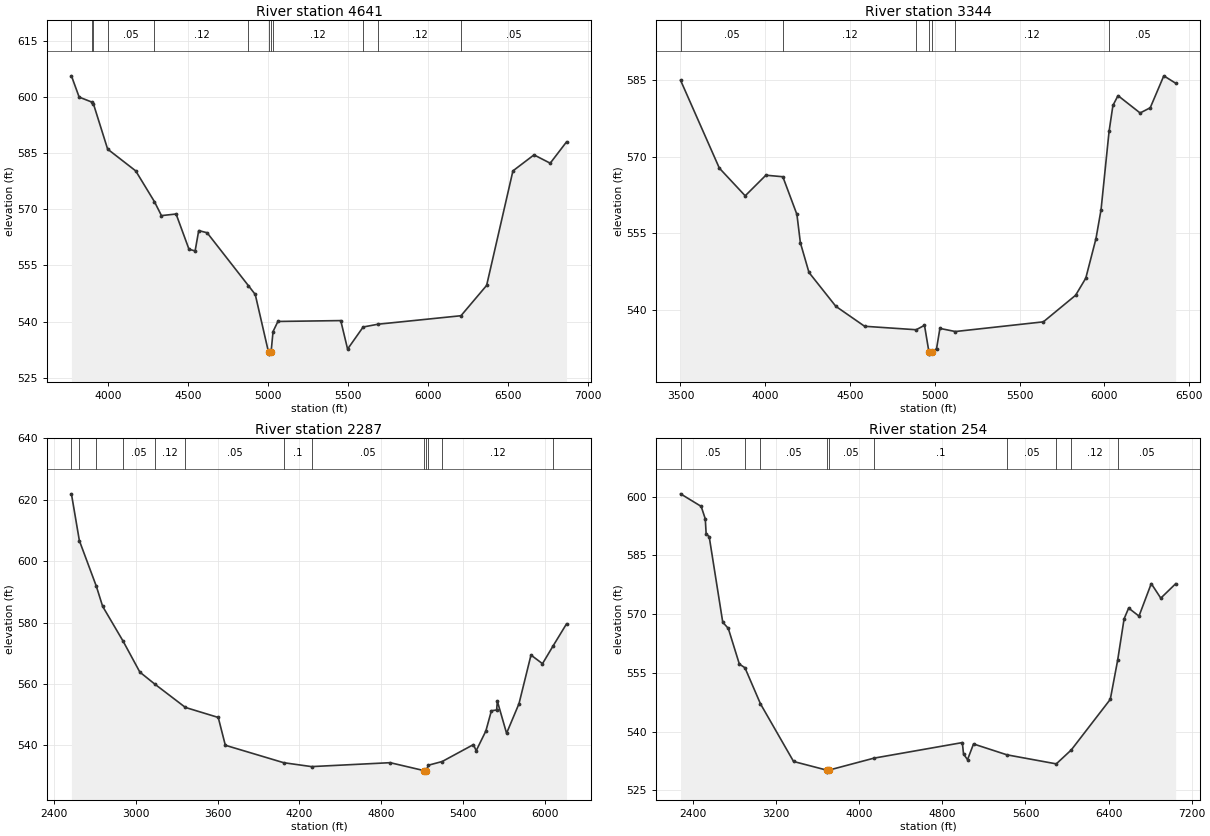
Type RM Length L Ch R = 1 ,4641    ,1297,1297,1297
BEGIN DESCRIPTION:
Whites Branch 5.0
END DESCRIPTION:
XS GIS Cut Line= 3
      2374196.92       7065116.5      2372979.47      7064939.84
      2371138.26      7065246.71
#Sta/Elev= 30
  3769.8  605.61  3818.2  599.93  3896.5  598.62  3907.3  598.15  3996.3  586.05
  4171.9  580.24  4289.2  572.01  4332.9   568.3  4424.5  568.73  4505.3  559.31
  4543.5  558.88    4566  564.31  4618.7  563.72  4876.4  549.63  4919.6  547.26
  5002.7  531.83  5004.7  531.33  5018.5  531.83  5030.9  537.36  5061.3  540.05
  5454.4  540.28  5497.2  532.68  5594.5  538.57  5688.3  539.32  6206.4  541.58
  6366.8  549.67  6531.3  580.24  6663.1  584.51  6764.5  582.29  6866.6  587.98
#Mann= 12 ,-1 , 0
  3769.8     .12       0  3896.5     .05       0  3907.3     .12       0
  3996.3     .05       0  4289.2     .12       0  4876.4      .1       0
  5002.7     .07       0  5018.5      .1       0  5030.9     .12       0
  5594.5     .05       0  5688.3     .12       0  6206.4     .05       0
Bank Sta=5002.7,5018.5
XS Rating Curve= 0 ,0
Exp/Cntr=0.3,0.1

Type RM Length L Ch R = 1 ,3344    ,1057,1057,1057
BEGIN DESCRIPTION:
Whites Branch 4.0
END DESCRIPTION:
XS GIS Cut Line= 3
      2373903.96      7064580.04        2372429.        7064310.
      2371008.99      7064280.56
#Sta/Elev= 30
  3500.6  584.98  3729.3  567.76  3881.8  562.33  4003.8  566.37  4103.7  566.07
  4186.8  558.68  4207.1  553.14  4257.9  547.31  4416.3  540.67    4586  536.76
  4890.2  536.08  4939.1  536.95    4965   531.8    4967   531.3    4982   531.8
  5010.1  532.35  5030.1  536.34    5121  535.73  5640.2  537.63  5830.3  542.84
  5890.3  546.19  5950.3  553.93  5980.3   559.6  6027.6  574.95  6050.3  580.04
  6080.3  581.97  6210.7  578.57  6270.4  579.59  6350.4  585.85  6420.4   584.4
#Mann= 7 ,-1 , 0
  3500.6     .05       0  4103.7     .12       0  4890.2      .1       0
    4965     .07       0    4982      .1       0    5121     .12       0
  6027.6     .05       0
Bank Sta=4965,4982
XS Rating Curve= 0 ,0
Exp/Cntr=0.3,0.1

Type RM Length L Ch R = 1 ,2287    ,2033,2033,2033
BEGIN DESCRIPTION:
Whites Branch 2.0
END DESCRIPTION:
XS GIS Cut Line= 3
      2374541.97      7064297.93      2372278.97      7063301.39
      2371134.81      7063486.29
#Sta/Elev= 30
  2527.3  621.96  2585.7  606.68  2710.4  591.78  2756.2  585.28  2906.9  573.88
  3029.3  563.83  3138.1  559.95  3363.5  552.31  3604.2  549.05  3656.3  539.98
  4084.6  534.29  4288.7  533.02  4865.2   534.3    5113  531.72    5115  531.22
  5130.1  531.72  5146.1  533.48  5246.9  534.68  5476.1   540.2  5496.3   538.2
  5567.2  544.63  5607.8  551.22  5646.3  551.49  5651.4  554.38  5719.2  543.89
  5810.3  553.55  5898.3  569.39  5982.6  566.58  6059.4   572.3    6159  579.57
#Mann= 13 ,-1 , 0
  2527.3     .12       0  2585.7     .05       0  2710.4     .12       0
  2906.9     .05       0  3138.1     .12       0  3363.5     .05       0
  4084.6      .1       0  4288.7     .05       0    5113     .07       0
  5130.1     .05       0  5146.1      .1       0  5246.9     .12       0
  6059.4     .05       0
Bank Sta=5113,5130.1
XS Rating Curve= 0 ,0
Exp/Cntr=0.3,0.1

Type RM Length L Ch R = 1 ,254     ,0,0,0
BEGIN DESCRIPTION:
Whites Branch 1.0
END DESCRIPTION:
XS GIS Cut Line= 3
      2375328.98      7063359.99      2372814.94      7062323.04
      2370853.73       7062904.9
#Sta/Elev= 30
  2280.5  600.76  2478.9  597.55  2518.5  594.35  2526.7  590.54  2556.1  589.81
  2686.6  567.94  2739.8  566.38  2846.4  557.25  2900.2  556.31  3049.7  547.09
  3368.2  532.36  3688.7  530.14  3690.7  529.64  3706.4  530.14  4141.3  533.21
  4992.5  537.19  5003.9  534.27  5042.4  532.82  5100.1  536.84  5421.9  534.06
  5896.6  531.75  6040.6   535.3  6416.4  548.24  6487.3  558.24  6549.3  568.82
    6593  571.56  6692.6  569.51  6810.7  577.82  6902.4   574.1  7045.7  577.79
#Mann= 10 ,-1 , 0
  2280.5     .05       0  2900.2     .12       0  3049.7     .05       0
  3688.7     .07       0  3706.4     .05       0  4141.3      .1       0
  5421.9     .05       0  5896.6      .1       0  6040.6     .12       0
  6487.3     .05       0
Bank Sta=3688.7,3706.4
XS Rating Curve= 0 ,0
Exp/Cntr=0.3,0.1

Chan Stop Cuts=-1
Use User Specified Reach Order=0
Composite Channel Slope=5