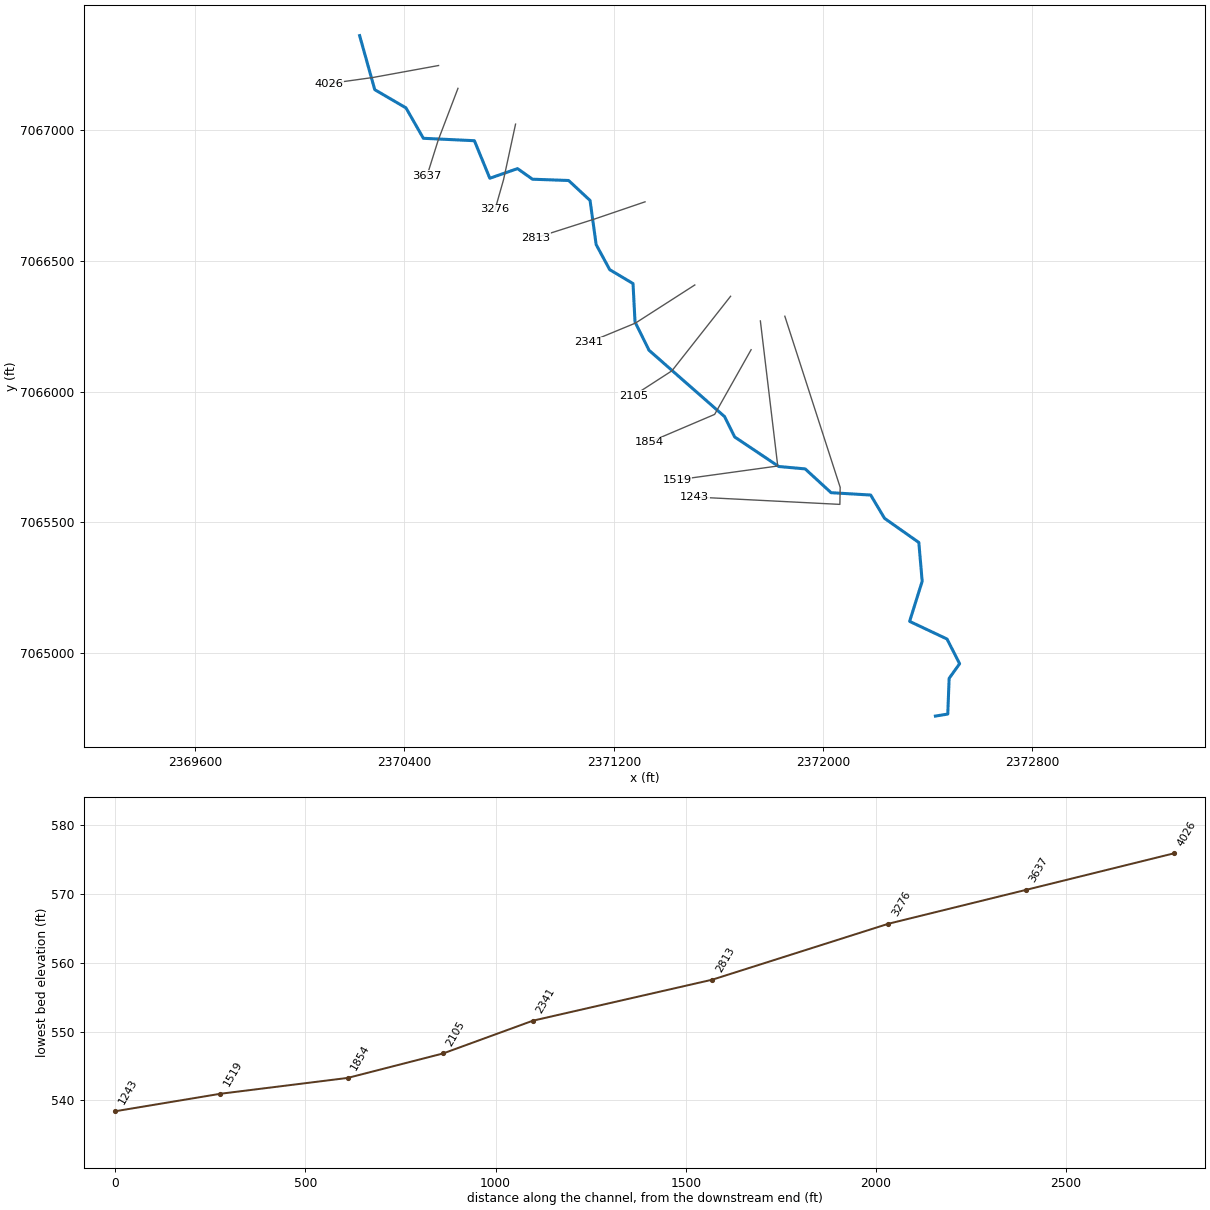
--- Whites Branch Tr 1.prj (project) ---

Proj Title=Whites Branch Tr 1 Base Level Engineering
Current Plan=p01
Default Exp/Contr=0.3,0.1
English Units
Geom File=g01
Flow File=f01
Plan File=p01
Y Axis Title=Elevation
X Axis Title(PF)=Main Channel Distance
X Axis Title(XS)=Station
BEGIN DESCRIPTION:
Whites Branch Tr 1
END DESCRIPTION:
DSS Export Rating Curves= 0
DSS Export Rating Curve Sorted= 0
DSS Export Volume Flow Curves= 0
DXF OffsetX= 0
DXF OffsetY= 0
DXF ScaleX= 1
DXF ScaleY= 10

--- Whites Branch Tr 1.p01 (plan) ---

Plan Title=Multiple Run
Short Identifier=Multiple
Geom File=g01
Flow File=f01
Subcritical Flow
K Sum by GR= 0
Std Step Tol= 0.01
Critical Tol= 0.01
Num of Std Step Trials= 20
Max Error Tol= 0.3
Flow Tol Ratio= 0.001
Split Flow NTrial= 30
Split Flow Tol= 0.02
Split Flow Ratio= 0.02
Log Output Level= 0
Friction Slope Method= 1
Unsteady Friction Slope Method= 2
Unsteady Bridges Friction Slope Method= 1
Parabolic Critical Depth
Global Vel Dist=  1 , 1 , 1
Global Log Level= 0
CheckData=True
Encroach Param= -1, 0, 0, 0
BEGIN DESCRIPTION:
Multiple Run
END DESCRIPTION:

--- Whites Branch Tr 1.f01 (steady flow) ---

Flow Title=Multiple
Program Version=4.10
Number of Profiles= 7
Profile Names=10-year,25-year,50-year,1pct_min,100-year,1pct_plu,500-year
River Rch & RM=Whites Branch Tr,Reach-1         ,4026
     517     703     856     518    1033    2062    1508
Boundary for River Rch & Prof#=Whites Branch Tr,Reach-1         , 1
Up Type= 0
Dn Type= 3
Dn Slope=0.012
Boundary for River Rch & Prof#=Whites Branch Tr,Reach-1         , 2
Up Type= 0
Dn Type= 3
Dn Slope=0.012
Boundary for River Rch & Prof#=Whites Branch Tr,Reach-1         , 3
Up Type= 0
Dn Type= 3
Dn Slope=0.012
Boundary for River Rch & Prof#=Whites Branch Tr,Reach-1         , 4
Up Type= 0
Dn Type= 3
Dn Slope=0.012
Boundary for River Rch & Prof#=Whites Branch Tr,Reach-1         , 5
Up Type= 0
Dn Type= 3
Dn Slope=0.012
Boundary for River Rch & Prof#=Whites Branch Tr,Reach-1         , 6
Up Type= 0
Dn Type= 3
Dn Slope=0.012
Boundary for River Rch & Prof#=Whites Branch Tr,Reach-1         , 7
Up Type= 0
Dn Type= 3
Dn Slope=0.012
DSS Import GetInterval= 0
DSS Import GetPeak= 0
DSS Import FillOption= 0

--- Whites Branch Tr 1.g01 (geometry) ---

Geom Title=Existing Conditions
Program Version=4.10

River Reach=Whites Branch Tr,Reach-1
Reach XY= 30
        2370229.        7067360.      2370286.74      7067153.54
      2370406.13      7067083.83      2370472.53       7066967.7
      2370667.47      7066958.49      2370726.43        7066815.
      2370832.29      7066851.89      2370889.44      7066811.39
      2371027.54      7066806.46      2371109.41      7066730.21
      2371132.75      7066561.53      2371184.62      7066465.62
       2371273.6      7066412.68      2371281.25      7066265.93
      2371334.83      7066157.69      2371623.36      7065904.35
      2371661.99      7065826.58       2371830.5      7065713.63
      2371931.42      7065704.46      2372030.47      7065613.56
      2372181.68       7065604.6      2372234.64      7065515.65
      2372365.64      7065423.34      2372378.49      7065275.22
       2372330.5      7065121.86      2372473.45      7065054.41
      2372521.48      7064960.04      2372481.46      7064904.14
      2372476.28      7064767.71        2372429.        7064760.

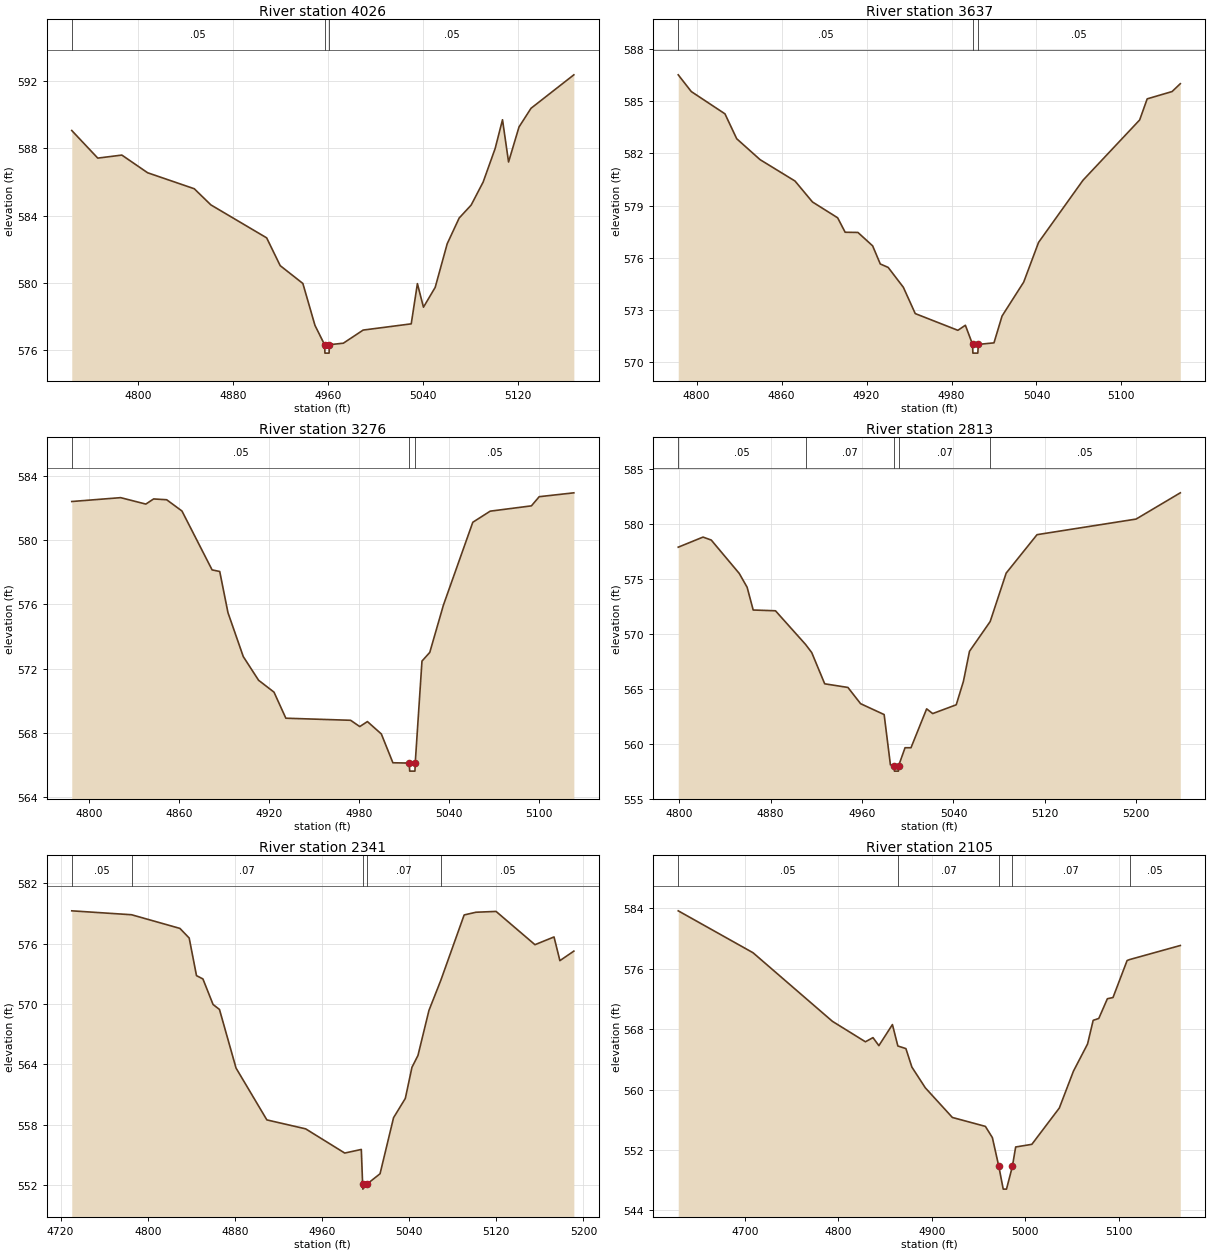
Type RM Length L Ch R = 1 ,4026    ,389,389,389
BEGIN DESCRIPTION:
Whites Branch Tr 1 7.0
END DESCRIPTION:
XS GIS Cut Line= 3
      2370530.54      7067245.82       2370278.8      7067199.88
      2370113.28      7067176.91
#Sta/Elev= 30
  4744.1  589.06    4766  587.42  4786.3   587.6    4808  586.55  4847.3   585.6
  4861.3  584.64  4908.3  582.68  4919.7  581.03  4938.8  579.97    4949  577.48
  4957.1  576.33  4957.4  575.83  4960.9  575.83  4961.1  576.33  4972.9  576.42
  4989.6   577.2  5030.1  577.57  5035.3  579.96  5040.4  578.56  5050.3  579.74
  5060.4  582.33  5070.5  583.86  5080.6  584.63  5090.7     586  5100.8  587.99
    5107   589.7  5112.1  587.19  5120.9  589.27    5131  590.38  5167.1  592.37
#Mann= 3 ,-1 , 0
  4744.1     .05       0  4957.1     .04       0  4961.1     .05       0
Bank Sta=4957.1,4961.1
XS Rating Curve= 0 ,0
Exp/Cntr=0.3,0.1

Type RM Length L Ch R = 1 ,3637    ,361,361,361
BEGIN DESCRIPTION:
Whites Branch Tr 1 6.0
END DESCRIPTION:
XS GIS Cut Line= 3
      2370604.72      7067158.59        2370529.        7066960.
       2370486.4      7066824.48
#Sta/Elev= 30
    4787  586.51  4796.2  585.55    4820  584.27  4828.3  582.84  4844.8  581.64
  4869.5  580.41  4881.8  579.21  4899.6   578.3  4904.9  577.47  4913.9  577.46
  4924.3  576.69  4929.7  575.65  4935.3  575.45    4946  574.31  4954.4   572.8
  4984.5  571.84  4989.8  572.13  4994.9  571.03  4995.1  570.53  4998.6  570.53
  4998.9  571.03    5010  571.12  5015.7  572.66    5031  574.61  5041.5  576.89
  5072.9  580.46  5112.9  583.92  5118.2  585.13  5135.8  585.55  5141.6     586
#Mann= 3 ,-1 , 0
    4787     .05       0  4994.9     .04       0  4998.9     .05       0
Bank Sta=4994.9,4998.9
XS Rating Curve= 0 ,0
Exp/Cntr=0.3,0.1

Type RM Length L Ch R = 1 ,3276    ,463,463,463
BEGIN DESCRIPTION:
Whites Branch Tr 1 5.0
END DESCRIPTION:
XS GIS Cut Line= 3
      2370824.76      7067021.83        2370779.        7066810.
      2370746.64      7066696.33
#Sta/Elev= 30
  4788.4  582.39    4821  582.63  4837.8  582.23    4843  582.55  4851.7   582.5
  4861.9   581.8    4882  578.14  4887.1  578.04  4892.6  575.48  4902.8  572.75
    4913  571.28  4923.3  570.54  4931.2  568.92  4974.4  568.79  4980.5   568.4
  4985.6  568.71  4994.9  567.94  5002.6  566.15  5013.5  566.13  5013.8  565.63
  5017.3  565.63  5017.5  566.13    5022  572.47  5027.2  573.01  5036.3  575.95
  5055.9   581.1  5067.5  581.79    5095  582.12  5100.2  582.69  5123.3  582.93
#Mann= 3 ,-1 , 0
  4788.4     .05       0  5013.5     .04       0  5017.5     .05       0
Bank Sta=5013.5,5017.5
XS Rating Curve= 0 ,0
Exp/Cntr=0.3,0.1

Type RM Length L Ch R = 1 ,2813    ,472,472,472
BEGIN DESCRIPTION:
Whites Branch Tr 1 4.0
END DESCRIPTION:
XS GIS Cut Line= 3
      2371319.52      7066724.97      2371129.36      7066660.15
      2370902.18      7066587.56
#Sta/Elev= 30
  4799.1  577.91  4820.8  578.83    4828  578.56  4852.5  575.52  4859.4  574.26
  4864.7  572.19  4884.2  572.12  4910.5  569.06  4915.9  568.32  4927.3  565.47
  4947.6  565.14  4958.7  563.66  4979.3  562.67  4984.8  558.09    4988  558.02
  4988.3  557.52  4991.8  557.52    4992  558.02  4997.6  559.65  5002.8  559.65
  5016.5  563.19  5021.8  562.76  5042.4  563.56  5048.7   565.7    5054  568.43
  5072.1  571.14  5086.1  575.55  5113.1  579.05  5199.8  580.47  5238.5  582.86
#Mann= 5 ,-1 , 0
  4799.1     .05       0  4910.5     .07       0    4988     .04       0
    4992     .07       0  5072.1     .05       0
Bank Sta=4988,4992
XS Rating Curve= 0 ,0
Exp/Cntr=0.3,0.1

Type RM Length L Ch R = 1 ,2341    ,236,236,236
BEGIN DESCRIPTION:
Whites Branch Tr 1 3.0
END DESCRIPTION:
XS GIS Cut Line= 3
      2371509.69      7066407.29      2371282.76      7066261.56
      2371106.05      7066188.53
#Sta/Elev= 30
  4730.3  579.27  4785.2  578.88  4829.6  577.52  4838.1  576.56  4844.8  572.82
  4850.7  572.49    4860  569.95  4865.9  569.45  4881.1  563.62  4909.4  558.46
    4945  557.57  4980.9  555.16  4996.1  555.52  4997.3  552.07  4997.5  551.57
  5001.3  552.07  5013.3   553.1  5025.7  558.68  5036.5   560.6  5042.6   563.7
  5048.1  564.87  5058.2  569.36  5069.1  572.36  5090.5  578.86  5101.4  579.13
  5119.8  579.21  5155.5   575.9    5173  576.67  5178.4  574.31  5191.2  575.26
#Mann= 5 ,-1 , 0
  4730.3     .05       0  4785.2     .07       0  4997.3     .04       0
  5001.3     .07       0  5069.1     .05       0
Bank Sta=4997.3,5001.3
XS Rating Curve= 0 ,0
Exp/Cntr=0.3,0.1

Type RM Length L Ch R = 1 ,2105    ,251,251,251
BEGIN DESCRIPTION:
Mapping XS 193bb0a9
END DESCRIPTION:
XS GIS Cut Line= 3
      2371646.37      7066364.11      2371422.42      7066079.41
      2371275.68      7065984.46
#Sta/Elev= 30
  4628.9  583.67  4708.9  578.12  4793.8  569.04  4829.1  566.33  4837.2  566.88
  4843.5  565.82    4858  568.61  4863.8  565.77  4872.4  565.43  4878.8  562.98
  4893.2  560.23  4922.1  556.31  4957.4  555.13  4964.9  553.64  4971.8  549.82
  4976.5  546.82    4980  546.82  4986.3  549.83  4989.8   552.4  5007.1  552.75
  5036.5  557.56  5051.6  562.44  5066.7  566.04  5072.7  569.17  5078.7  569.42
  5087.9  572.03  5093.9  572.19    5109  577.09  5111.8  577.22  5165.9  579.08
#Mann= 5 ,-1 , 0
  4628.9     .05       0  4863.8     .07       0  4971.8     .04       0
  4986.3     .07       0  5111.8     .05       0
Bank Sta=4971.8,4986.3
XS Rating Curve= 0 ,0
Exp/Cntr=0.3,0.1

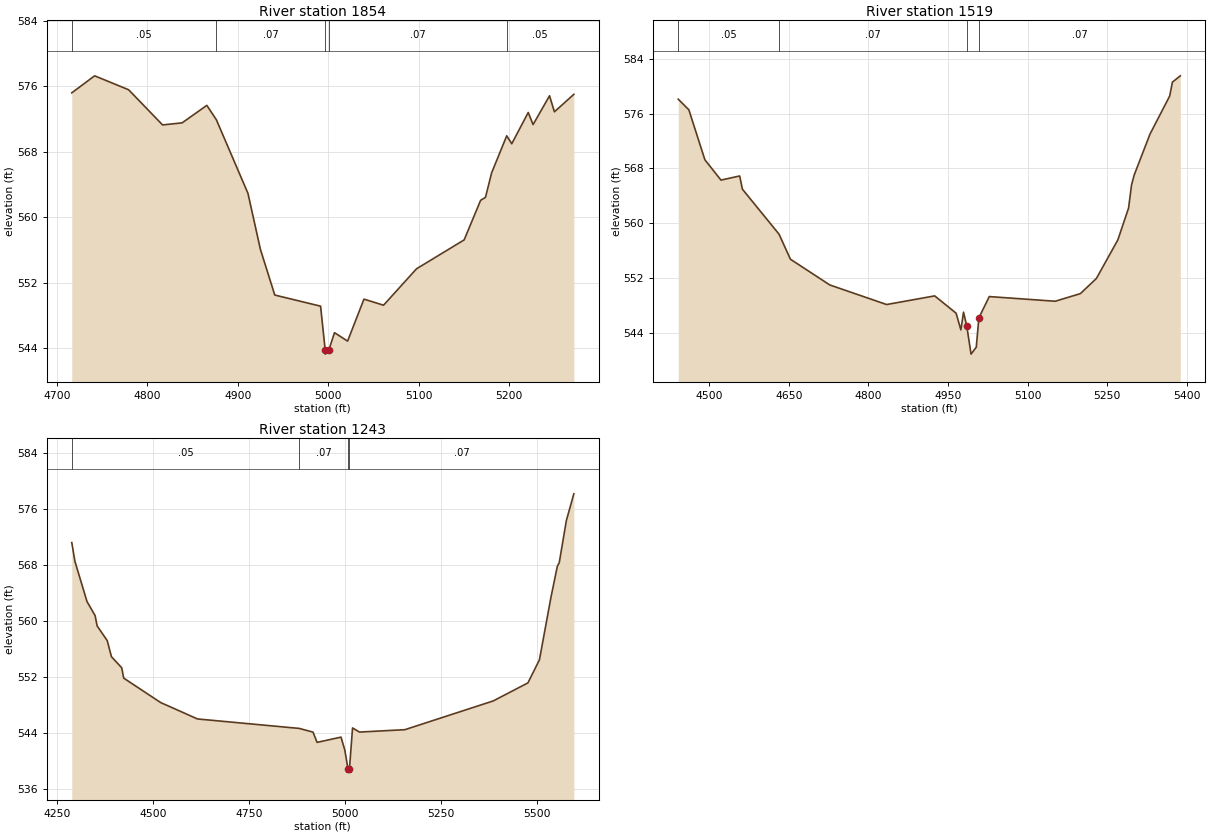
Type RM Length L Ch R = 1 ,1854    ,335,335,335
BEGIN DESCRIPTION:
Whites Branch Tr 1 2.0
END DESCRIPTION:
XS GIS Cut Line= 3
      2371724.81       7066159.9      2371585.42      7065912.69
      2371335.26      7065806.14
#Sta/Elev= 30
  4716.2   575.2  4741.5  577.28  4779.1  575.58  4816.7  571.28  4838.3  571.53
  4865.7  573.67  4876.2  571.92  4911.2  562.92    4925  556.07  4940.9  550.49
  4991.6  549.13  4996.7  543.77  4996.9  543.27  5000.7  543.77    5007  545.89
  5021.5  544.86  5039.6  549.99  5061.3  549.25  5097.8   553.7  5150.5  557.23
  5168.7  562.06  5174.1  562.43  5180.9  565.42  5197.6  569.95  5203.2  568.98
  5221.4   572.8  5226.8  571.32    5245  574.84  5250.4  572.88  5271.9  575.02
#Mann= 5 ,-1 , 0
  4716.2     .05       0  4876.2     .07       0  4996.7     .04       0
  5000.7     .07       0  5197.6     .05       0
Bank Sta=4996.7,5000.7
XS Rating Curve= 0 ,0
Exp/Cntr=0.3,0.1

Type RM Length L Ch R = 1 ,1519    ,276,276,276
BEGIN DESCRIPTION:
Mapping XS b8569f07
END DESCRIPTION:
XS GIS Cut Line= 3
      2371760.22      7066269.88      2371826.58      7065715.54
      2371442.42      7065662.51
#Sta/Elev= 30
  4441.7  578.09  4461.7  576.55  4491.9  569.27  4522.2  566.31  4557.5  566.91
  4562.6  564.99  4631.7  558.43  4653.1  554.79  4727.3  551.04  4834.4  548.19
    4925  549.45  4965.3  546.93  4974.3   544.5  4979.3  547.08  4985.4  545.06
  4993.5  540.97  5003.3  541.98  5008.3  546.26  5027.8  549.35  5152.1  548.67
  5199.5  549.78  5229.7  551.99  5270.1   557.6  5290.3  562.24  5295.9   565.6
    5301  567.07  5330.7  573.01  5367.8  578.55  5372.9  580.57  5387.8  581.49
#Mann= 4 ,-1 , 0
  4441.7     .05       0  4631.7     .07       0  4985.4     .04       0
  5008.3     .07       0
Bank Sta=4985.4,5008.3
XS Rating Curve= 0 ,0
Exp/Cntr=0.3,0.1

Type RM Length L Ch R = 1 ,1243    ,0,0,0
BEGIN DESCRIPTION:
Whites Branch Tr 1 1.0
END DESCRIPTION:
XS GIS Cut Line= 4
      2371853.68      7066287.81      2372065.12        7065634.
      2372064.03       7065568.9      2371509.52      7065597.11
#Sta/Elev= 30
  4288.4  571.16  4296.6  568.49  4328.1  562.75  4349.2  560.75  4354.4  559.29
  4380.7  557.19  4391.7   554.9  4418.5  553.31  4423.7  551.84  4519.8  548.36
  4615.8  546.02  4880.9  544.67  4916.7  544.14  4927.2  542.68  4989.6  543.43
  4999.6  541.55  5007.6  538.94  5007.8  538.44  5011.6  538.94  5019.6  544.74
  5037.6  544.15  5155.8  544.49  5386.1  548.59  5476.3  551.16  5506.3  554.45
  5536.3  563.36  5552.9  567.78  5557.9  568.29  5576.4   574.3  5595.9  578.11
#Mann= 4 ,-1 , 0
  4288.4     .05       0  4880.9     .07       0  5007.6     .04       0
  5011.6     .07       0
Bank Sta=5007.6,5011.6
XS Rating Curve= 0 ,0
Exp/Cntr=0.3,0.1

Chan Stop Cuts=-1
Use User Specified Reach Order=0
Composite Channel Slope=5