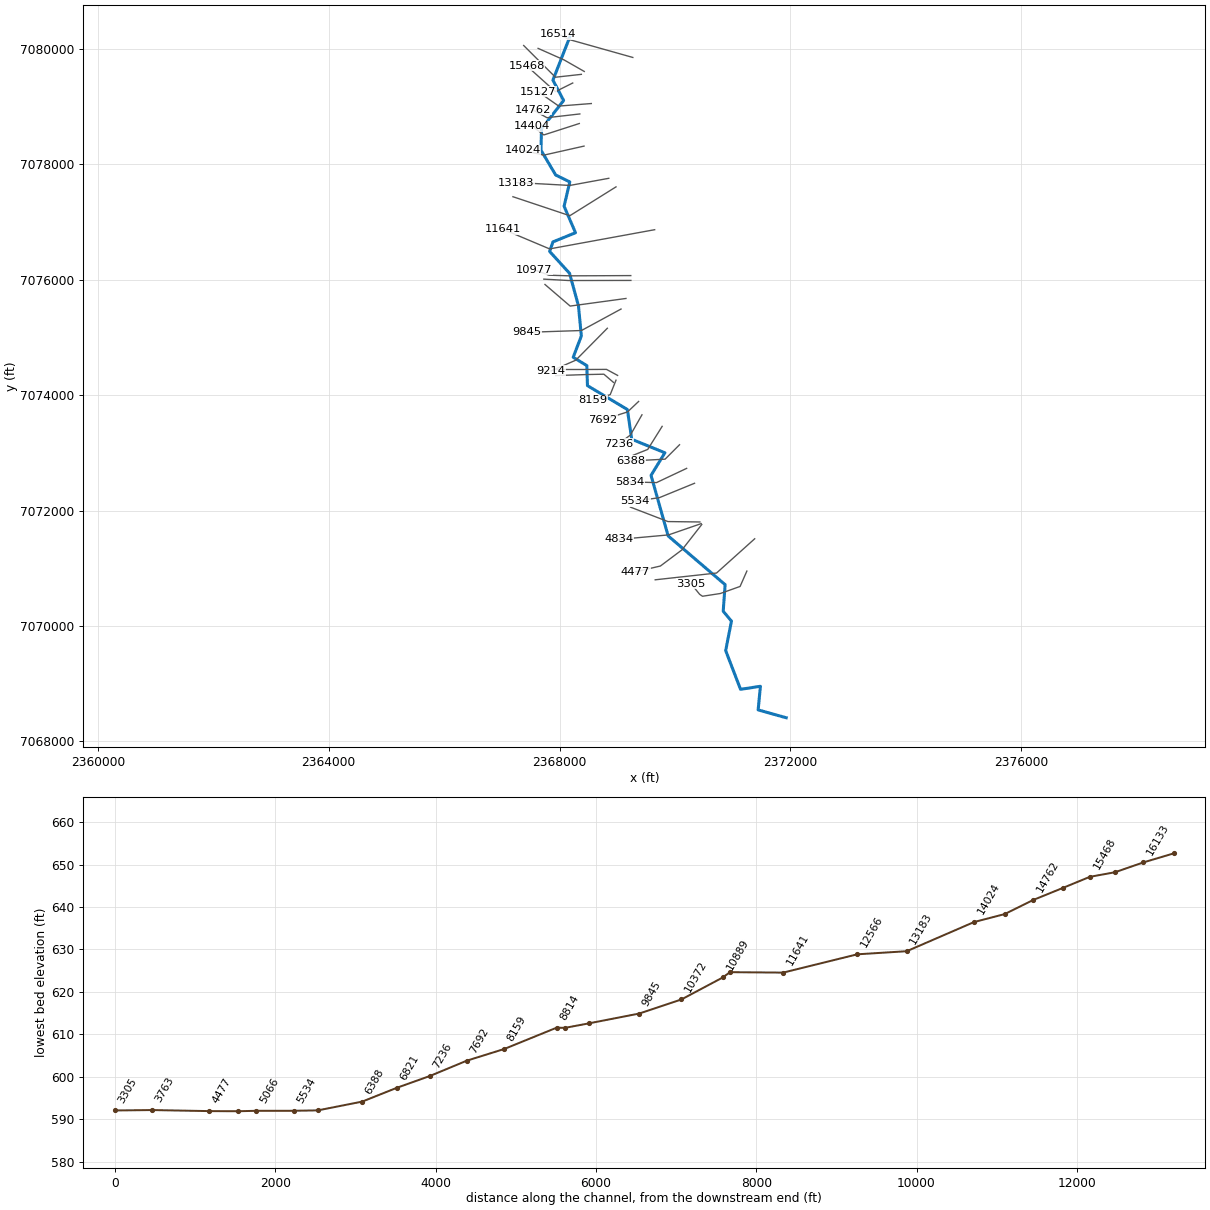
--- Whites Branch Tr 2_1.prj (project) ---

Proj Title=Whites Branch Tr 2_1 Base Level Engineering
Current Plan=p01
Default Exp/Contr=0.3,0.1
English Units
Geom File=g01
Flow File=f01
Plan File=p01
Y Axis Title=Elevation
X Axis Title(PF)=Main Channel Distance
X Axis Title(XS)=Station
BEGIN DESCRIPTION:
Whites Branch Tr 2_1
END DESCRIPTION:
DSS Export Rating Curves= 0
DSS Export Rating Curve Sorted= 0
DSS Export Volume Flow Curves= 0
DXF OffsetX= 0
DXF OffsetY= 0
DXF ScaleX= 1
DXF ScaleY= 10

--- Whites Branch Tr 2_1.p01 (plan) ---

Plan Title=Multiple Run
Short Identifier=Multiple
Geom File=g01
Flow File=f01
Subcritical Flow
K Sum by GR= 0
Std Step Tol= 0.01
Critical Tol= 0.01
Num of Std Step Trials= 20
Max Error Tol= 0.3
Flow Tol Ratio= 0.001
Split Flow NTrial= 30
Split Flow Tol= 0.02
Split Flow Ratio= 0.02
Log Output Level= 0
Friction Slope Method= 1
Unsteady Friction Slope Method= 2
Unsteady Bridges Friction Slope Method= 1
Parabolic Critical Depth
Global Vel Dist=  1 , 1 , 1
Global Log Level= 0
CheckData=True
Encroach Param= -1, 0, 0, 0
BEGIN DESCRIPTION:
Multiple Run
END DESCRIPTION:

--- Whites Branch Tr 2_1.f01 (steady flow) ---

Flow Title=Multiple
Program Version=4.10
Number of Profiles= 7
Profile Names=10-year,25-year,50-year,1pct_min,100-year,1pct_plu,500-year
River Rch & RM=Whites Branch Tr,Reach-1         ,16514
     413     552     664     397     792    1581    1129
River Rch & RM=Whites Branch Tr,Reach-1         ,15782
     630     863    1056     642    1280    2554    1884
River Rch & RM=Whites Branch Tr,Reach-1         ,12566
     719     991    1217     742    1480    2953    2193
River Rch & RM=Whites Branch Tr,Reach-1         ,9845
    1085    1526    1900    1172    2338    4664    3550
River Rch & RM=Whites Branch Tr,Reach-1         ,4834
    1270    1804    2260    1403    2798    5583    4303
Boundary for River Rch & Prof#=Whites Branch Tr,Reach-1         , 1
Up Type= 0
Dn Type= 3
Dn Slope=0.00943
Boundary for River Rch & Prof#=Whites Branch Tr,Reach-1         , 2
Up Type= 0
Dn Type= 3
Dn Slope=0.00943
Boundary for River Rch & Prof#=Whites Branch Tr,Reach-1         , 3
Up Type= 0
Dn Type= 3
Dn Slope=0.00943
Boundary for River Rch & Prof#=Whites Branch Tr,Reach-1         , 4
Up Type= 0
Dn Type= 3
Dn Slope=0.00943
Boundary for River Rch & Prof#=Whites Branch Tr,Reach-1         , 5
Up Type= 0
Dn Type= 3
Dn Slope=0.00943
Boundary for River Rch & Prof#=Whites Branch Tr,Reach-1         , 6
Up Type= 0
Dn Type= 3
Dn Slope=0.00943
Boundary for River Rch & Prof#=Whites Branch Tr,Reach-1         , 7
Up Type= 0
Dn Type= 3
Dn Slope=0.00943
DSS Import GetInterval= 0
DSS Import GetPeak= 0
DSS Import FillOption= 0

--- Whites Branch Tr 2_1.g01 (geometry) ---

Geom Title=Existing Conditions
Program Version=4.10

River Reach=Whites Branch Tr,Reach-1
Reach XY= 30
        2368179.        7080210.      2367886.11        7079460.
      2368071.38      7079106.67       2367688.4      7078616.66
      2367678.56      7078246.18      2367934.01      7077815.01
      2368178.49      7077696.13      2368079.39      7077275.16
      2368276.92      7076815.24      2367887.02      7076656.68
      2367828.26      7076491.66      2368173.67      7076112.66
      2368328.24      7075550.22      2368378.51      7075025.22
      2368236.99      7074656.65      2368473.72      7074512.71
      2368484.41      7074165.17      2369175.77      7073751.99
      2369251.86      7073236.16       2369826.1      7073002.09
      2369586.09        7072610.      2369882.54      7071561.46
      2370869.89      7070716.73       2370836.8      7070256.58
      2370979.51      7070085.04      2370879.68      7069573.92
      2371136.81      7068903.17      2371481.59      7068955.03
      2371442.24      7068546.25        2371929.        7068410.

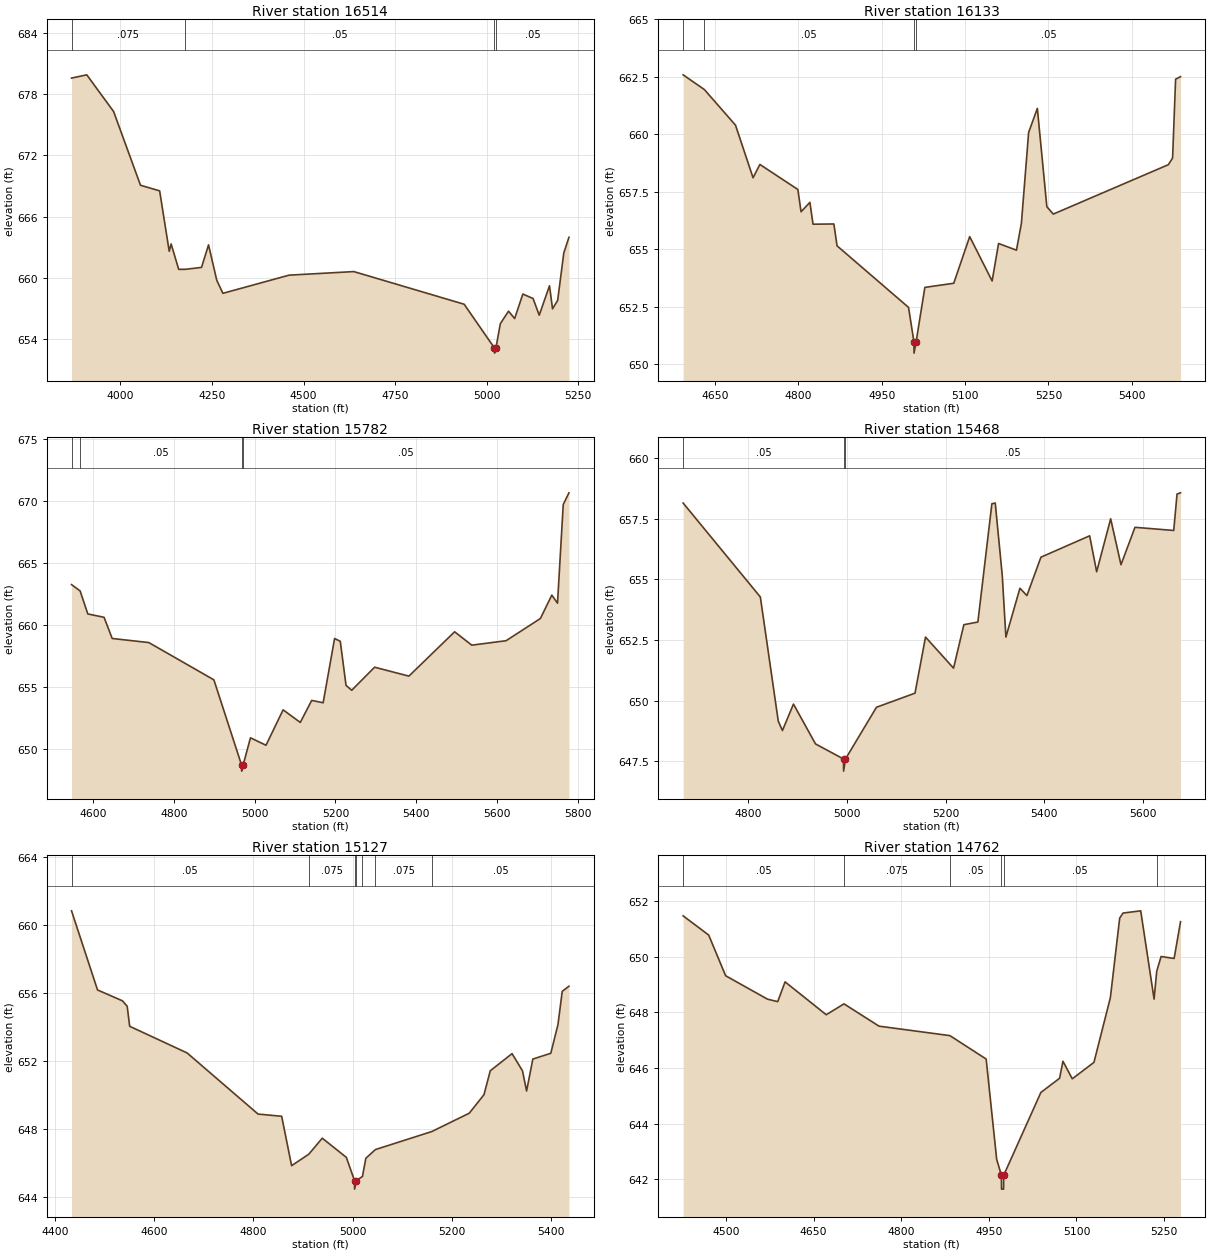
Type RM Length L Ch R = 1 ,16514   ,381,381,381
BEGIN DESCRIPTION:
Whites Branch Tr 2_1 33.0
END DESCRIPTION:
XS GIS Cut Line= 3
      2369270.53      7079852.72        2368179.        7080160.
      2367978.97      7080260.02
#Sta/Elev= 30
  3866.7  679.57  3908.3  679.89  3981.6  676.29  4054.9  669.07  4107.2  668.52
  4133.3   662.6  4138.5  663.32  4159.2  660.83  4176.7  660.83  4221.5  661.02
  4240.6  663.23  4263.1  659.76  4279.8  658.48  4460.4  660.26  4637.1  660.61
  4938.3  657.41    5021  653.12  5021.3  652.62    5025  653.12    5037   655.5
  5059.4  656.73  5076.1  656.01  5098.5  658.41  5126.4  657.97  5143.2  656.34
  5171.2  659.22  5179.5  656.96  5193.5  657.79  5210.3  662.45  5224.3  663.97
#Mann= 4 ,-1 , 0
  3866.7    .075       0  4176.7     .05       0    5021     .05       0
    5025     .05       0
Bank Sta=5021,5025
XS Rating Curve= 0 ,0
Exp/Cntr=0.3,0.1

Type RM Length L Ch R = 1 ,16133   ,351,351,351
BEGIN DESCRIPTION:
Whites Branch Tr 2_1 32.0
END DESCRIPTION:
XS GIS Cut Line= 3
      2368428.98      7079610.01        2368079.        7079810.
      2367629.03      7080009.99
#Sta/Elev= 30
  4592.4  662.59  4630.6  661.95  4686.7   660.4  4718.3  658.11  4730.6  658.69
    4799   657.6  4804.7  656.63  4820.6  657.04  4826.3  656.09  4863.8   656.1
  4869.5  655.15  4998.2  652.47  5007.9  650.98  5008.1  650.48  5011.9  650.98
  5027.6  653.34  5079.6  653.52  5108.3  655.55  5148.7  653.62  5160.3  655.25
  5192.5  654.96  5201.4  656.13  5214.4  660.08  5230.1  661.13  5247.2  656.85
  5258.8  656.53    5466  658.68  5473.6  658.97    5479   662.4  5487.9  662.51
#Mann= 4 ,-1 , 0
  4592.4    .075       0  4630.6     .05       0  5007.9     .05       0
  5011.9     .05       0
Bank Sta=5007.9,5011.9
XS Rating Curve= 0 ,0
Exp/Cntr=0.3,0.1

Type RM Length L Ch R = 1 ,15782   ,314,314,314
BEGIN DESCRIPTION:
Whites Branch Tr 2_1 31.0
END DESCRIPTION:
XS GIS Cut Line= 3
      2368379.03        7079560.        2367929.        7079510.
      2367379.01      7080059.99
#Sta/Elev= 30
  4547.1  663.24  4568.3  662.73  4587.4  660.87  4627.6   660.6  4647.7  658.89
  4738.3  658.56  4899.3  655.55  4967.7  648.68    4968  648.18  4971.7  648.68
  4989.8  650.87  5028.2  650.27  5070.6  653.13    5113  652.11  5141.3  653.89
  5169.6   653.7  5197.9  658.89    5212  658.66  5226.2   655.1  5240.3  654.71
  5296.9  656.57  5381.7  655.85  5494.9  659.43  5537.3  658.35  5622.2  658.71
    5707   660.5  5735.3  662.39  5749.4  661.74  5763.6  669.71  5777.7  670.65
#Mann= 4 ,-1 , 0
  4547.1    .075       0  4568.3     .05       0  4967.7     .05       0
  4971.7     .05       0
Bank Sta=4967.7,4971.7
XS Rating Curve= 0 ,0
Exp/Cntr=0.3,0.1

Type RM Length L Ch R = 1 ,15468   ,341,341,341
BEGIN DESCRIPTION:
Whites Branch Tr 2_1 30.0
END DESCRIPTION:
XS GIS Cut Line= 3
      2368228.96      7079409.98        2367929.        7079260.
      2367429.03      7079709.97
#Sta/Elev= 30
  4668.2  658.14  4824.7  654.27    4861  649.16  4869.4  648.77  4891.8  649.86
  4936.5  648.22  4993.2   647.6  4993.4   647.1  4997.2   647.6    5060  649.73
  5138.1  650.31  5159.4  652.62  5216.2  651.34  5237.1  653.13  5265.5  653.24
  5293.9  658.11  5300.7  658.14  5314.9  655.16  5322.3  652.62  5350.7  654.63
  5364.9  654.33  5393.3  655.91    5492  656.79  5506.2  655.31  5534.6  657.49
  5555.5   655.6  5583.9  657.14  5662.4  657.01  5669.1  658.51  5676.2  658.56
#Mann= 3 ,-1 , 0
  4668.2     .05       0  4993.2    .033       0  4997.2     .05       0
Bank Sta=4993.2,4997.2
XS Rating Curve= 0 ,0
Exp/Cntr=0.3,0.1

Type RM Length L Ch R = 1 ,15127   ,365,365,365
BEGIN DESCRIPTION:
Whites Branch Tr 2_1 29.0
END DESCRIPTION:
XS GIS Cut Line= 3
      2368551.27       7079054.1      2367986.59      7079009.99
      2367629.02      7079259.99
#Sta/Elev= 30
  4433.6  660.84    4486  656.18  4536.2  655.54  4545.8  655.22  4550.8  654.04
  4666.6  652.47  4809.6  648.87  4857.2  648.74  4877.2  645.83    4912  646.51
    4939  647.45  4987.6  646.32    5004  644.95  5004.2  644.45    5008  644.95
  5020.1   645.2  5026.9  646.27  5046.2  646.78  5159.7  647.84  5235.3  648.92
    5265  650.01  5277.7  651.42  5321.6  652.43  5342.6  651.42  5350.9  650.23
  5363.5  652.11  5399.7  652.45  5414.1  654.13  5422.8   656.1  5436.3   656.4
#Mann= 7 ,-1 , 0
  4433.6     .05       0    4912    .075       0    5004     .07       0
    5008    .075       0  5020.1     .05       0  5046.2    .075       0
  5159.7     .05       0
Bank Sta=5004,5008
XS Rating Curve= 0 ,0
Exp/Cntr=0.3,0.1

Type RM Length L Ch R = 1 ,14762   ,358,358,358
BEGIN DESCRIPTION:
Whites Branch Tr 2_1 28.0
END DESCRIPTION:
XS GIS Cut Line= 3
      2368352.51      7078873.72      2367782.63      7078808.45
      2367539.38      7078943.65
#Sta/Elev= 30
  4426.4  651.46  4470.2  650.77  4499.2  649.31  4570.8  648.47  4588.4  648.38
    4601  649.09  4671.5  647.91  4701.9   648.3  4761.9   647.5  4883.3  647.16
  4945.4  646.32  4963.4  642.72  4971.5  642.15  4971.7  641.65  4975.2  641.65
  4975.5  642.15  5039.1  645.12  5071.2  645.63  5076.9  646.24  5092.9  645.61
    5130   646.2  5158.1  648.52  5174.1  651.38  5179.8  651.56  5210.1  651.64
    5233  648.47  5237.5  649.47    5245     650  5267.3  649.93  5278.3  651.25
#Mann= 6 ,-1 , 0
  4426.4     .05       0  4701.9    .075       0  4883.3     .05       0
  4971.5     .05       0  4975.5     .05       0  5237.5    .075       0
Bank Sta=4971.5,4975.5
XS Rating Curve= 0 ,0
Exp/Cntr=0.3,0.1

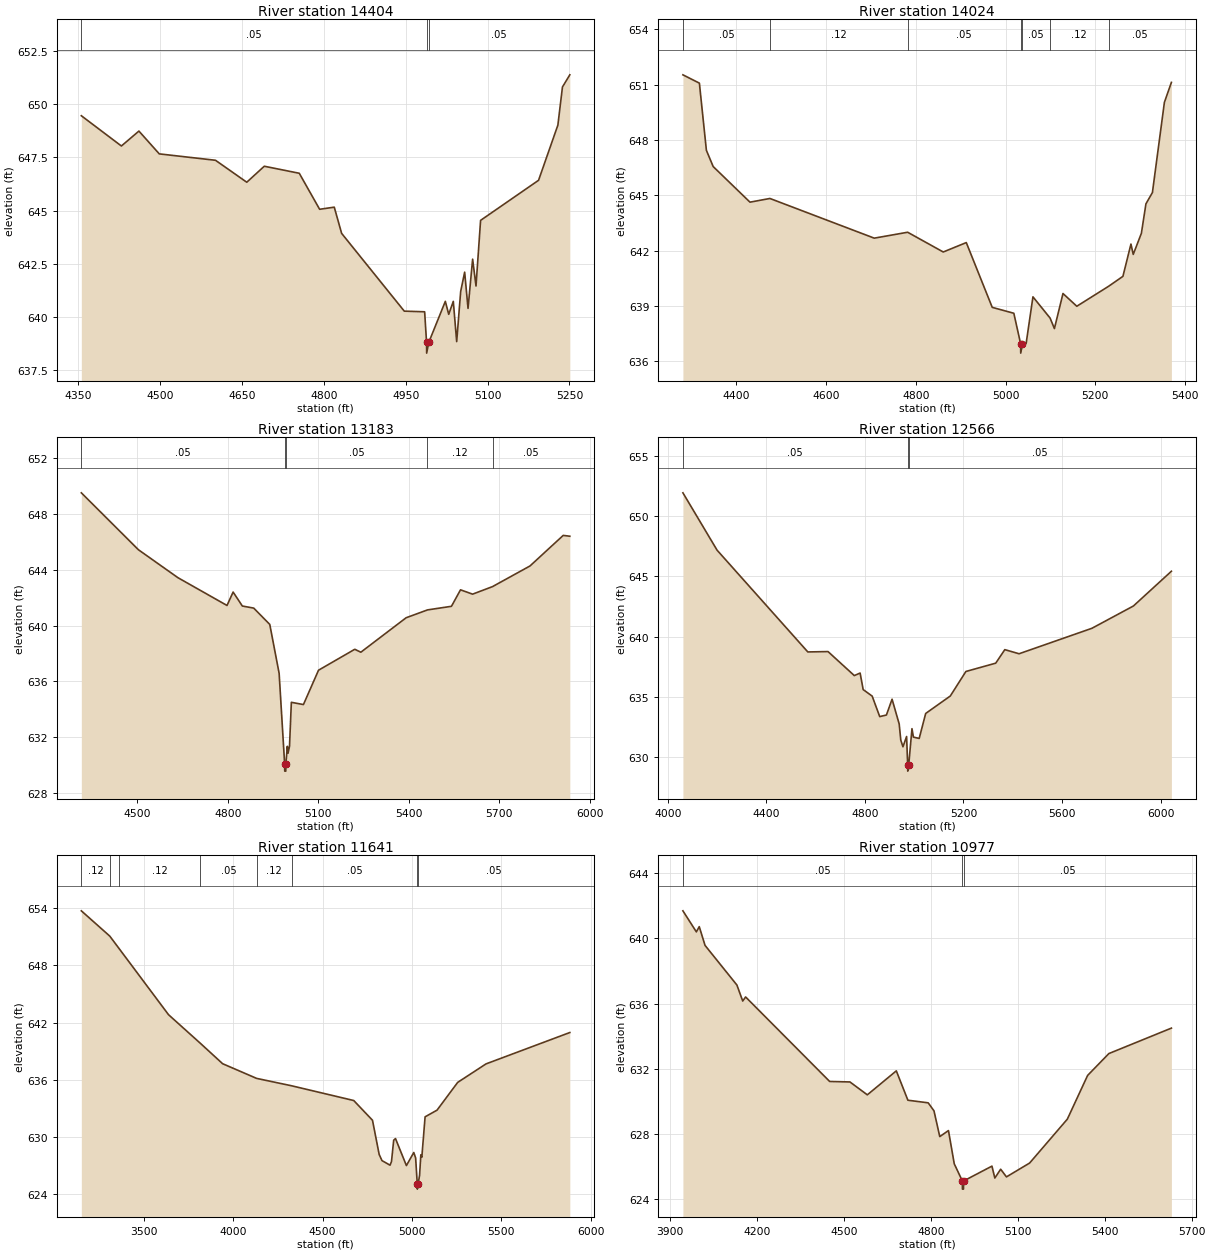
Type RM Length L Ch R = 1 ,14404   ,380,380,380
BEGIN DESCRIPTION:
Whites Branch Tr 2_1 27.0
END DESCRIPTION:
XS GIS Cut Line= 3
      2368342.92      7078707.81        2367729.        7078510.
        2367529.        7078660.
#Sta/Elev= 30
  4355.8  649.45  4429.2  648.03  4461.3  648.73  4498.6  647.66  4601.6  647.36
  4658.9  646.33    4691  647.08  4755.1  646.75  4792.4  645.06  4819.2  645.16
  4832.7  643.93  4947.5  640.28  4984.8  640.25  4988.3  638.81  4988.5  638.31
  4992.3  638.81  5022.7  640.74  5028.9  640.13  5037.3  640.74  5043.5  638.85
  5050.8   641.2  5058.1  642.11  5064.3  640.41  5072.7  642.72  5078.9  641.46
  5087.3  644.54  5193.5  646.42  5228.9  649.01  5237.3   650.8  5250.8  651.37
#Mann= 3 ,-1 , 0
  4355.8     .05       0  4988.3    .033       0  4992.3     .05       0
Bank Sta=4988.3,4992.3
XS Rating Curve= 0 ,0
Exp/Cntr=0.3,0.1

Type RM Length L Ch R = 1 ,14024   ,841,841,841
BEGIN DESCRIPTION:
Whites Branch Tr 2_1 26.0
END DESCRIPTION:
XS GIS Cut Line= 3
       2368424.8      7078316.51        2367729.        7078160.
      2367363.81      7078244.83
#Sta/Elev= 30
  4281.4  651.53  4318.1  651.08  4333.7  647.44  4348.8  646.56  4430.8  644.63
  4475.2  644.83  4707.6  642.68    4782     643  4861.3  641.93  4912.6  642.44
  4970.4  638.93  5018.5  638.61  5033.7  636.95  5033.9  636.45  5037.7  636.95
  5045.9  636.97  5061.1   639.5  5099.3  638.35  5108.9  637.78    5128  639.68
  5158.8  638.99  5229.5  640.07  5261.5  640.61  5279.4  642.36  5284.5   641.8
  5302.6  642.94  5312.8  644.54  5327.2  645.15  5353.9  650.04  5369.5  651.12
#Mann= 7 ,-1 , 0
  4281.4     .05       0  4475.2     .12       0    4782     .05       0
  5033.7    .033       0  5037.7     .05       0  5099.3     .12       0
  5229.5     .05       0
Bank Sta=5033.7,5037.7
XS Rating Curve= 0 ,0
Exp/Cntr=0.3,0.1

Type RM Length L Ch R = 1 ,13183   ,617,617,617
BEGIN DESCRIPTION:
Whites Branch Tr 2_1 25.0
END DESCRIPTION:
XS GIS Cut Line= 3
      2368853.95      7077758.51       2368179.5      7077634.82
      2367247.18      7077685.59
#Sta/Elev= 30
  4314.3  649.51  4503.7  645.43  4634.5  643.43  4797.2  641.44  4817.5   642.4
    4848   641.4  4885.8  641.25    4939  640.08    4970  636.58  4988.3  630.07
  4988.6  629.57  4992.1  629.57  4992.3  630.07  4997.2  631.35  4999.5  630.85
  5004.4  631.35  5010.5   634.5  5050.6  634.34  5100.6   636.8  5220.8   638.3
  5240.9  638.09  5391.1  640.56  5461.7  641.12  5541.3  641.38  5571.3  642.56
  5611.4  642.25  5677.4  642.79  5801.7  644.27  5911.8  646.46  5933.7   646.4
#Mann= 5 ,-1 , 0
  4314.3     .05       0  4988.3    .033       0  4992.3     .05       0
  5461.7     .12       0  5677.4     .05       0
Bank Sta=4988.3,4992.3
XS Rating Curve= 0 ,0
Exp/Cntr=0.3,0.1

Type RM Length L Ch R = 1 ,12566   ,925,925,925
BEGIN DESCRIPTION:
Whites Branch Tr 2_1 24.0
END DESCRIPTION:
XS GIS Cut Line= 3
      2368979.03      7077610.02        2368179.        7077110.
      2367192.88      7077439.36
#Sta/Elev= 30
    4061  651.91  4199.6  647.16  4568.1  638.72  4650.1  638.75  4756.8  636.76
  4780.4  636.97  4792.8   635.6  4829.3  635.06    4860  633.36  4887.1  633.49
  4910.1   634.8    4939  632.75  4945.5  631.41  4954.3  630.86  4969.1  631.71
  4973.5  629.34  4973.8  628.84  4977.6  629.34  4990.9  632.36  4996.8  631.66
  5020.2  631.55  5046.6  633.62  5146.6  635.07  5209.8   637.1  5330.9  637.79
  5367.8  638.91  5425.7  638.57  5721.4  640.68    5890  642.53  6044.1  645.41
#Mann= 3 ,-1 , 0
    4061     .05       0  4973.5    .033       0  4977.6     .05       0
Bank Sta=4973.5,4977.6
XS Rating Curve= 0 ,0
Exp/Cntr=0.3,0.1

Type RM Length L Ch R = 1 ,11641   ,664,664,664
BEGIN DESCRIPTION:
Whites Branch Tr 2_1 23.0
END DESCRIPTION:
XS GIS Cut Line= 3
      2369649.12      7076867.71      2367828.57        7076535.
      2367013.86      7076878.08
#Sta/Elev= 30
  3149.3  653.71  3308.4  651.06    3360  649.77  3637.4  642.82  3816.2  639.81
  3940.2  637.68  4130.7  636.14  4327.8  635.36  4674.3  633.82  4779.3  631.75
  4816.6  628.17  4832.5  627.52  4877.6  627.04  4885.7  627.43  4897.9  629.66
  4908.1  629.83  4969.1     627  5010.4  628.37  5020.8   627.8    5030  625.03
  5030.3  624.53  5034.2  625.03  5042.9  625.98  5049.9  628.13  5055.4  627.87
  5073.7  632.11  5140.6  632.81  5256.1  635.72  5414.8  637.66    5884  640.95
#Mann= 8 ,-1 , 0
  3149.3     .12       0  3308.4     .05       0    3360     .12       0
  3816.2     .05       0  4130.7     .12       0  4327.8     .05       0
    5030    .033       0  5034.2     .05       0
Bank Sta=5030,5034.2
XS Rating Curve= 0 ,0
Exp/Cntr=0.3,0.1

Type RM Length L Ch R = 1 ,10977   ,88,88,88
BEGIN DESCRIPTION:
Mapping XS 7c14ed7e
END DESCRIPTION:
XS GIS Cut Line= 4
      2369235.42      7076072.53       2368182.9      7076068.19
      2367818.32      7076079.04      2367566.63      7076172.34
#Sta/Elev= 30
  3944.4  641.69  3990.8   640.4  4000.8  640.72  4020.8  639.57  4130.8  637.14
  4150.8  636.16  4160.8  636.41  4450.8  631.23  4520.8   631.2  4580.8  630.41
  4680.8  631.88  4720.8  630.08  4790.8  629.92  4810.8  629.43  4830.8  627.85
  4860.8  628.22  4880.8  626.18  4908.7  625.13    4909  624.63  4912.6  624.63
    4913  625.13  5010.8  626.04  5020.8  625.31  5040.9  625.85  5060.9  625.38
  5140.9  626.23    5271  628.92    5341   631.6  5414.3  632.94  5630.1   634.5
#Mann= 3 ,-1 , 0
  3944.4     .05       0  4908.7     .04       0    4913     .05       0
Bank Sta=4908.7,4913
XS Rating Curve= 0 ,0
Exp/Cntr=0.3,0.1

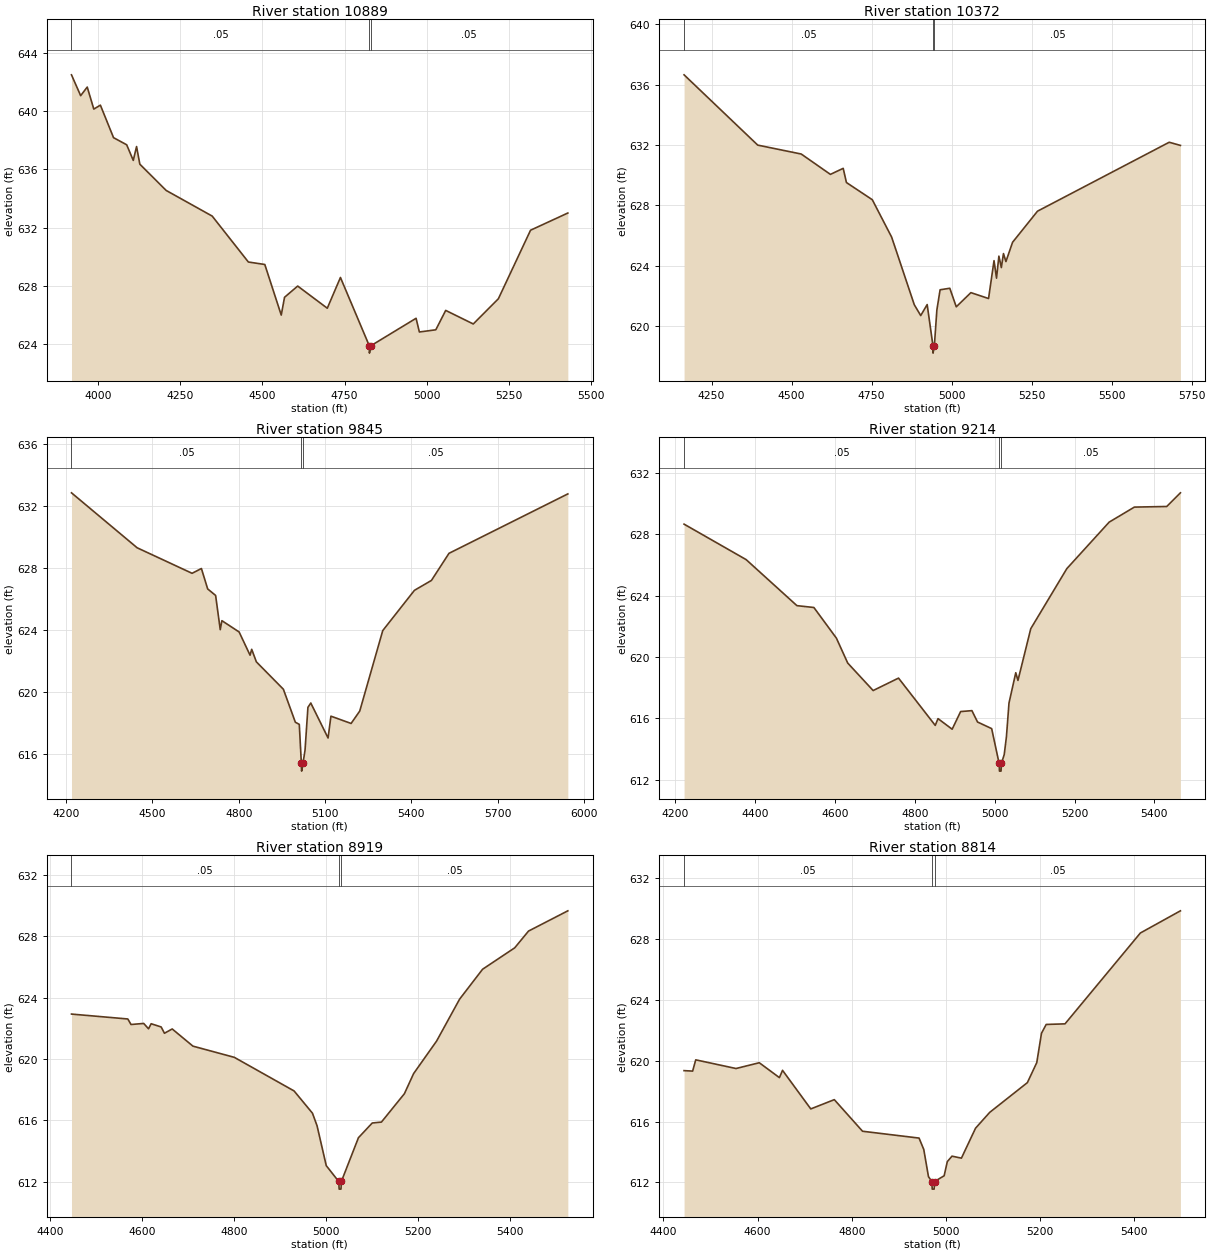
Type RM Length L Ch R = 1 ,10889   ,517,517,517
BEGIN DESCRIPTION:
Mapping XS cc50cf89
END DESCRIPTION:
XS GIS Cut Line= 3
      2369236.88      7075988.65      2368160.44      7075986.92
      2367728.16      7076011.22
#Sta/Elev= 30
  3919.2  642.49  3947.1  641.06  3967.1  641.65  3987.1  640.14  4007.1  640.41
  4047.1  638.18  4087.1  637.69  4107.1  636.62  4117.1  637.57  4127.1  636.36
  4207.1  634.56  4347.1   632.8  4457.1  629.65  4507.1  629.48  4557.1  626.01
  4567.1  627.23  4607.1     628  4697.1  626.48  4737.1  628.59  4824.9   623.9
  4825.3   623.4  4829.2   623.9  4967.1  625.79  4977.1  624.85  5027.1     625
  5057.2  626.33    5141   625.4  5217.4  627.13  5315.2  631.83  5428.6  633.01
#Mann= 3 ,-1 , 0
  3919.2     .05       0  4824.9     .04       0  4829.2     .05       0
Bank Sta=4824.9,4829.2
XS Rating Curve= 0 ,0
Exp/Cntr=0.3,0.1

Type RM Length L Ch R = 1 ,10372   ,527,527,527
BEGIN DESCRIPTION:
Whites Branch Tr 2_1 21.0
END DESCRIPTION:
XS GIS Cut Line= 3
      2369151.76      7075676.15      2368184.31      7075544.21
      2367748.26      7075918.54
#Sta/Elev= 30
  4163.9  636.66  4394.1     632    4530  631.41  4621.2  630.06  4661.2  630.46
  4671.3  629.52  4752.1  628.38  4812.6   625.9  4883.3  621.42  4903.4   620.7
  4923.6  621.43  4941.6  618.71    4942  618.21  4946.1  618.71  4953.9  621.07
    4964  622.41  4994.3  622.51  5014.5  621.28  5060.2  622.22  5115.4  621.83
  5132.5  624.34  5140.3  623.18  5147.7  624.64  5155.4  623.88    5162  624.81
  5169.7  624.28  5190.5  625.56  5268.4  627.62    5680  632.19    5715  631.98
#Mann= 3 ,-1 , 0
  4163.9     .05       0  4941.6     .04       0  4946.1     .05       0
Bank Sta=4941.6,4946.1
XS Rating Curve= 0 ,0
Exp/Cntr=0.3,0.1

Type RM Length L Ch R = 1 ,9845    ,631,631,631
BEGIN DESCRIPTION:
Whites Branch Tr 2_1 20.0
END DESCRIPTION:
XS GIS Cut Line= 3
      2369066.23      7075492.99      2368380.82      7075120.81
      2367436.08      7075089.36
#Sta/Elev= 30
  4218.7  632.86  4446.9  629.31  4637.9  627.66  4670.3  627.97  4692.1  626.65
  4719.7  626.23  4735.8  624.02  4741.5   624.6  4801.4  623.87  4839.4  622.37
  4845.1  622.75  4861.3  621.94  4955.2  620.17  4996.8  618.04  5010.5   617.9
  5017.7  615.38  5018.5  614.88  5023.3  615.38  5030.5  616.24  5040.5     619
  5050.5  619.28  5110.5  617.02  5120.5  618.43  5190.6  617.96  5220.6  618.76
  5300.6  623.96  5410.7  626.56  5469.8   627.2  5530.8  628.95  5943.9  632.79
#Mann= 3 ,-1 , 0
  4218.7     .05       0  5017.7     .04       0  5023.3     .05       0
Bank Sta=5017.7,5023.3
XS Rating Curve= 0 ,0
Exp/Cntr=0.3,0.1

Type RM Length L Ch R = 1 ,9214    ,295,295,295
BEGIN DESCRIPTION:
Whites Branch Tr 2_1 19.0
END DESCRIPTION:
XS GIS Cut Line= 3
        2368829.        7075160.      2368281.82      7074606.38
      2367855.33      7074420.09
#Sta/Elev= 30
  4221.6  628.65  4377.1  626.34  4504.4  623.34  4546.9  623.22  4603.4  621.22
  4631.7   619.6  4695.4  617.81    4759  618.62    4851  615.54    4858  615.98
  4893.4  615.29  4914.6  616.44  4942.9   616.5    4957  615.76  4992.4  615.33
  5011.1  613.06    5012  612.56  5015.9  612.56  5016.8  613.06  5023.9  613.64
  5029.4   614.8  5035.8  616.99  5052.8  618.97  5058.3  618.47  5090.4  621.84
  5180.7  625.75  5286.8  628.78    5350  629.76  5431.1   629.8  5465.4  630.69
#Mann= 3 ,-1 , 0
  4221.6     .05       0  5011.1     .04       0  5016.8     .05       0
Bank Sta=5011.1,5016.8
XS Rating Curve= 0 ,0
Exp/Cntr=0.3,0.1

Type RM Length L Ch R = 1 ,8919    ,105,105,105
BEGIN DESCRIPTION:
Mapping XS 14dccb10
END DESCRIPTION:
XS GIS Cut Line= 4
      2369006.88      7074342.85      2368814.15      7074447.03
      2368472.14      7074445.29      2367953.54      7074445.29
#Sta/Elev= 30
  4446.5  622.92  4569.1   622.6    4576  622.24  4603.6  622.31  4614.1  621.96
  4619.8  622.29  4641.6  622.08  4648.7  621.67  4665.6  621.95  4710.7  620.83
  4800.7   620.1  4930.7  617.91  4970.7  616.46  4980.7  615.64  5000.7  613.04
  5027.8  612.01  5028.8  611.51  5032.7  611.51  5033.6  612.01  5070.7  614.86
  5100.7  615.82  5120.7  615.88  5170.7  617.73  5190.7  619.04  5240.7  621.16
  5290.7  623.89  5340.7  625.84  5410.7  627.24  5440.7  628.33  5526.2  629.65
#Mann= 3 ,-1 , 0
  4446.5     .05       0  5027.8     .04       0  5033.6     .05       0
Bank Sta=5027.8,5033.6
XS Rating Curve= 0 ,0
Exp/Cntr=0.3,0.1

Type RM Length L Ch R = 1 ,8814    ,655,655,655
BEGIN DESCRIPTION:
Mapping XS 2228170e
END DESCRIPTION:
XS GIS Cut Line= 4
      2368935.68      7074221.34      2368769.01       7074363.7
      2368435.68      7074356.75      2367933.97      7074339.39
#Sta/Elev= 30
  4443.8  619.35    4462  619.32  4468.6  620.06  4554.2  619.49  4603.6  619.87
  4646.4  618.89    4653  619.37    4713  616.83    4763  617.44    4823  615.36
  4943.1  614.91  4953.1  614.16  4963.1  612.37  4970.2  612.05  4971.1  611.55
  4975.1  611.55    4976  612.05  4996.4  612.43  5003.1  613.36  5013.1  613.72
  5033.1  613.59  5063.1  615.56  5093.1   616.6  5173.2  618.56  5193.2  619.88
  5203.2  621.81  5213.2  622.39  5253.2  622.43  5413.3  628.41  5498.4  629.87
#Mann= 3 ,-1 , 0
  4443.8     .05       0  4970.2     .04       0    4976     .05       0
Bank Sta=4970.2,4976
XS Rating Curve= 0 ,0
Exp/Cntr=0.3,0.1

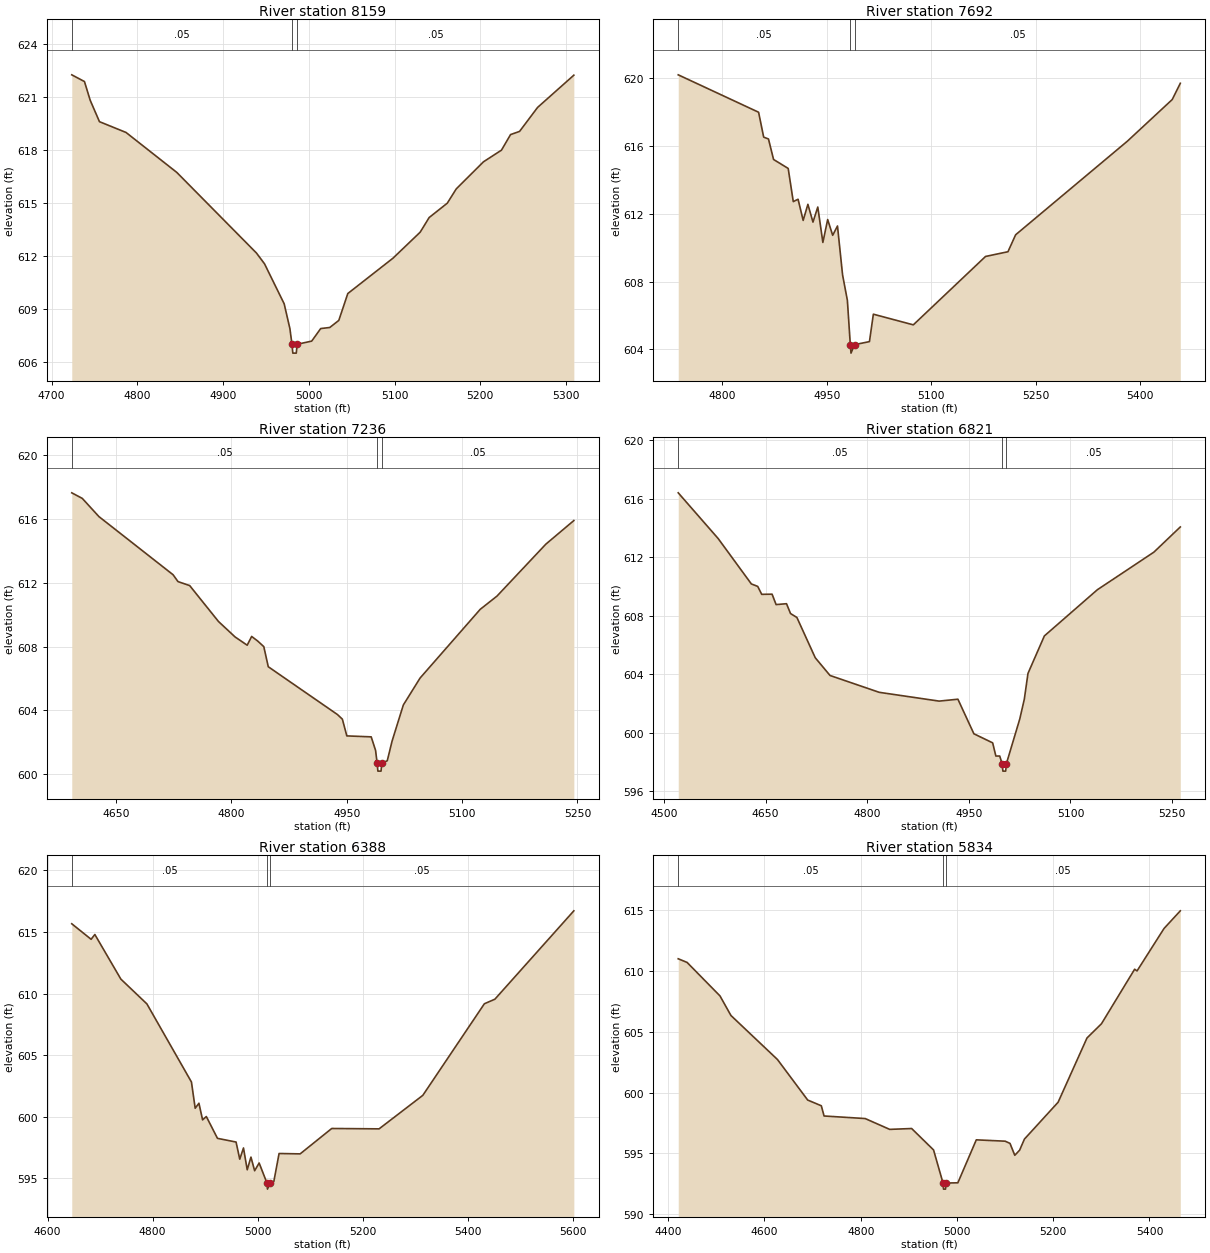
Type RM Length L Ch R = 1 ,8159    ,467,467,467
BEGIN DESCRIPTION:
Whites Branch Tr 2_1 17.0
END DESCRIPTION:
XS GIS Cut Line= 3
      2368978.99      7074259.98        2368879.        7074010.
      2368578.97      7073909.99
#Sta/Elev= 30
  4723.6  622.26  4738.4  621.88  4745.1  620.82  4755.9  619.61  4786.9     619
  4846.1  616.74    4939  612.18  4948.4  611.57  4971.3  609.31    4978   607.9
  4980.4  607.02  4981.4  606.52  4985.4  606.52  4986.4  607.02  5003.4   607.2
  5013.9  607.91  5024.5  607.97    5035  608.37  5045.5  609.89  5098.2  611.89
  5129.9  613.36  5140.4  614.19  5161.5     615    5172  615.81  5203.7  617.34
  5224.7     618  5235.3  618.88  5245.8  619.06  5266.9  620.42  5309.1  622.24
#Mann= 3 ,-1 , 0
  4723.6     .05       0  4980.4     .04       0  4986.4     .05       0
Bank Sta=4980.4,4986.4
XS Rating Curve= 0 ,0
Exp/Cntr=0.3,0.1

Type RM Length L Ch R = 1 ,7692    ,456,456,456
BEGIN DESCRIPTION:
Whites Branch Tr 2_1 16.0
END DESCRIPTION:
XS GIS Cut Line= 3
      2369370.93      7073891.43        2369179.        7073710.
      2368743.69      7073571.24
#Sta/Elev= 30
  4736.7  620.21  4852.1     618  4859.4  616.53  4866.3  616.42  4873.6  615.21
  4894.6  614.68  4901.9  612.72  4908.8  612.86  4916.1  611.61  4922.9  612.56
  4930.2  611.51  4937.1   612.4  4944.4  610.31  4951.3  611.66  4958.5  610.73
  4965.4  611.28  4972.7  608.39  4979.6  606.89  4983.8  604.27  4984.8  603.77
  4989.9  604.27  5011.3  604.45  5016.9  606.07  5074.3  605.44    5178  609.48
  5210.2  609.76  5221.2  610.76  5381.7  616.29  5446.1  618.75  5457.7  619.71
#Mann= 3 ,-1 , 0
  4736.7     .05       0  4983.8     .04       0  4989.9     .05       0
Bank Sta=4983.8,4989.9
XS Rating Curve= 0 ,0
Exp/Cntr=0.3,0.1

Type RM Length L Ch R = 1 ,7236    ,415,415,415
BEGIN DESCRIPTION:
Whites Branch Tr 2_1 15.0
END DESCRIPTION:
XS GIS Cut Line= 3
      2369429.01      7073660.02        2369229.        7073310.
      2369029.03      7073160.02
#Sta/Elev= 30
  4592.3  617.65    4606   617.3  4627.6  616.16  4724.1  612.51  4730.5  612.08
  4745.7  611.83  4783.1  609.58  4804.7  608.61  4820.5  608.09  4826.3  608.64
  4834.2  608.35  4842.1     608  4847.9  606.74  4937.9  603.74  4944.3  603.45
  4950.1   602.4  4981.8  602.34  4987.5  601.49  4989.5  600.69  4990.5  600.19
  4994.6  600.19  4995.6  600.69  5002.7  600.84    5009  602.08  5023.6  604.34
  5045.4  606.03  5123.6  610.34  5145.4  611.17    5209  614.43  5245.4  615.91
#Mann= 3 ,-1 , 0
  4592.3     .05       0  4989.5     .04       0  4995.6     .05       0
Bank Sta=4989.5,4995.6
XS Rating Curve= 0 ,0
Exp/Cntr=0.3,0.1

Type RM Length L Ch R = 1 ,6821    ,433,433,433
BEGIN DESCRIPTION:
Whites Branch Tr 2_1 14.0
END DESCRIPTION:
XS GIS Cut Line= 3
      2369778.99      7073459.98        2369529.        7073060.
      2369279.03      7072960.01
#Sta/Elev= 30
  4521.2  616.39  4580.1  613.27  4629.1  610.17  4638.5     610  4644.4  609.46
  4659.7  609.47  4665.6  608.76    4681  608.82  4686.9  608.15  4696.3  607.88
  4723.4  605.13  4745.2  603.92  4817.8  602.77  4906.2  602.17  4933.9   602.3
  4957.5  599.94  4985.2  599.32  4989.9  598.42  4995.6  598.42  4999.2  597.89
  5000.3  597.39  5004.4  597.39  5005.4  597.89  5025.2  600.95  5031.9   602.3
  5037.3  604.06  5061.5  606.62  5139.6  609.77  5223.1  612.34  5262.1  614.06
#Mann= 3 ,-1 , 0
  4521.2     .05       0  4999.2    .033       0  5005.4     .05       0
Bank Sta=4999.2,5005.4
XS Rating Curve= 0 ,0
Exp/Cntr=0.3,0.1

Type RM Length L Ch R = 1 ,6388    ,554,554,554
BEGIN DESCRIPTION:
Whites Branch Tr 2_1 13.0
END DESCRIPTION:
XS GIS Cut Line= 3
      2370079.84      7073141.21      2369829.84      7072891.21
        2369229.        7072860.
#Sta/Elev= 30
  4646.1  615.66  4682.9   614.4    4690  614.79  4739.5  611.17    4789  609.16
  4873.8  602.82  4880.9  600.69    4888   601.1    4895  599.75  4902.1  600.02
  4923.3  598.25  4958.7  597.95  4965.7  596.56  4972.8  597.47  4979.9   595.7
    4987  596.73    4994  595.62  5002.6  596.25  5017.4  594.63  5018.4  594.13
  5023.6  594.63  5030.5  594.74  5040.5  597.02  5080.6  596.99  5140.7  599.05
  5230.8  599.02    5314  601.74  5431.1  609.17  5451.1  609.54  5601.3  616.71
#Mann= 3 ,-1 , 0
  4646.1     .05       0  5017.4     .04       0  5023.6     .05       0
Bank Sta=5017.4,5023.6
XS Rating Curve= 0 ,0
Exp/Cntr=0.3,0.1

Type RM Length L Ch R = 1 ,5834    ,300,300,300
BEGIN DESCRIPTION:
Mapping XS b4eb4922
END DESCRIPTION:
XS GIS Cut Line= 3
      2370203.03      7072731.74      2369680.47      7072485.22
      2369215.21      7072497.38
#Sta/Elev= 30
  4420.9  610.99  4439.3  610.69  4507.6  607.94  4530.4  606.33  4627.1  602.71
  4689.9  599.38  4718.2  598.91  4723.9  598.07  4809.3  597.86  4860.3  596.97
  4905.9  597.04  4951.4  595.28  4971.1  592.56  4972.1  592.06  4976.3  592.06
  4977.4  592.56  5001.9  592.58  5040.2  596.11  5100.2     596  5110.2  595.82
  5120.2  594.84  5130.2  595.26  5140.2  596.17  5210.2   599.2  5270.2  604.48
  5300.3  605.65  5369.2  610.13  5374.2  609.99  5430.3  613.48  5464.1  614.93
#Mann= 3 ,-1 , 0
  4420.9     .05       0  4971.1     .04       0  4977.4     .05       0
Bank Sta=4971.1,4977.4
XS Rating Curve= 0 ,0
Exp/Cntr=0.3,0.1

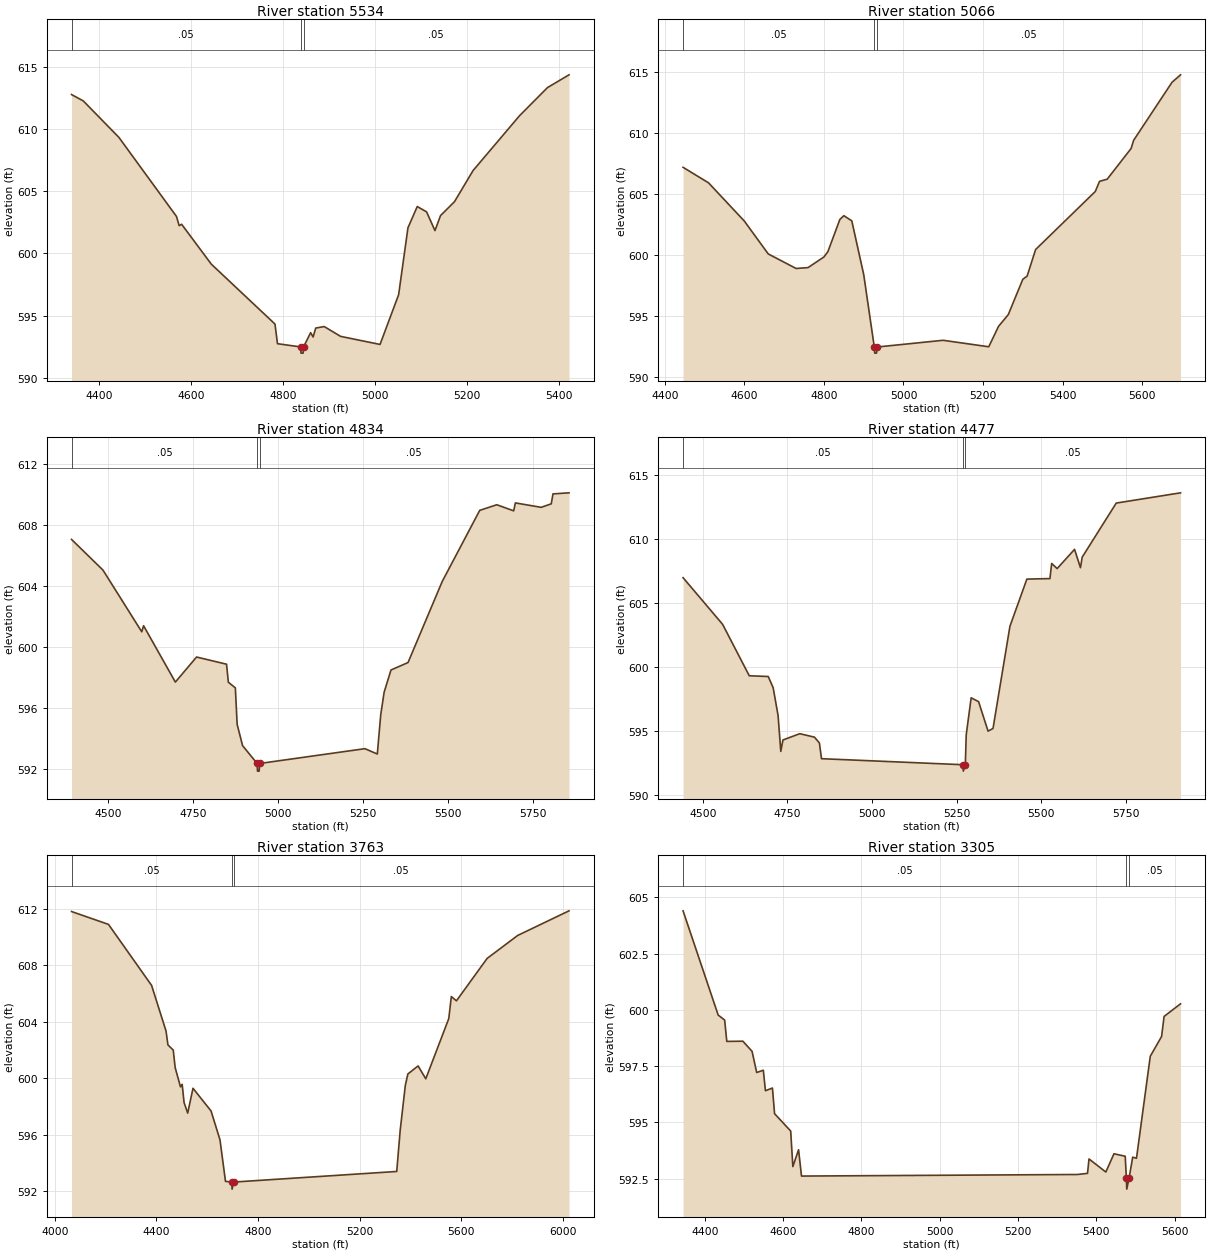
Type RM Length L Ch R = 1 ,5534    ,468,468,468
BEGIN DESCRIPTION:
Whites Branch Tr 2_1 11.0
END DESCRIPTION:
XS GIS Cut Line= 3
      2370339.99      7072473.68      2369729.81      7072223.98
       2369312.7      7072163.99
#Sta/Elev= 30
  4340.7   612.8  4366.2  612.29  4443.6  609.35  4568.7  602.98  4574.5  602.24
  4579.9  602.35  4644.3  599.14  4782.7  594.31  4788.1  592.73  4838.2  592.47
  4839.3  591.97  4843.8  591.97  4844.8  592.47  4860.1  593.62  4865.5  593.27
  4871.2  593.99  4889.6  594.11  4925.2  593.32  5010.9  592.67  5051.3  596.68
  5071.5  602.06  5091.7  603.78    5112  603.35  5130.2  601.84  5142.3  603.05
  5172.6  604.17    5213  606.68    5314   611.1  5374.6  613.36  5421.4  614.39
#Mann= 3 ,-1 , 0
  4340.7     .05       0  4838.2     .04       0  4844.8     .05       0
Bank Sta=4838.2,4844.8
XS Rating Curve= 0 ,0
Exp/Cntr=0.3,0.1

Type RM Length L Ch R = 1 ,5066    ,232,232,232
BEGIN DESCRIPTION:
Whites Branch Tr 2_1 10.0
END DESCRIPTION:
XS GIS Cut Line= 3
      2370433.03      7071802.93        2369879.        7071810.
        2369229.        7072060.
#Sta/Elev= 30
    4446  607.17    4510   605.9    4600  602.77  4660.1  600.08  4730.1  598.89
  4760.1  598.96  4800.1  599.83  4810.1  600.27  4840.1   602.9  4850.1  603.21
  4870.1  602.79  4900.1  598.39  4926.7  592.46  4927.8  591.96  4932.4  591.96
  4933.4  592.46  5099.7  593.01  5214.4  592.48    5239  594.15  5263.6  595.12
  5300.1  598.01  5310.8  598.26  5332.2  600.44  5482.2  605.19  5492.9  606.02
  5512.2   606.2  5572.2  608.71  5578.6  609.38  5675.1  614.13  5696.5  614.74
#Mann= 3 ,-1 , 0
    4446     .05       0  4926.7    .033       0  4933.4     .05       0
Bank Sta=4926.7,4933.4
XS Rating Curve= 0 ,0
Exp/Cntr=0.3,0.1

Type RM Length L Ch R = 1 ,4834    ,357,357,357
BEGIN DESCRIPTION:
Mapping XS 0f135cce
END DESCRIPTION:
XS GIS Cut Line= 3
      2370454.48      7071774.14      2369889.38      7071578.83
      2369027.41       7071500.7
#Sta/Elev= 30
  4391.8  607.03  4484.3  605.02  4598.4  600.98  4603.7  601.38  4697.2  597.69
  4759.6  599.33  4847.8  598.86  4853.1  597.68  4873.7  597.31    4879  594.92
  4894.9  593.53  4937.8  592.36  4938.9  591.86  4943.7  591.86  4944.8  592.36
  5254.9  593.33  5291.3  592.98  5301.4  595.56  5311.4  597.03  5331.5  598.48
  5381.7  598.97  5482.1  604.27  5592.5  608.93  5642.7   609.3  5692.4   608.9
  5697.4  609.42  5773.3  609.13    5803  609.36    5808  610.01  5855.2  610.08
#Mann= 3 ,-1 , 0
  4391.8     .05       0  4937.8    .033       0  4944.8     .05       0
Bank Sta=4937.8,4944.8
XS Rating Curve= 0 ,0
Exp/Cntr=0.3,0.1

Type RM Length L Ch R = 1 ,4477    ,714,714,714
BEGIN DESCRIPTION:
Mapping XS 774f0d6a
END DESCRIPTION:
XS GIS Cut Line= 4
      2370464.89       7071758.5      2370123.76      7071321.02
      2369748.76      7071039.77      2369313.98      7070938.23
#Sta/Elev= 30
    4442  606.98  4558.9  603.34  4637.6  599.33  4693.7  599.27  4708.2   598.4
  4722.7  596.24  4730.8  593.43  4737.1  594.32  4786.9  594.81  4830.3  594.54
  4844.8  594.09  4851.1  592.86  5268.9  592.39  5270.1  591.89    5276  592.39
  5278.7  594.72  5293.3  597.61  5315.2  597.31  5343.3  595.01  5357.9  595.22
  5407.9  603.19  5457.9  606.87  5526.1  606.91  5531.2  608.09  5547.4  607.69
  5598.8  609.19  5616.3  607.76  5621.4  608.58    5722   612.8    5912   613.6
#Mann= 3 ,-1 , 0
    4442     .05       0  5268.9    .033       0    5276     .05       0
Bank Sta=5268.9,5276
XS Rating Curve= 0 ,0
Exp/Cntr=0.3,0.1

Type RM Length L Ch R = 1 ,3763    ,458,458,458
BEGIN DESCRIPTION:
Mapping XS 62b0294e
END DESCRIPTION:
XS GIS Cut Line= 3
      2371382.62      7071511.74       2370721.2      7070918.02
      2369658.65      7070800.83
#Sta/Elev= 30
  4065.7  611.79  4211.1  610.88  4380.8  606.56  4437.6  603.33  4445.1  602.35
    4466  601.98  4473.5  600.75  4494.4  599.38  4501.1  599.56  4508.6  598.27
  4522.8  597.52  4543.7  599.28  4614.8  597.67  4649.9  595.63  4671.6  592.69
  4696.4  592.64  4697.5  592.14  4703.5  592.64  5345.5  593.39  5359.1   596.3
  5379.3  599.48  5389.3  600.29  5429.6  600.86  5459.8  599.95  5550.3  604.21
  5560.4  605.77  5580.5  605.47  5701.2  608.47  5821.9   610.1  6023.5  611.84
#Mann= 3 ,-1 , 0
  4065.7     .05       0  4696.4    .033       0  4703.5     .05       0
Bank Sta=4696.4,4703.5
XS Rating Curve= 0 ,0
Exp/Cntr=0.3,0.1

Type RM Length L Ch R = 1 ,3305    ,36,36,36
BEGIN DESCRIPTION:
Mapping XS b546e4ca
END DESCRIPTION:
XS GIS Cut Line= 6
      2371246.86      7070952.11      2371129.47       7070685.8
      2370787.02      7070563.31       2370477.6      7070515.77
      2370428.51      7070549.08      2370276.66      7070736.45
#Sta/Elev= 30
  4344.6   604.4  4434.3  599.77  4450.8  599.55  4456.3   598.6  4497.4  598.61
  4520.8  598.16  4532.7  597.22  4549.6  597.32    4555  596.41  4572.9  596.53
  4578.3  595.39  4619.5  594.62    4625  593.04  4639.6  593.79  4647.1  592.62
  5352.1  592.69  5377.6  592.74  5381.4  593.38  5424.4   592.8  5445.2  593.61
  5473.9   593.5  5476.8  592.54  5477.9  592.04  5483.9  592.54    5493  593.46
  5502.7  593.41  5537.9  597.94  5566.8  598.82  5573.2  599.71  5615.2  600.27
#Mann= 3 ,-1 , 0
  4344.6     .05       0  5476.8    .033       0  5483.9     .05       0
Bank Sta=5476.8,5483.9
XS Rating Curve= 0 ,0
Exp/Cntr=0.3,0.1