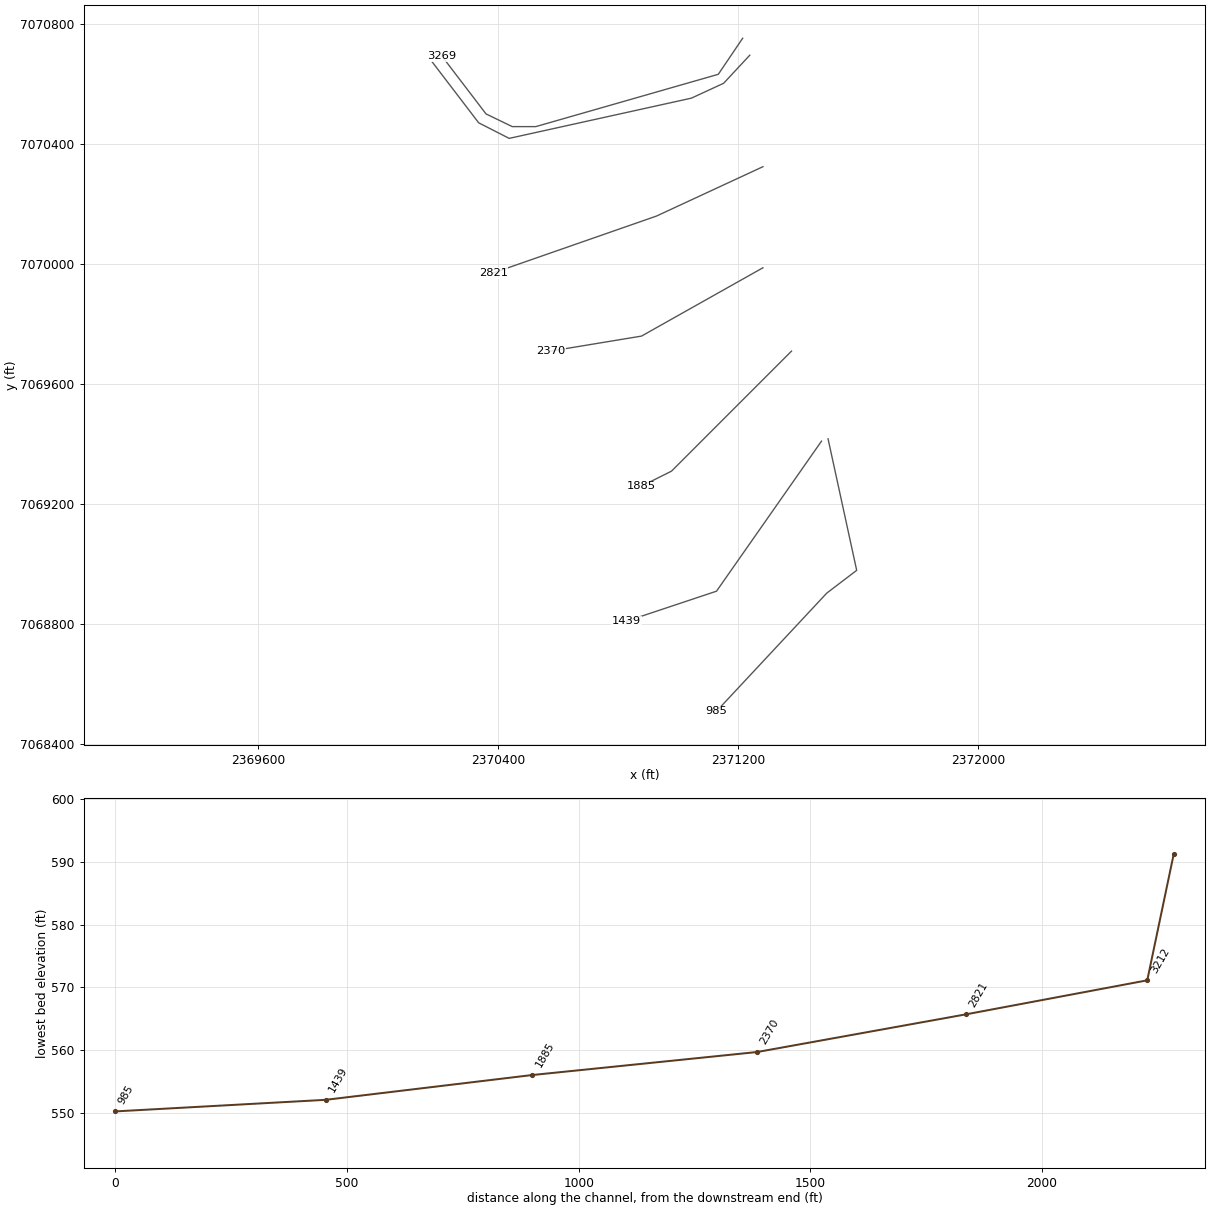
HEC-RAS study Whites Branch Tr 2_1.prj: Whites Branch Tr 2_1 Base Level Engineering

--- Whites Branch Tr 2_1.g01 (geometry) --- (continued)

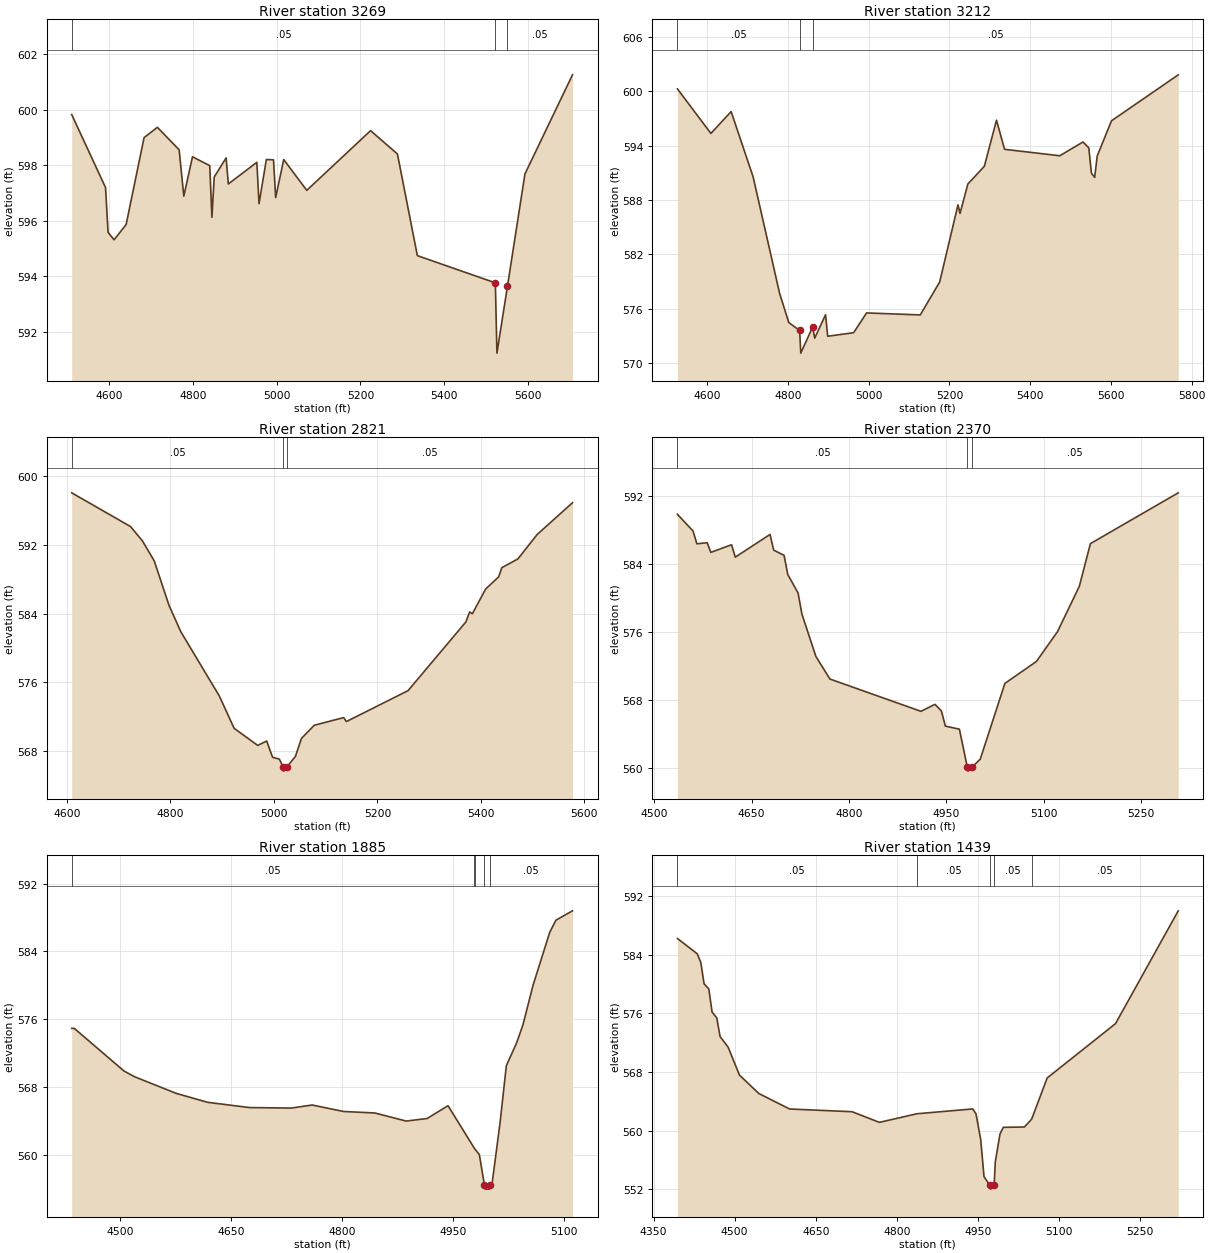
Type RM Length L Ch R = 1 ,3269    ,57,57,57
BEGIN DESCRIPTION:
Mapping XS c5168534
END DESCRIPTION:
XS GIS Cut Line= 6
      2371216.21      7070752.51      2371134.94      7070632.33
       2370526.6      7070458.02      2370448.13      7070458.02
      2370360.63      7070500.38      2370213.37      7070693.28
#Sta/Elev= 30
    4510  599.82  4590.9  597.19  4596.9  595.58  4611.3  595.31  4640.1  595.86
    4683  598.99  4714.8  599.36  4766.8  598.55  4777.9  596.88  4798.7   598.3
  4839.9  597.98  4845.1  596.12  4850.6  597.57  4879.1  598.26  4884.3  597.32
  4952.5   598.1  4957.7  596.61  4975.2   598.2  4992.3  598.19  4997.5  596.83
  5016.7   598.2  5071.8  597.09  5224.3  599.24  5288.5   598.4  5336.1  594.74
  5522.5  593.76  5526.3  591.23  5551.5  593.64  5593.2  597.68  5706.9  601.25
#Mann= 3 ,-1 , 0
    4510     .05       0  5522.5    .033       0  5551.5     .05       0
Bank Sta=5522.5,5551.5
XS Rating Curve= 0 ,0
Exp/Cntr=0.3,0.1

Type RM Length L Ch R = 1 ,3212    ,391,391,391
BEGIN DESCRIPTION:
Whites Branch Tr 2_1 6.0
END DESCRIPTION:
XS GIS Cut Line= 6
      2371239.83      7070695.94      2371152.67      7070602.39
      2371045.47      7070552.91      2370437.83       7070418.8
       2370336.2       7070470.7      2370181.49      7070673.27
#Sta/Elev= 30
  4526.4  600.24  4609.3  595.33  4659.4  597.74  4713.8  590.55  4779.5   577.7
  4802.2  574.49  4829.1  573.62  4831.9  571.12  4861.2  573.99  4866.4  572.77
  4893.3  575.35  4898.6  572.98  4962.8  573.37  4994.9  575.55  5127.9  575.33
  5175.9  578.95  5221.3  587.46  5226.4  586.52  5245.8  589.76  5286.6  591.71
  5316.7  596.79  5336.7  593.58  5473.5  592.87    5531  594.39  5545.4  593.74
  5551.8  590.95  5559.9  590.49  5566.2  592.84  5601.5  596.72  5766.9  601.79
#Mann= 3 ,-1 , 0
  4526.4     .05       0  4829.1    .033       0  4861.2     .05       0
Bank Sta=4829.1,4861.2
XS Rating Curve= 0 ,0
Exp/Cntr=0.3,0.1

Type RM Length L Ch R = 1 ,2821    ,451,451,451
BEGIN DESCRIPTION:
Whites Branch Tr 2_1 5.0
END DESCRIPTION:
XS GIS Cut Line= 3
       2371283.7      7070324.44        2370929.        7070160.
      2370384.37      7069970.26
#Sta/Elev= 30
  4609.3  598.03    4723  594.11  4745.9  592.45  4768.8  590.12  4797.3  584.96
  4820.2  581.88  4894.4  574.44  4923.1  570.67  4968.7  568.68  4986.1  569.19
  4997.5  567.29  5010.5  567.09  5017.7  566.19  5018.8  565.69  5025.2  566.19
  5041.6   567.4  5053.2  569.49    5078  571.02  5134.8  571.91  5140.1  571.45
  5259.2  575.04  5370.9  583.02  5378.2  584.18  5383.5  583.98  5409.3  586.86
  5434.4  588.27  5440.4  589.33  5471.5  590.35  5508.6  593.18    5577  596.88
#Mann= 3 ,-1 , 0
  4609.3     .05       0  5017.7    .033       0  5025.2     .05       0
Bank Sta=5017.7,5025.2
XS Rating Curve= 0 ,0
Exp/Cntr=0.3,0.1

Type RM Length L Ch R = 1 ,2370    ,485,485,485
BEGIN DESCRIPTION:
Whites Branch Tr 2_1 4.0
END DESCRIPTION:
XS GIS Cut Line= 3
      2371283.65      7069987.61        2370879.        7069760.
      2370575.39      7069709.85
#Sta/Elev= 30
  4535.7   589.9  4559.8  587.93  4565.6  586.43  4581.5  586.56  4587.2  585.42
  4619.1  586.32  4624.9  584.86  4678.4  587.53  4684.1  585.68  4700.1  585.07
  4705.8  582.81  4721.7  580.63  4727.5  578.18  4749.1  573.17  4770.8  570.51
  4911.1  566.71  4932.7  567.53  4942.6  566.76  4948.7  564.97  4970.3  564.61
  4982.5  560.17  4983.6  559.67  4990.1  560.17  5002.5  561.08  5040.5     570
  5089.1  572.58  5121.6  576.09  5155.2  581.42  5172.3  586.45  5307.7  592.43
#Mann= 3 ,-1 , 0
  4535.7     .05       0  4982.5    .033       0  4990.1     .05       0
Bank Sta=4982.5,4990.1
XS Rating Curve= 0 ,0
Exp/Cntr=0.3,0.1

Type RM Length L Ch R = 1 ,1885    ,446,446,446
BEGIN DESCRIPTION:
Whites Branch Tr 2_1 3.0
END DESCRIPTION:
XS GIS Cut Line= 3
      2371378.99      7069709.99        2370979.        7069310.
      2370878.98      7069259.99
#Sta/Elev= 30
  4434.3  574.94  4437.8  574.94    4505  569.92  4519.1  569.25  4575.7  567.28
  4618.1  566.23  4674.7  565.61  4731.3  565.55  4759.6  565.91    4802  565.15
  4844.4  564.97  4886.8  564.02  4915.1  564.32  4943.4  565.83  4979.2  560.79
    4980   560.7  4985.8  560.06  4992.6   556.5  4993.8     556  4999.1     556
  5000.2   556.5  5002.8   556.5  5013.9   563.9  5022.3  570.54  5036.3  573.25
  5044.7  575.34  5058.7   580.1    5081  586.26  5089.4  587.69  5111.8  588.79
#Mann= 5 ,-1 , 0
  4434.3     .05       0  4979.2     .12       0    4980     .05       0
  4992.6    .033       0  5000.2     .05       0
Bank Sta=4992.6,5000.2
XS Rating Curve= 0 ,0
Exp/Cntr=0.3,0.1

Type RM Length L Ch R = 1 ,1439    ,454,454,454
BEGIN DESCRIPTION:
Whites Branch Tr 2_1 2.0
END DESCRIPTION:
XS GIS Cut Line= 3
      2371479.02      7069410.02        2371129.        7068910.
      2370828.99        7068810.
#Sta/Elev= 30
  4394.2   586.2  4430.9  584.11  4437.4  582.94  4443.5  580.02  4452.2  579.33
  4458.3  576.18    4467  575.37  4473.1  572.83    4488  571.39  4508.9  567.59
  4544.6  565.08  4601.7  562.96  4717.3  562.59  4767.8  561.14  4837.2  562.31
  4940.5  562.97  4946.6  562.31  4955.3   558.8  4961.4  553.76  4972.4  552.54
  4973.5  552.04  4980.1  552.54  4982.3  555.77    4991  559.55  4997.1  560.46
  5036.2  560.51  5049.6  561.58  5078.3  567.19  5204.8   574.6  5320.8  589.97
#Mann= 5 ,-1 , 0
  4394.2     .05       0  4837.2     .05       0  4972.4    .033       0
  4980.1     .05       0  5049.6     .05       0
Bank Sta=4972.4,4980.1
XS Rating Curve= 0 ,0
Exp/Cntr=0.3,0.1

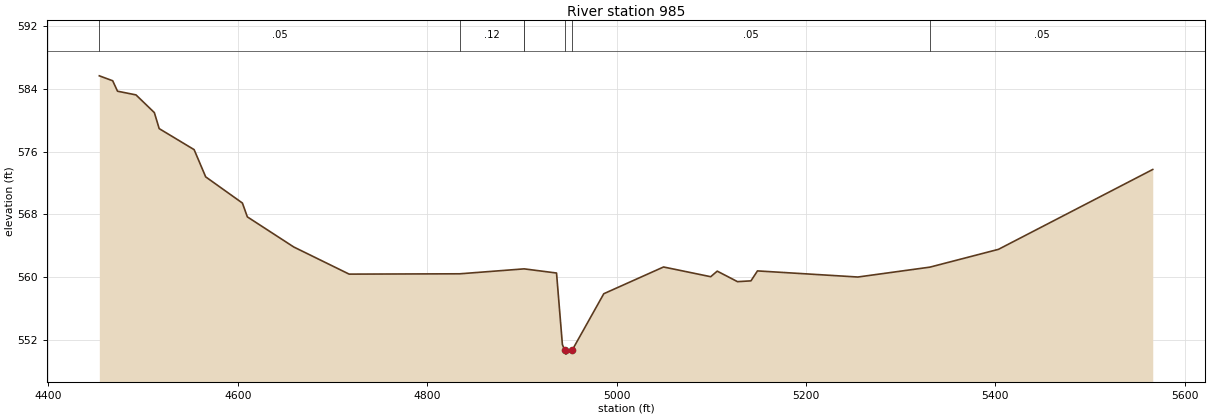
Type RM Length L Ch R = 1 ,985     ,0,0,0
BEGIN DESCRIPTION:
Whites Branch Tr 2_1 1.0
END DESCRIPTION:
XS GIS Cut Line= 4
      2371500.76      7069417.76      2371596.24      7068979.44
      2371496.42      7068903.48        2371129.        7068510.
#Sta/Elev= 30
  4453.8  585.67  4467.9  585.04    4473  583.71  4492.5  583.24  4511.9  580.98
    4517  578.94  4553.9  576.26  4566.1  572.79  4604.9  569.45  4610.1  567.69
  4659.1  563.85  4717.6  560.39  4834.4  560.43  4902.4  561.06  4936.6  560.53
  4942.8   551.4  4945.3  550.69  4946.5  550.19  4953.1  550.69  4986.5  557.89
  5049.6   561.3  5099.4  560.06  5106.3  560.77  5127.7  559.43  5141.9  559.53
  5148.8   560.8  5254.8  560.02  5330.9  561.28  5403.3  563.55  5566.2  573.73
#Mann= 7 ,-1 , 0
  4453.8     .05       0  4834.4     .12       0  4902.4     .05       0
  4902.4     .05       0  4945.3    .033       0  4953.1     .05       0
  5330.9     .05       0
Bank Sta=4945.3,4953.1
XS Rating Curve= 0 ,0
Exp/Cntr=0.3,0.1

Chan Stop Cuts=-1
Use User Specified Reach Order=0
Composite Channel Slope=5