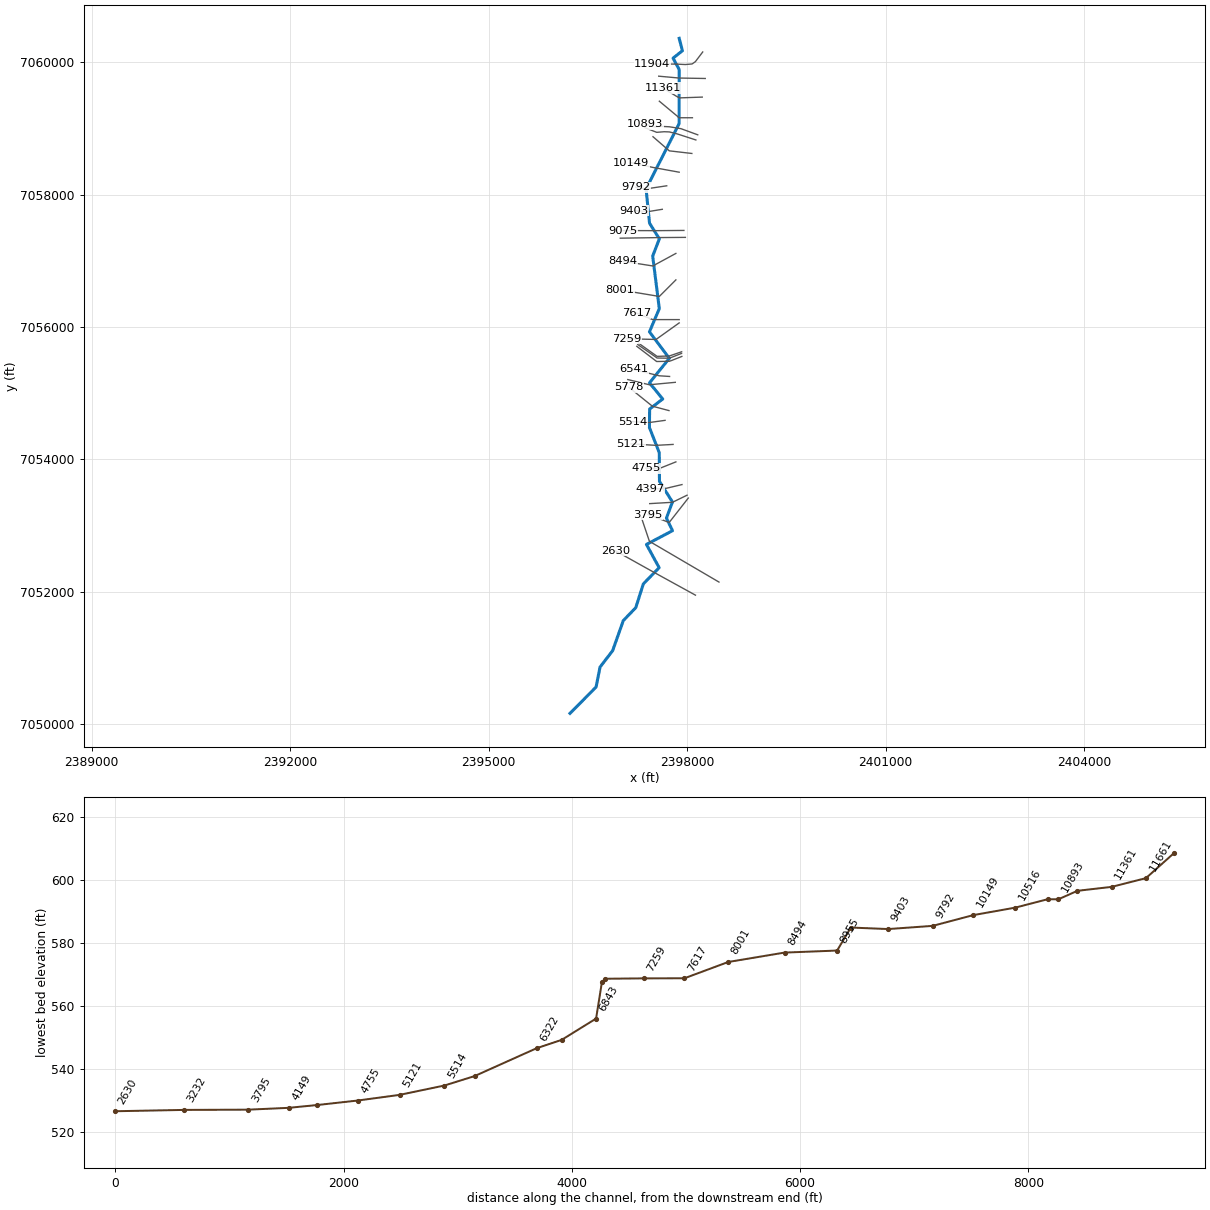
--- Wichita Chase Tr.prj (project) ---

Proj Title=Wichita Chase Tr Base Level Engineering
Current Plan=p01
Default Exp/Contr=0.3,0.1
English Units
Geom File=g01
Flow File=f01
Plan File=p01
Y Axis Title=Elevation
X Axis Title(PF)=Main Channel Distance
X Axis Title(XS)=Station
BEGIN DESCRIPTION:
Wichita Chase Tr
END DESCRIPTION:
DSS Export Rating Curves= 0
DSS Export Rating Curve Sorted= 0
DSS Export Volume Flow Curves= 0
DXF OffsetX= 0
DXF OffsetY= 0
DXF ScaleX= 1
DXF ScaleY= 10

--- Wichita Chase Tr.p01 (plan) ---

Plan Title=Multiple Run
Short Identifier=Multiple
Geom File=g01
Flow File=f01
Subcritical Flow
K Sum by GR= 0
Std Step Tol= 0.01
Critical Tol= 0.01
Num of Std Step Trials= 20
Max Error Tol= 0.3
Flow Tol Ratio= 0.001
Split Flow NTrial= 30
Split Flow Tol= 0.02
Split Flow Ratio= 0.02
Log Output Level= 0
Friction Slope Method= 1
Unsteady Friction Slope Method= 2
Unsteady Bridges Friction Slope Method= 1
Parabolic Critical Depth
Global Vel Dist=  1 , 1 , 1
Global Log Level= 0
CheckData=True
Encroach Param= -1, 0, 0, 0
BEGIN DESCRIPTION:
Multiple Run
END DESCRIPTION:

--- Wichita Chase Tr.f01 (steady flow) ---

Flow Title=Multiple
Number of Profiles=7
Profile Names=10-year,25-year,50-year,1pct_min,100-year,1pct_plu,500-year
River Rch & RM= Wichita Chase Tr,Reach-1,11904
     348     461     551     327     653    1303     920
River Rch & RM= Wichita Chase Tr,Reach-1,10149
     574     784     957     580    1158    2310    1697
River Rch & RM= Wichita Chase Tr,Reach-1,3232
     919    1287    1595     980    1956    3903    2951
Boundary for River Rch & Prof#=Wichita Chase Tr,Reach-1,1
Up Type=0
Dn Type=3
Dn Slope=0.005
Boundary for River Rch & Prof#=Wichita Chase Tr,Reach-1,2
Up Type=0
Dn Type=3
Dn Slope=0.005
Boundary for River Rch & Prof#=Wichita Chase Tr,Reach-1,3
Up Type=0
Dn Type=3
Dn Slope=0.005
Boundary for River Rch & Prof#=Wichita Chase Tr,Reach-1,4
Up Type=0
Dn Type=3
Dn Slope=0.005
Boundary for River Rch & Prof#=Wichita Chase Tr,Reach-1,5
Up Type=0
Dn Type=3
Dn Slope=0.005
Boundary for River Rch & Prof#=Wichita Chase Tr,Reach-1,6
Up Type=0
Dn Type=3
Dn Slope=0.005
Boundary for River Rch & Prof#=Wichita Chase Tr,Reach-1,7
Up Type=0
Dn Type=3
Dn Slope=0.005

--- Wichita Chase Tr.g01 (geometry) ---

Geom Title=Existing Conditions
Program Version=4.10

River Reach=Wichita Chase Tr,Reach-1
Reach XY= 30
        2397879.        7060360.      2397927.83      7060172.01
      2397786.31      7060060.11      2397878.71      7059889.71
       2397877.8       7059070.5      2397378.61        7058085.
      2397431.07      7057565.86       2397579.6      7057330.05
      2397478.54      7057070.19      2397578.49      7056275.21
      2397429.36      7055925.16      2397729.79      7055525.07
      2397430.49      7055154.09      2397629.89      7054909.97
      2397432.44      7054758.78      2397429.07      7054480.03
      2397577.78       7054099.5      2397581.01      7053665.68
      2397776.94      7053354.14      2397686.29      7053110.06
      2397778.17      7052920.43      2397384.29      7052712.67
       2397575.9      7052361.65      2397337.14      7052116.06
      2397223.17       7051757.7      2397034.83       7051562.3
      2396873.46      7051107.58      2396682.55      7050858.53
      2396623.17       7050557.7        2396229.        7050160.

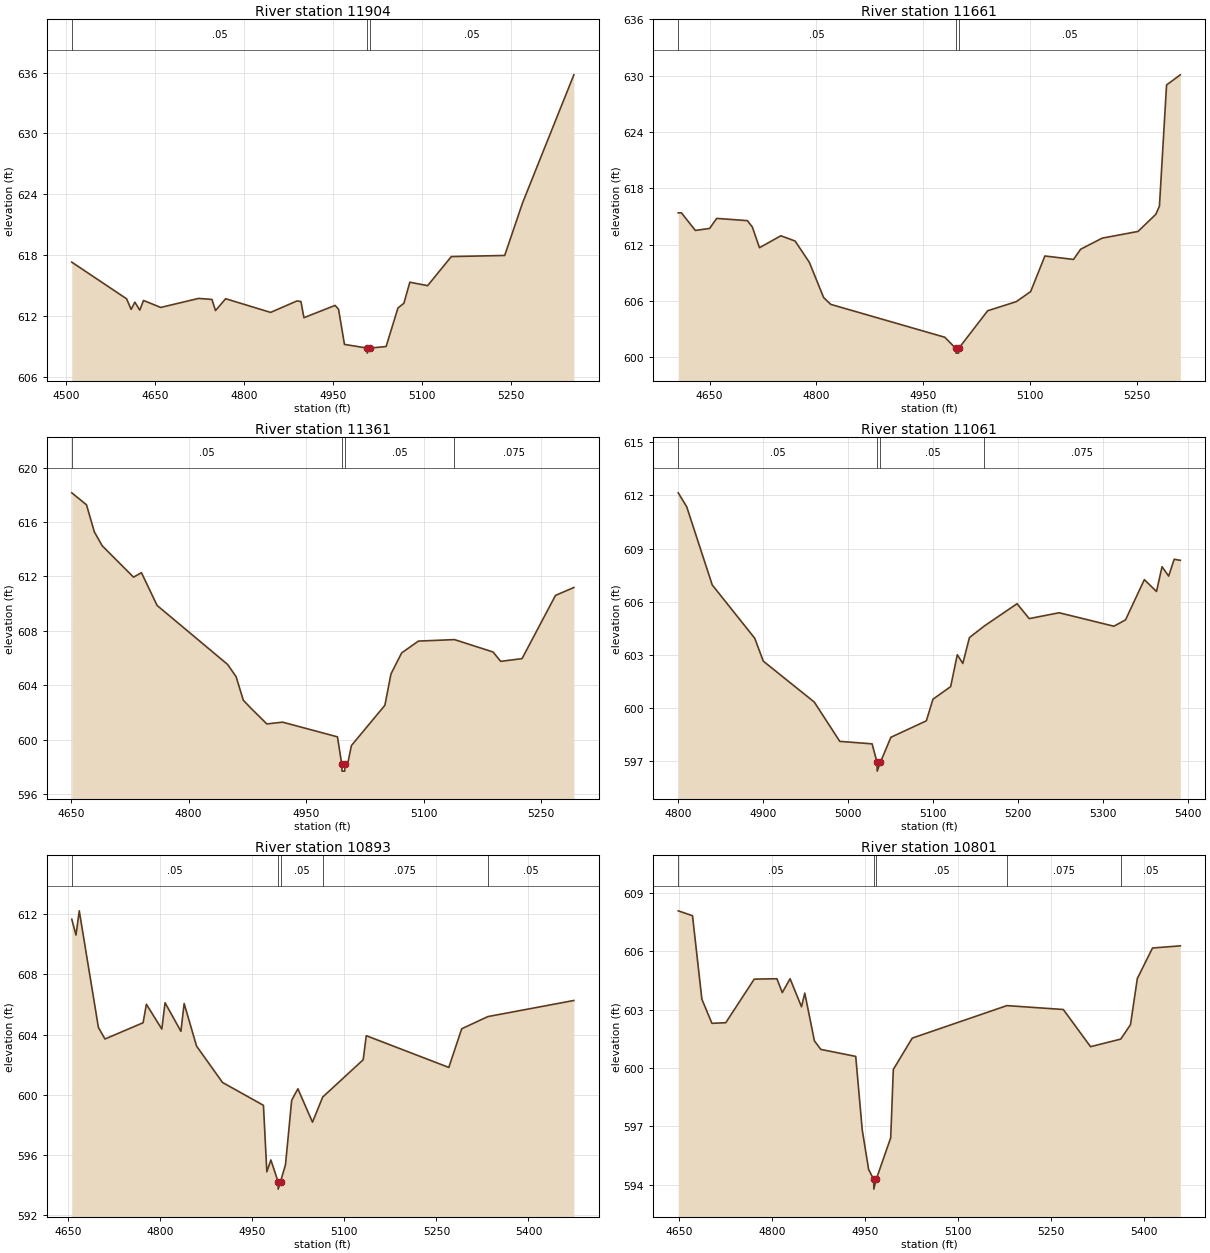
Type RM Length L Ch R = 1 ,11904   ,243,243,243
BEGIN DESCRIPTION:
Wichita Chase Tr 32.0
END DESCRIPTION:
XS GIS Cut Line= 6
      2398234.75       7060154.1      2398123.73      7060007.86
      2398074.25      7059972.96      2397972.69      7059964.11
      2397828.87      7059970.97      2397472.38      7059971.62
#Sta/Elev= 30
  4509.9  617.29  4602.4  613.67    4610  612.63  4616.3  613.34  4624.6  612.56
  4630.9  613.51  4659.9  612.82  4723.8  613.71  4746.3  613.61  4752.3  612.51
  4769.4  613.68  4845.2  612.33  4889.7  613.46  4896.4   613.4  4901.4  611.81
    4954  613.02  4959.8  612.64  4969.8  609.17    5008  608.81  5008.2  608.31
    5012  608.81    5040  608.96    5060  612.77    5070  613.23    5080  615.31
    5110  614.97    5150  617.84    5240  617.95    5270  623.12  5356.6  635.78
#Mann= 3 ,-1 , 0
  4509.9     .05       0    5008     .05       0    5012     .05       0
Bank Sta=5008,5012
XS Rating Curve= 0 ,0
Exp/Cntr=0.3,0.1

Type RM Length L Ch R = 1 ,11661   ,300,300,300
BEGIN DESCRIPTION:
Wichita Chase Tr 31.0
END DESCRIPTION:
XS GIS Cut Line= 3
      2398272.98      7059753.41        2397879.        7059760.
      2397569.82      7059788.13
#Sta/Elev= 30
    4606  615.39  4610.5  615.39    4630  613.52    4650  613.73    4660   614.8
  4703.1  614.56    4710  613.88    4720  611.68    4750  612.95    4770  612.39
    4790  610.12    4810  606.38    4820  605.65    4980  602.15  4995.5  600.96
  4995.8  600.46  4999.3  600.46  4999.5  600.96  5040.2  604.97  5080.4  605.94
  5100.5  607.01  5120.5   610.8  5160.6  610.43  5170.7  611.52  5200.9   612.7
  5251.1  613.41  5276.1  615.23  5281.2   616.1  5291.2     629  5310.5  630.08
#Mann= 3 ,-1 , 0
    4606     .05       0  4995.5    .033       0  4999.5     .05       0
Bank Sta=4995.5,4999.5
XS Rating Curve= 0 ,0
Exp/Cntr=0.3,0.1

Type RM Length L Ch R = 1 ,11361   ,300,300,300
BEGIN DESCRIPTION:
Wichita Chase Tr 30.0
END DESCRIPTION:
XS GIS Cut Line= 3
       2398227.8      7059472.16        2397879.        7059460.
      2397628.96      7059610.02
#Sta/Elev= 30
    4651  618.15  4669.8  617.27  4679.8  615.28  4689.8  614.26  4729.8  611.95
  4739.9  612.28  4759.9  609.87  4849.9  605.53  4860.7  604.63  4869.9   602.9
  4879.9   602.3  4899.9  601.16    4920  601.29    4990  600.21  4995.5  598.19
  4995.8  597.69  4999.3  597.69  4999.5  598.19  5002.9  598.19  5007.8  599.57
  5050.5  602.53  5058.3  604.84  5071.9  606.38  5093.3  607.25  5139.3  607.36
  5188.5  606.45  5198.3  605.76  5225.5  605.96  5268.2  610.61  5291.6  611.19
#Mann= 4 ,-1 , 0
    4651     .05       0  4995.5     .05       0  4999.5     .05       0
  5139.3    .075       0
Bank Sta=4995.5,4999.5
XS Rating Curve= 0 ,0
Exp/Cntr=0.3,0.1

Type RM Length L Ch R = 1 ,11061   ,168,168,168
BEGIN DESCRIPTION:
Wichita Chase Tr 29.0
END DESCRIPTION:
XS GIS Cut Line= 3
      2398078.99        7059160.        2397879.        7059160.
        2397579.        7059410.
#Sta/Elev= 30
  4800.1  612.15  4810.1  611.36  4840.1  606.95  4890.1  603.94  4900.1  602.65
  4960.1  600.34  4990.1  598.12  5028.1  597.98  5033.9  596.94  5034.1  596.44
  5037.9  596.94  5050.2  598.35  5091.9  599.28  5099.7   600.5  5120.5  601.21
  5128.3  603.01  5134.8  602.52  5142.6  603.98  5160.3  604.64  5198.6  605.89
  5212.9  605.05  5248.1  605.38  5312.5  604.62  5326.2  604.98  5348.3  607.25
  5362.6  606.58  5369.1  607.98  5376.9  607.45  5383.4   608.4  5390.6  608.34
#Mann= 4 ,-1 , 0
  4800.1     .05       0  5033.9    .033       0  5037.9     .05       0
  5160.3    .075       0
Bank Sta=5033.9,5037.9
XS Rating Curve= 0 ,0
Exp/Cntr=0.3,0.1

Type RM Length L Ch R = 1 ,10893   ,92,92,92
BEGIN DESCRIPTION:
Mapping XS 63434626
END DESCRIPTION:
XS GIS Cut Line= 6
      2398159.54       7058902.2      2397904.71      7058995.25
      2397730.41      7059023.72      2397612.35      7059029.28
      2397508.88      7059020.94      2397367.24      7059063.99
#Sta/Elev= 30
  4655.9  611.67  4662.8  610.62  4668.1  612.23  4699.3  604.48    4710  603.71
  4772.1  604.79  4777.5  606.02  4802.6  604.37  4807.9  606.12  4833.7  604.22
    4839  606.07  4859.2  603.24  4901.5  600.82  4968.2   599.3  4973.7  594.88
  4980.3  595.67    4992  594.23  4992.2  593.73    4996  594.23  5004.1  595.35
  5014.2  599.64  5024.3   600.4  5048.1  598.18  5064.7  599.85  5130.7  602.33
  5135.7  603.93  5270.2  601.82  5291.2  604.39  5333.9   605.2  5473.9  606.27
#Mann= 5 ,-1 , 0
  4655.9     .05       0    4992     .05       0    4996     .05       0
  5064.7    .075       0  5333.9     .05       0
Bank Sta=4992,4996
XS Rating Curve= 0 ,0
Exp/Cntr=0.3,0.1

Type RM Length L Ch R = 1 ,10801   ,285,285,285
BEGIN DESCRIPTION:
Wichita Chase Tr 28.0
END DESCRIPTION:
XS GIS Cut Line= 6
      2398131.08      7058824.42      2397846.45      7058916.75
      2397729.71      7058945.94      2397651.24      7058948.72
      2397539.43      7058939.69      2397354.24      7059012.08
#Sta/Elev= 30
  4649.1  608.08  4672.1  607.83  4687.2  603.54  4703.4   602.3  4725.7  602.33
  4771.6  604.57  4808.2  604.59  4816.8  603.88  4829.4  604.59  4847.8  603.15
  4853.1  603.85  4868.6   601.4  4878.9  600.96  4935.2   600.6  4945.7  596.82
    4956  594.79  4964.2  594.28  4964.4  593.78  4968.2  594.28  4991.6  596.42
  4995.8  599.93  5026.3  601.54  5178.9  603.21  5269.8  603.01  5313.7   601.1
  5362.4  601.49  5378.1  602.23  5389.1   604.6  5413.6  606.17  5458.4  606.28
#Mann= 5 ,-1 , 0
  4649.1     .05       0  4964.2     .05       0  4968.2     .05       0
  5178.9    .075       0  5362.4     .05       0
Bank Sta=4964.2,4968.2
XS Rating Curve= 0 ,0
Exp/Cntr=0.3,0.1

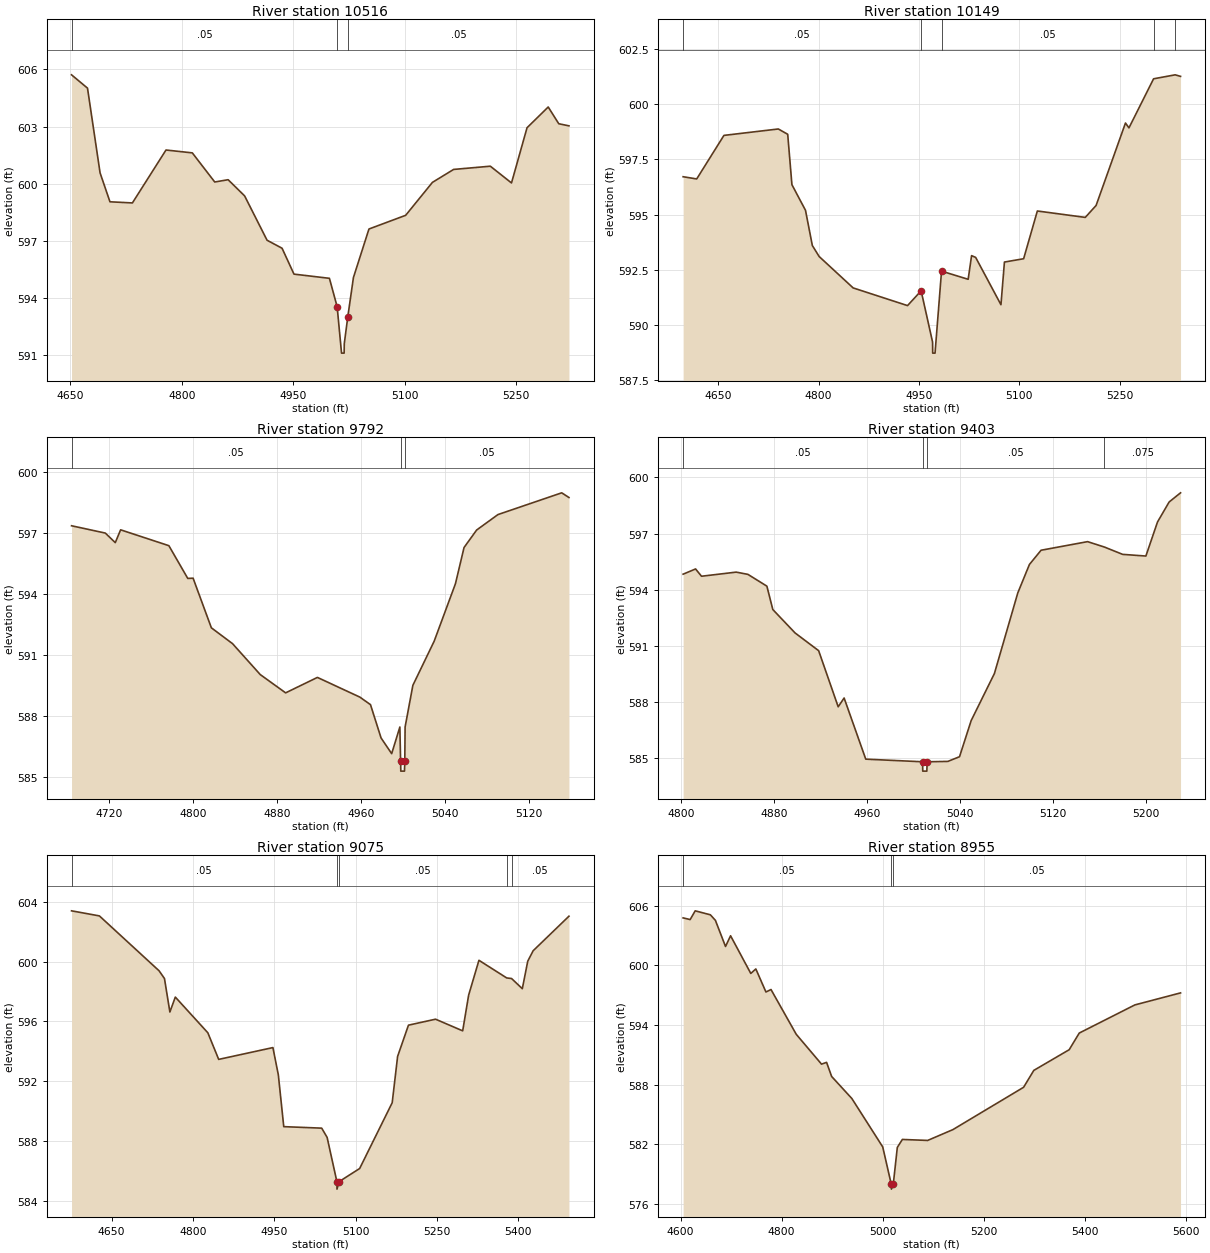
Type RM Length L Ch R = 1 ,10516   ,367,367,367
BEGIN DESCRIPTION:
Wichita Chase Tr 27.0
END DESCRIPTION:
XS GIS Cut Line= 3
      2398070.38      7058620.36        2397729.        7058660.
      2397483.15      7058873.52
#Sta/Elev= 30
  4651.7  605.72  4673.2  605.02  4690.1  600.57  4703.4  599.05  4733.6  598.99
  4778.8  601.77  4814.2  601.62  4844.4  600.09  4862.4  600.21  4884.6  599.36
  4914.8  597.03    4935  596.61    4951  595.25  4998.7  595.03  5009.1  593.54
    5015   591.1  5018.5   591.1  5018.7   591.6  5023.4     593    5031  595.07
  5051.9  597.62  5101.3  598.34  5137.3  600.07  5165.8  600.75  5215.2  600.92
  5243.7  600.04  5264.6  602.94  5293.1  604.03  5307.3  603.15    5321  603.04
#Mann= 3 ,-1 , 0
  4651.7     .05       0  5009.1    .033       0  5023.4     .05       0
Bank Sta=5009.1,5023.4
XS Rating Curve= 0 ,0
Exp/Cntr=0.3,0.1

Type RM Length L Ch R = 1 ,10149   ,357,357,357
BEGIN DESCRIPTION:
Wichita Chase Tr 26.0
END DESCRIPTION:
XS GIS Cut Line= 3
      2397878.99      7058337.28        2397479.        7058410.
      2397149.86      7058481.68
#Sta/Elev= 30
  4597.5  596.71  4617.8  596.61  4658.5  598.58  4739.8  598.87  4753.8  598.63
  4760.1  596.35  4780.4  595.19  4790.6   593.6  4800.8   593.1  4851.6  591.68
  4932.9  590.88  4953.2  591.55  4970.3  589.23  4970.5  588.73    4974  588.73
  4983.7  592.44  5023.5  592.07  5028.6  593.14  5034.7  593.06  5072.5  590.92
  5077.7  592.85  5106.4     593  5126.9  595.16  5198.5  594.87  5214.7  595.41
  5258.6  599.14  5263.8  598.92  5300.6  601.14  5332.9  601.32  5340.9  601.25
#Mann= 5 ,-1 , 0
  4597.5     .05       0  4953.2    .033       0  4983.7     .05       0
  5300.6    .075       0  5332.9     .05       0
Bank Sta=4953.2,4983.7
XS Rating Curve= 0 ,0
Exp/Cntr=0.3,0.1

Type RM Length L Ch R = 1 ,9792    ,389,389,389
BEGIN DESCRIPTION:
Wichita Chase Tr 25.0
END DESCRIPTION:
XS GIS Cut Line= 3
      2397690.81      7058131.86      2397378.61        7058085.
      2397222.21      7058110.72
#Sta/Elev= 30
  4684.3  597.38  4716.5  597.02    4726  596.55  4731.1  597.18  4777.1   596.4
  4795.1  594.79  4800.2   594.8  4817.6  592.36  4837.8  591.58  4864.2  590.06
  4888.4  589.16  4918.7  589.92  4959.2  588.95  4969.3  588.58  4979.4  586.94
  4989.5  586.17  4997.3  587.48    4998  585.81  4998.2  585.31  5001.7  585.31
    5002  585.81  5002.3  587.48  5009.7  589.53    5030   591.7  5050.3  594.53
  5058.5  596.31  5070.5  597.17  5090.8  597.93  5151.6     599  5158.5  598.77
#Mann= 3 ,-1 , 0
  4684.3     .05       0    4998     .05       0    5002     .05       0
Bank Sta=4998,5002
XS Rating Curve= 0 ,0
Exp/Cntr=0.3,0.1

Type RM Length L Ch R = 1 ,9403    ,328,328,328
BEGIN DESCRIPTION:
Wichita Chase Tr 24.0
END DESCRIPTION:
XS GIS Cut Line= 3
      2397623.97      7057776.83      2397428.48      7057744.78
      2397199.21      7057755.06
#Sta/Elev= 30
  4801.9  594.83  4812.6  595.11  4817.7  594.72  4847.5  594.94  4857.6  594.82
  4873.9  594.19    4879  592.94  4898.1  591.69  4918.4  590.74  4935.2  587.74
  4940.3  588.21  4958.9  584.94  5007.7   584.8  5007.9   584.3  5011.4   584.3
  5011.7   584.8  5029.5  584.82  5039.5  585.07  5049.5     587  5069.5  589.52
  5089.6  593.83  5099.6  595.35  5109.6  596.11  5149.6  596.57  5164.1  596.28
  5179.7  595.89  5199.7   595.8  5209.7  597.62  5219.7  598.69  5229.5  599.18
#Mann= 4 ,-1 , 0
  4801.9     .05       0  5007.7     .05       0  5011.7     .05       0
  5164.1    .075       0
Bank Sta=5007.7,5011.7
XS Rating Curve= 0 ,0
Exp/Cntr=0.3,0.1

Type RM Length L Ch R = 1 ,9075    ,120,120,120
BEGIN DESCRIPTION:
Wichita Chase Tr 23.0
END DESCRIPTION:
XS GIS Cut Line= 3
      2397950.38      7057457.38       2397526.5      7057453.96
        2397033.      7057455.64
#Sta/Elev= 30
  4576.1   603.4  4627.5  603.06  4737.5  599.39  4747.5  598.87  4757.5  596.63
  4767.5  597.63  4827.5  595.24  4847.5  593.46  4947.5  594.25  4957.5  592.43
  4967.5  588.96  5037.5  588.86  5047.5  588.24  5065.5  585.28  5065.7  584.78
  5069.5  585.28  5107.5  586.16  5167.5  590.56  5177.5  593.66  5197.5  595.75
  5247.5  596.15  5297.5  595.37  5308.5  597.76  5327.5  600.09  5378.7  598.91
  5387.7  598.87  5407.5  598.19  5417.5  600.03  5427.5  600.73  5493.5  603.04
#Mann= 5 ,-1 , 0
  4576.1     .05       0  5065.5     .05       0  5069.5     .05       0
  5378.7    .075       0  5387.7     .05       0
Bank Sta=5065.5,5069.5
XS Rating Curve= 0 ,0
Exp/Cntr=0.3,0.1

Type RM Length L Ch R = 1 ,8955    ,461,461,461
BEGIN DESCRIPTION:
Wichita Chase Tr 22.0
END DESCRIPTION:
XS GIS Cut Line= 3
      2397972.91      7057352.35      2397577.92      7057349.46
      2396988.59       7057340.2
#Sta/Elev= 30
    4605  604.78  4618.9  604.61  4628.9  605.49  4658.9  605.09  4668.9  604.53
  4688.9   601.9  4698.9  602.98  4738.9  599.19  4748.9  599.64  4768.9  597.32
  4778.9  597.57  4828.9  593.06  4878.9  590.06  4888.9  590.24  4898.9  588.82
  4938.9   586.6    5000  581.73  5016.9  577.98  5017.2  577.48  5020.9  577.98
  5028.9  581.68  5038.9  582.48  5088.9  582.38  5138.9  583.47  5278.8  587.73
    5299  589.43    5369  591.51    5389  593.19    5499  596.02  5589.4  597.23
#Mann= 3 ,-1 , 0
    4605     .05       0  5016.9    .033       0  5020.9     .05       0
Bank Sta=5016.9,5020.9
XS Rating Curve= 0 ,0
Exp/Cntr=0.3,0.1

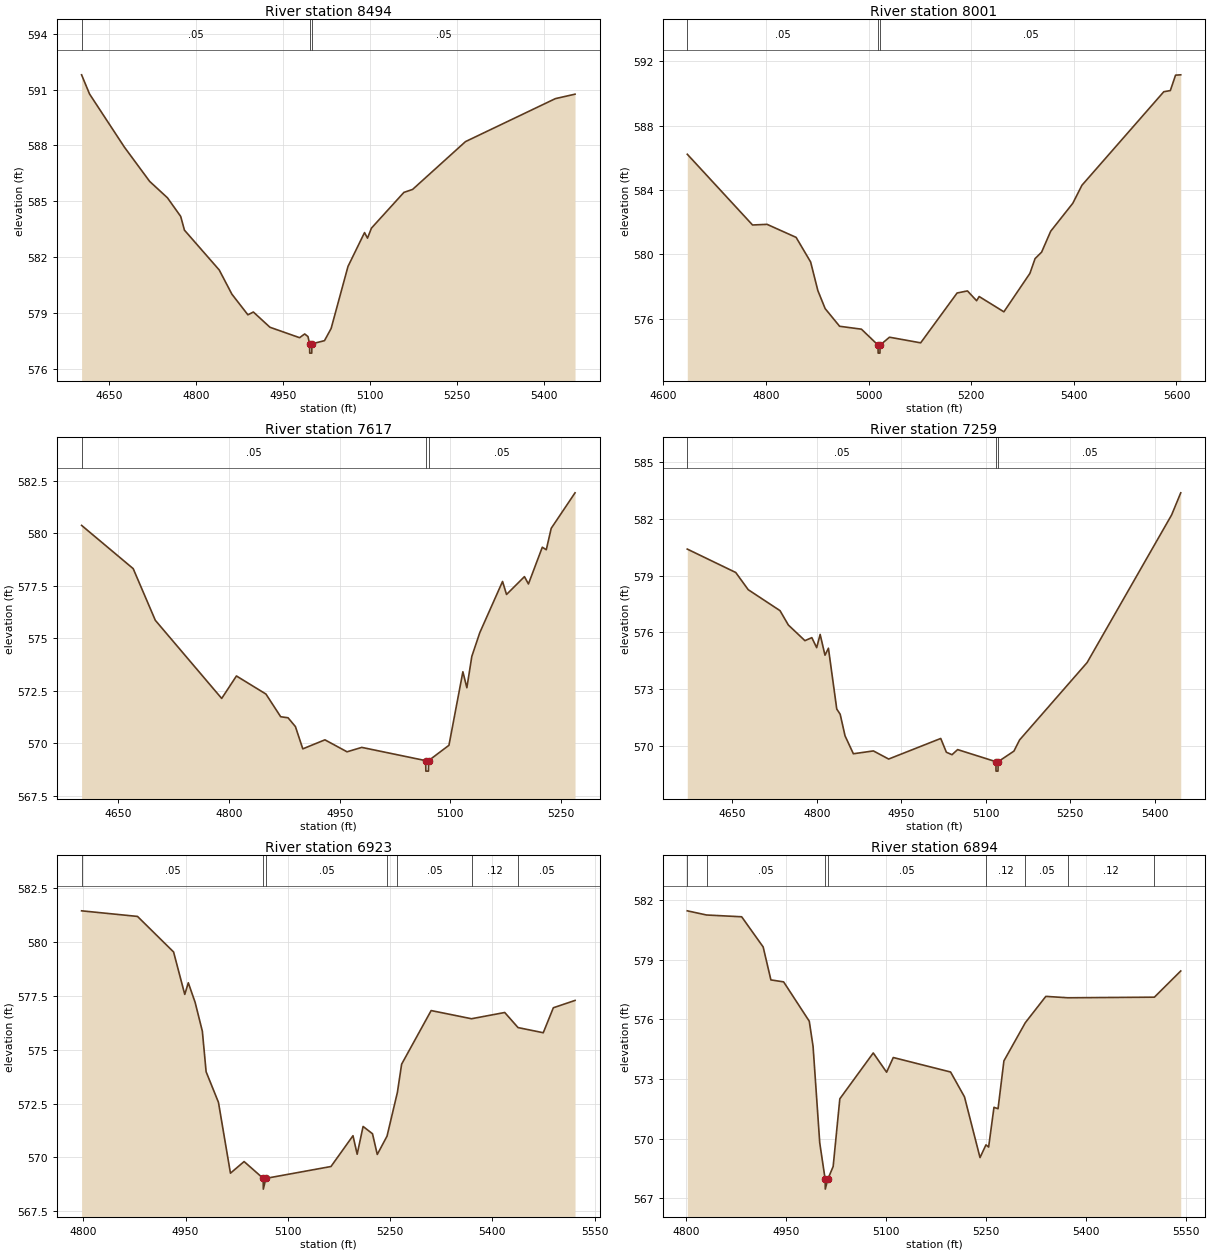
Type RM Length L Ch R = 1 ,8494    ,493,493,493
BEGIN DESCRIPTION:
Wichita Chase Tr 21.0
END DESCRIPTION:
XS GIS Cut Line= 3
      2397828.97      7057109.98      2397480.22       7056920.5
      2397032.56      7056990.56
#Sta/Elev= 30
  4603.1  591.79  4616.8  590.76  4676.7  587.91  4720.4  586.06    4751  585.18
  4773.8  584.18  4780.3  583.44  4840.2   581.3    4862     580  4889.6  578.89
    4899  579.04  4927.6  578.22  4978.6  577.66  4987.4  577.86  4993.1  577.72
  4995.8  577.33  4996.1  576.83  4999.6  576.83  4999.8  577.33  5021.5   577.5
  5032.9  578.15    5062  581.49  5090.5  583.31  5095.6  583.01  5102.4  583.55
  5158.3  585.47  5173.3  585.63  5264.4   588.2  5419.2  590.51  5453.1  590.75
#Mann= 3 ,-1 , 0
  4603.1     .05       0  4995.8    .033       0  4999.8     .05       0
Bank Sta=4995.8,4999.8
XS Rating Curve= 0 ,0
Exp/Cntr=0.3,0.1

Type RM Length L Ch R = 1 ,8001    ,384,384,384
BEGIN DESCRIPTION:
Wichita Chase Tr 20.0
END DESCRIPTION:
XS GIS Cut Line= 3
      2397828.97      7056709.97        2397579.        7056460.
      2396978.99        7056560.
#Sta/Elev= 30
  4646.5  586.22  4773.7  581.82    4802  581.86  4858.6  581.05  4886.9  579.52
    4901  577.74  4915.2  576.62  4943.4  575.52  4985.9  575.34  5018.3  574.35
  5018.5  573.85    5022  573.85  5022.3  574.35  5040.6  574.84  5101.4  574.49
  5172.4  577.59  5192.6  577.72  5210.4  577.11  5215.4  577.37  5263.6  576.42
  5314.3  578.81  5324.4  579.73  5337.1  580.13  5354.8  581.43  5397.9  583.17
  5415.7  584.29  5575.3  590.11    5588  590.18  5598.2  591.14  5608.3  591.16
#Mann= 3 ,-1 , 0
  4646.5     .05       0  5018.3    .033       0  5022.3     .05       0
Bank Sta=5018.3,5022.3
XS Rating Curve= 0 ,0
Exp/Cntr=0.3,0.1

Type RM Length L Ch R = 1 ,7617    ,358,358,358
BEGIN DESCRIPTION:
Wichita Chase Tr 19.0
END DESCRIPTION:
XS GIS Cut Line= 3
      2397878.97        7056110.        2397479.        7056110.
      2397229.03      7056209.99
#Sta/Elev= 30
    4600  580.38    4670  578.32    4700  575.86    4790  572.14    4810  573.21
    4850  572.35    4870  571.27    4880  571.22    4890   570.8    4900  569.74
    4930  570.17    4960   569.6    4980  569.81  5066.6  569.18  5066.9  568.68
  5070.4  568.68  5070.6  569.18  5098.2  569.91  5117.1  573.41  5122.5  572.65
  5129.2  574.14    5140  575.27  5170.9  577.71  5176.3  577.09  5200.6  577.94
    5206  577.59  5224.8  579.34  5230.2  579.22  5236.9  580.24  5269.2  581.93
#Mann= 3 ,-1 , 0
    4600     .05       0  5066.6    .033       0  5070.6     .05       0
Bank Sta=5066.6,5070.6
XS Rating Curve= 0 ,0
Exp/Cntr=0.3,0.1

Type RM Length L Ch R = 1 ,7259    ,336,336,336
BEGIN DESCRIPTION:
Wichita Chase Tr 18.0
END DESCRIPTION:
XS GIS Cut Line= 3
      2397879.03      7056060.02        2397529.        7055810.
      2397082.77      7055820.17
#Sta/Elev= 30
    4570  580.41  4656.1  579.17  4678.2  578.26  4734.7  577.15  4749.5  576.39
    4779  575.56  4791.2  575.72  4799.8  575.19    4806  575.89  4814.6  574.79
  4820.7  575.16  4835.5  571.94  4841.6  571.66  4850.2  570.52    4865  569.57
  4900.6  569.72  4927.7  569.29  5020.2  570.38  5030.2  569.65  5040.2  569.52
  5050.2  569.79  5118.2  569.15  5118.4  568.65  5121.9  568.65  5122.2  569.15
  5150.2  569.71  5160.2   570.3  5280.2   574.4  5430.3  582.22  5446.5  583.39
#Mann= 3 ,-1 , 0
    4570     .05       0  5118.2    .033       0  5122.2     .05       0
Bank Sta=5118.2,5122.2
XS Rating Curve= 0 ,0
Exp/Cntr=0.3,0.1

Type RM Length L Ch R = 1 ,6923    ,29,29,29
BEGIN DESCRIPTION:
Wichita Chase Tr 17.0
END DESCRIPTION:
XS GIS Cut Line= 4
      2397916.62      7055624.03        2397729.        7055560.
      2397545.12      7055554.58      2397267.22      7055752.88
#Sta/Elev= 30
  4797.6  581.45  4879.6  581.19  4932.5  579.54  4948.9  577.57  4954.1  578.11
  4964.1   577.2  4974.7  575.86  4980.2  573.98  4998.3  572.56  5015.9  569.27
  5035.9  569.81  5063.9  569.03  5064.1  568.53  5067.9  569.03  5163.3  569.58
  5195.6  571.01  5201.7  570.15  5210.4  571.44  5224.2   571.1  5231.2  570.14
  5245.5  570.99  5260.7  573.02  5266.9  574.33  5310.2  576.82  5369.4  576.44
  5418.1  576.73  5437.6  576.03  5474.6  575.79  5489.4  576.95  5521.2  577.29
#Mann= 7 ,-1 , 0
  4797.6     .05       0  5063.9    .033       0  5067.9     .05       0
  5245.5     .12       0  5260.7     .05       0  5369.4     .12       0
  5437.6     .05       0
Bank Sta=5063.9,5067.9
XS Rating Curve= 0 ,0
Exp/Cntr=0.3,0.1

Type RM Length L Ch R = 1 ,6894    ,51,51,51
BEGIN DESCRIPTION:
Mapping XS 6c6792e6
END DESCRIPTION:
XS GIS Cut Line= 6
      2397914.81      7055599.17      2397744.71      7055532.35
      2397683.08      7055527.14      2397543.32      7055529.75
      2397523.36      7055545.37      2397252.45      7055733.39
#Sta/Elev= 30
  4802.1  581.47  4830.9  581.26  4883.6  581.17  4915.8  579.65  4927.4  577.99
  4946.5  577.89  4984.9  575.91  4990.6  574.64  5000.6  569.78  5008.7  567.95
  5008.9  567.45  5012.7  567.95  5020.7  568.59  5030.7     572  5080.8  574.31
  5100.8  573.34  5110.8  574.08  5196.7  573.35  5217.5   572.1  5240.8  569.04
  5249.7  569.68  5253.7  569.57  5261.7  571.57  5267.8   571.5  5276.6  573.91
  5308.6  575.83  5339.4  577.16  5372.5  577.09  5502.1  577.12  5541.6  578.44
#Mann= 8 ,-1 , 0
  4802.1     .12       0  4830.9     .05       0  5008.7    .033       0
  5012.7     .05       0  5249.7     .12       0  5308.6     .05       0
  5372.5     .12       0  5502.1     .05       0
Bank Sta=5008.7,5012.7
XS Rating Curve= 0 ,0
Exp/Cntr=0.3,0.1

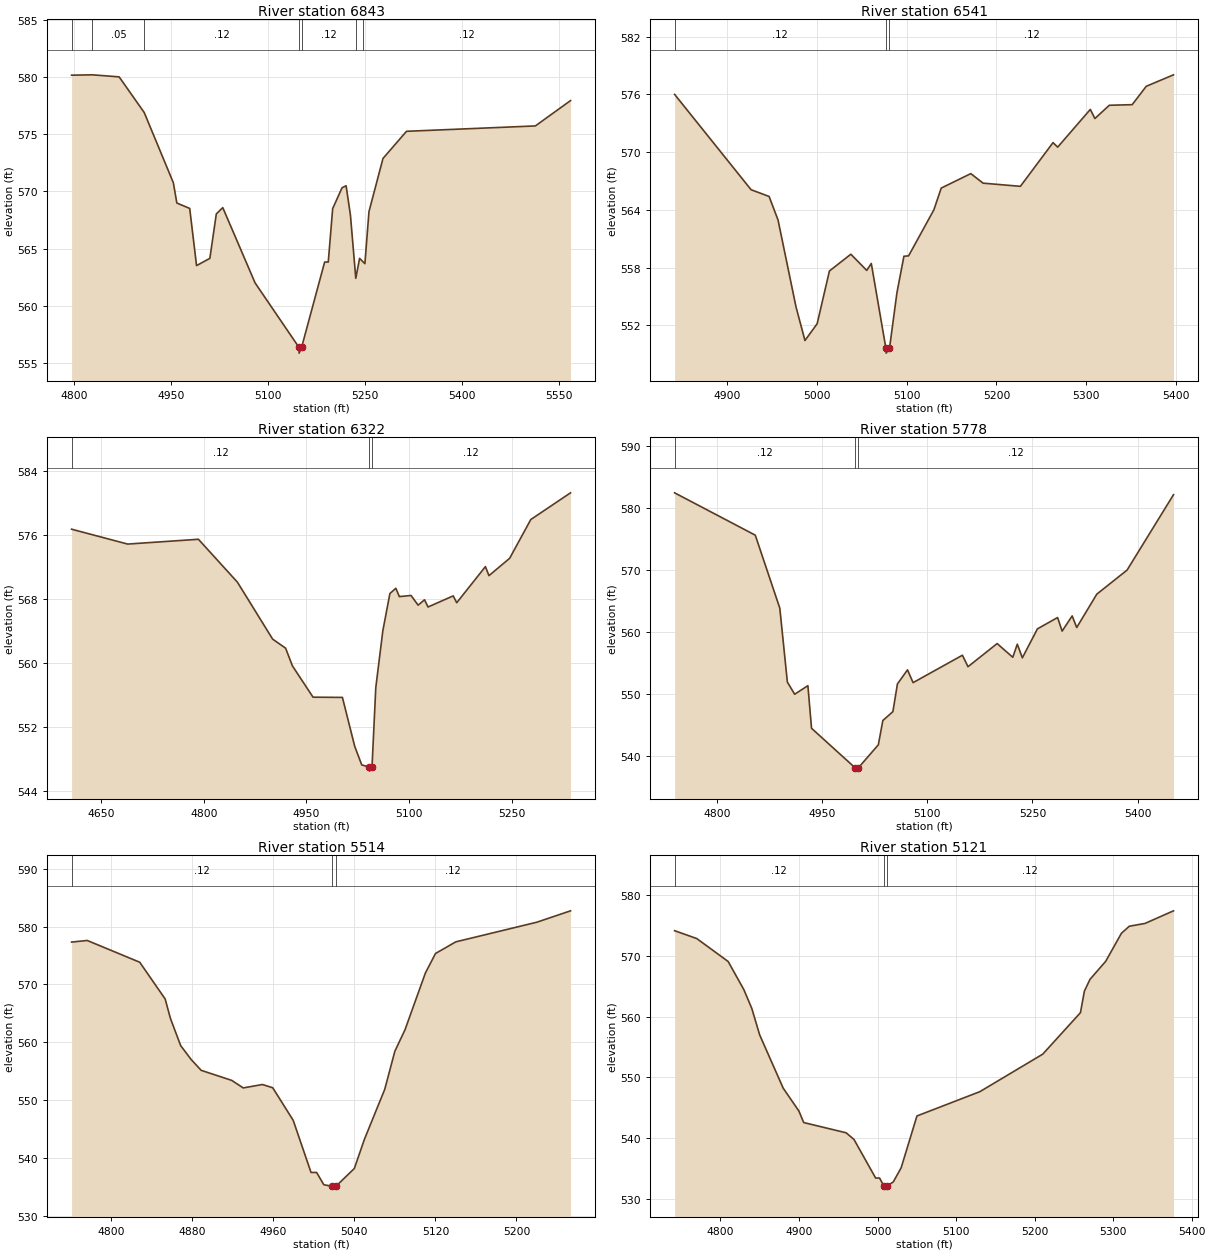
Type RM Length L Ch R = 1 ,6843    ,302,302,302
BEGIN DESCRIPTION:
Mapping XS 35b20bcc
END DESCRIPTION:
XS GIS Cut Line= 5
      2397919.26      7055553.32      2397759.43      7055490.25
      2397729.26      7055479.95       2397538.6      7055476.71
      2397238.33      7055706.17
#Sta/Elev= 30
  4796.3  580.15  4828.6  580.18  4869.9     580  4908.7  576.89  4953.8  570.76
  4959.2  568.99  4979.1  568.52  4989.7  563.53  5010.3  564.16  5020.3  568.04
  5030.3  568.59  5080.3  562.02  5148.3  556.39  5148.5  555.89  5152.3  556.39
    5188  563.84  5193.6  563.84  5200.4   568.5  5214.9  570.32  5221.2   570.5
  5227.9  567.94  5236.2  562.42  5242.1  564.16  5247.2  563.87  5250.3   563.7
  5256.6  568.24  5278.3  572.88  5314.7  575.25  5514.2  575.72  5568.6  577.93
#Mann= 7 ,-1 , 0
  4796.3     .12       0  4828.6     .05       0  4908.7     .12       0
  5148.3     .07       0  5152.3     .12       0  5236.2     .05       0
  5247.2     .12       0
Bank Sta=5148.3,5152.3
XS Rating Curve= 0 ,0
Exp/Cntr=0.3,0.1

Type RM Length L Ch R = 1 ,6541    ,219,219,219
BEGIN DESCRIPTION:
Wichita Chase Tr 16.0
END DESCRIPTION:
XS GIS Cut Line= 3
      2397734.13       7055250.8      2397575.47      7055261.29
      2397189.43      7055356.04
#Sta/Elev= 30
    4841  575.99  4926.3  566.09  4946.4  565.39  4956.4  562.94  4976.4  553.93
  4986.4  550.43    5000  552.17  5013.7  557.65  5037.6  559.39  5055.3  557.71
  5060.4  558.43  5076.7  549.62    5077  549.12  5080.7  549.62    5089  555.39
  5096.8  559.18    5102  559.22  5130.2     564  5138.4  566.26  5171.4  567.76
  5185.1  566.77  5226.7  566.44  5263.1  570.98  5268.3  570.51  5304.7  574.43
  5309.8  573.48  5325.9  574.86  5351.4  574.92  5367.1  576.83  5397.5  578.02
#Mann= 3 ,-1 , 0
    4841     .12       0  5076.7     .07       0  5080.7     .12       0
Bank Sta=5076.7,5080.7
XS Rating Curve= 0 ,0
Exp/Cntr=0.3,0.1

Type RM Length L Ch R = 1 ,6322    ,544,544,544
BEGIN DESCRIPTION:
Wichita Chase Tr 15.0
END DESCRIPTION:
XS GIS Cut Line= 3
      2397820.07      7055162.26      2397428.81      7055125.29
      2397102.57      7055203.99
#Sta/Elev= 30
    4607  576.74  4688.8  574.88  4792.2  575.48  4849.1  570.12  4900.6  562.99
  4919.5  561.86  4929.5  559.64  4959.6  555.73  5002.5   555.7  5020.4  549.59
  5030.7  547.26  5041.7  546.98    5042  546.48  5045.7  546.98  5051.2  556.91
  5061.5  564.03  5071.8  568.69  5080.5  569.35  5085.6  568.31  5102.7  568.45
    5113  567.24  5122.4  567.91  5127.5  567.01  5164.3   568.4  5169.4  567.54
  5211.3  572.06  5216.5  570.93  5246.7   573.1  5277.6  577.95  5335.6  581.29
#Mann= 3 ,-1 , 0
    4607     .12       0  5041.7     .07       0  5045.7     .12       0
Bank Sta=5041.7,5045.7
XS Rating Curve= 0 ,0
Exp/Cntr=0.3,0.1

Type RM Length L Ch R = 1 ,5778    ,264,264,264
BEGIN DESCRIPTION:
Wichita Chase Tr 14.0
END DESCRIPTION:
XS GIS Cut Line= 3
      2397724.62      7054735.16       2397472.5      7054802.27
      2397120.95      7055085.43
#Sta/Elev= 30
  4739.1  582.51  4854.3  575.68  4889.3  563.91  4900.1  551.99  4910.5  550.03
  4929.4  551.41  4934.6  544.54  4997.2  538.13  4997.5  537.63  5001.2  538.13
    5030  541.88  5036.4  545.79  5050.8  547.23  5057.2  551.68  5071.6  553.96
  5079.6   551.9    5150  556.32    5158  554.47  5199.6   558.2  5221.9  555.99
  5228.4   558.1  5235.6   555.9  5257.1  560.57  5285.9   562.4  5292.4  560.21
  5306.7  562.66  5313.2  560.79  5341.9  566.17  5385.1  570.05  5451.4  582.21
#Mann= 3 ,-1 , 0
  4739.1     .12       0  4997.2     .07       0  5001.2     .12       0
Bank Sta=4997.2,5001.2
XS Rating Curve= 0 ,0
Exp/Cntr=0.3,0.1

Type RM Length L Ch R = 1 ,5514    ,393,393,393
BEGIN DESCRIPTION:
Wichita Chase Tr 13.0
END DESCRIPTION:
XS GIS Cut Line= 3
      2397665.57       7054587.6      2397428.91      7054554.96
      2397175.97       7054568.5
#Sta/Elev= 30
  4761.1  577.31  4776.5  577.59  4828.3  573.83  4853.4  567.48  4858.6  564.12
  4868.7  559.43  4878.8  557.08  4888.9  555.16  4919.1  553.42  4930.4  552.12
  4949.4  552.71  4959.5  552.15  4979.7  546.53  4997.3  537.52  5002.8  537.52
  5009.9   535.4  5017.9  535.14  5018.2  534.64  5021.7  534.64  5021.9  535.14
    5040   538.2    5050  543.26    5070  551.87    5080  558.46    5090  562.16
  5110.1  571.96  5120.1  575.34  5140.1  577.35  5220.2  580.75  5253.3  582.71
#Mann= 3 ,-1 , 0
  4761.1     .12       0  5017.9     .07       0  5021.9     .12       0
Bank Sta=5017.9,5021.9
XS Rating Curve= 0 ,0
Exp/Cntr=0.3,0.1

Type RM Length L Ch R = 1 ,5121    ,366,366,366
BEGIN DESCRIPTION:
Wichita Chase Tr 12.0
END DESCRIPTION:
XS GIS Cut Line= 3
      2397787.11      7054223.89        2397529.        7054210.
      2397152.81      7054231.63
#Sta/Elev= 30
  4741.6   574.1  4769.8  572.81  4809.8  569.04  4829.8  564.42  4839.9  561.34
  4849.9     557  4879.9  548.24  4899.9  544.49    4906   542.6    4960  540.92
    4970  539.83  4997.6  533.49  5002.6  533.49  5008.1  532.17  5008.4  531.67
  5011.9  531.67  5012.1  532.17  5020.1  532.86  5030.1  535.18  5050.2  543.68
  5130.3  547.67  5210.4  553.83  5258.4  560.64  5263.4  564.17  5270.5   566.1
  5290.6  569.08  5310.6  573.68  5320.6  574.83  5340.6  575.29  5376.9  577.36
#Mann= 3 ,-1 , 0
  4741.6     .12       0  5008.1     .07       0  5012.1     .12       0
Bank Sta=5008.1,5012.1
XS Rating Curve= 0 ,0
Exp/Cntr=0.3,0.1

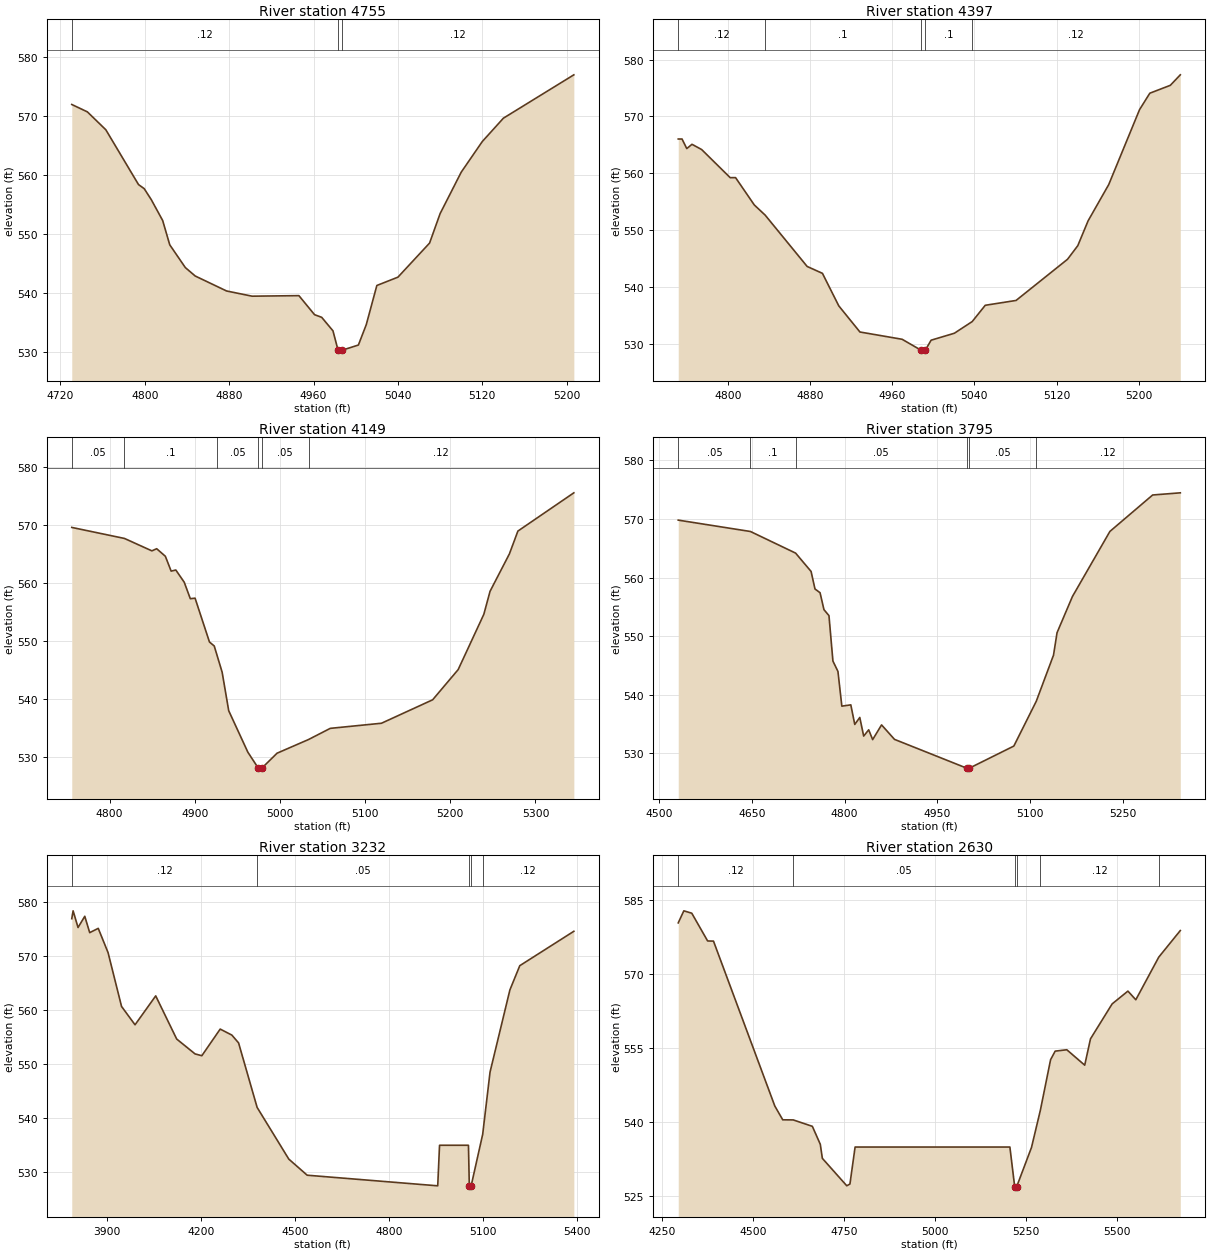
Type RM Length L Ch R = 1 ,4755    ,358,358,358
BEGIN DESCRIPTION:
Wichita Chase Tr 11.0
END DESCRIPTION:
XS GIS Cut Line= 3
      2397829.02      7053960.01        2397579.        7053860.
      2397372.23      7053864.47
#Sta/Elev= 30
  4730.7  571.97  4745.5  570.72    4763  567.69    4794  558.41  4799.4  557.72
  4806.1  555.86  4816.9  552.33  4823.6  548.22  4838.4  544.36  4847.8  542.93
  4877.5   540.4  4901.7  539.52  4946.1  539.61  4960.9  536.39  4967.7  535.94
  4978.4  533.65  4983.2  530.38  4983.4  529.88  4986.9  529.88  4987.2  530.38
  5002.5  531.25    5010  534.72    5020  541.33    5040  542.74    5070  548.51
    5080   553.5    5100  560.51    5120   565.7    5140  569.65  5206.8  576.99
#Mann= 3 ,-1 , 0
  4730.7     .12       0  4983.2     .07       0  4987.2     .12       0
Bank Sta=4983.2,4987.2
XS Rating Curve= 0 ,0
Exp/Cntr=0.3,0.1

Type RM Length L Ch R = 1 ,4397    ,248,248,248
BEGIN DESCRIPTION:
Wichita Chase Tr 10.0
END DESCRIPTION:
XS GIS Cut Line= 3
      2397921.15      7053617.12        2397679.        7053560.
      2397439.36       7053546.8
#Sta/Elev= 30
  4751.7  566.04  4755.4  566.04    4760  564.36  4765.1  565.11  4774.5  564.19
  4802.3  559.25  4807.5  559.26  4825.8  554.45  4836.3  552.68  4877.2  543.66
  4892.1  542.45    4908  536.74  4928.6  532.15  4969.7  530.87  4988.2  528.94
  4988.5  528.44  4992.2  528.94  4997.9  530.71  5020.5  531.93  5037.9  533.98
  5050.6  536.84  5080.6  537.69  5130.7  544.92  5140.7  547.31  5150.7  551.66
  5170.8  558.03  5200.8  571.19  5210.8  574.08  5230.8  575.47  5240.5  577.31
#Mann= 5 ,-1 , 0
  4751.7     .12       0  4836.3      .1       0  4988.2     .07       0
  4992.2      .1       0  5037.9     .12       0
Bank Sta=4988.2,4992.2
XS Rating Curve= 0 ,0
Exp/Cntr=0.3,0.1

Type RM Length L Ch R = 1 ,4149    ,354,354,354
BEGIN DESCRIPTION:
Wichita Chase Tr 9.0
END DESCRIPTION:
XS GIS Cut Line= 3
      2397997.76      7053456.64      2397777.96      7053349.56
      2397433.45      7053329.39
#Sta/Elev= 30
  4755.5  569.55  4817.4  567.65  4849.6  565.51  4855.2  565.88  4865.4  564.58
  4872.2  562.02  4877.7  562.21  4887.6   560.1  4894.7  557.27  4900.3  557.36
  4917.2  549.81  4922.8  549.12  4926.3  547.42  4932.1   544.6  4939.8  537.97
  4962.3  530.82  4974.6  528.06  4974.8  527.56  4978.6  528.06  4996.6  530.65
  5033.6  533.01  5059.1  534.93  5119.2  535.81  5179.3  539.85  5209.3  545.06
  5239.4  554.58  5246.7  558.54  5269.4  564.98  5279.4  568.92  5345.1  575.51
#Mann= 6 ,-1 , 0
  4755.5     .05       0  4817.4      .1       0  4926.3     .05       0
  4974.6    .033       0  4978.6     .05       0  5033.6     .12       0
Bank Sta=4974.6,4978.6
XS Rating Curve= 0 ,0
Exp/Cntr=0.3,0.1

Type RM Length L Ch R = 1 ,3795    ,563,563,563
BEGIN DESCRIPTION:
Wichita Chase Tr 8.0
END DESCRIPTION:
XS GIS Cut Line= 3
      2398016.65      7053413.63      2397727.85      7053044.35
      2397407.18      7053164.96
#Sta/Elev= 30
  4531.2  569.82  4647.9  567.88  4720.9  564.19  4745.9  561.06  4752.2  558.07
  4760.4  557.43  4766.7  554.54  4774.8  553.52  4781.2  545.76  4789.3     544
  4795.6  538.07  4810.1  538.29  4816.5  534.95  4824.6  536.14  4830.9  532.96
    4839  534.03  4845.4  532.36  4859.8  534.87  4880.7   532.4  4997.6  527.48
  4997.8  526.98  5001.6  527.48  5073.6  531.26  5109.8   538.9  5137.7  546.78
  5143.4  550.61  5168.3  556.79  5228.8  567.89  5297.9  574.11  5342.6  574.48
#Mann= 6 ,-1 , 0
  4531.2     .05       0  4647.9      .1       0  4720.9     .05       0
  4997.6    .033       0  5001.6     .05       0  5109.8     .12       0
Bank Sta=4997.6,5001.6
XS Rating Curve= 0 ,0
Exp/Cntr=0.3,0.1

Type RM Length L Ch R = 1 ,3232    ,602,602,602
BEGIN DESCRIPTION:
Wichita Chase Tr 7.0
END DESCRIPTION:
XS GIS Cut Line= 3
      2398480.03      7052144.16        2397429.        7052760.
      2397306.45      7053123.32
#Sta/Elev= 30
  3787.3  576.85  3791.6   578.3  3807.3  575.22  3828.8  577.29  3844.5  574.27
  3871.8  575.06  3903.1  570.58  3946.1  560.64  3989.1  557.25  4055.1  562.59
    4122  554.62  4180.7  551.87  4202.2  551.54  4260.8  556.46    4298  555.35
  4319.4  553.91  4378.6  541.99  4479.7  532.44  4538.3  529.47  4954.7  527.51
  4960.5     535  5052.7     535  5055.5   527.4  5056.3   526.9  5060.9   527.4
  5098.1  537.02  5121.6  548.52  5184.9  563.69  5216.5  568.17  5388.9  574.52
#Mann= 5 ,-1 , 0
  3787.3     .12       0  4378.6     .05       0  5055.5    .033       0
  5060.9     .05       0  5098.1     .12       0
Bank Sta=5055.5,5060.9
XS Rating Curve= 0 ,0
Exp/Cntr=0.3,0.1

Type RM Length L Ch R = 1 ,2630    ,580,580,580
BEGIN DESCRIPTION:
Wichita Chase Tr 6.0
END DESCRIPTION:
XS GIS Cut Line= 3
      2398125.04      7051946.21      2397505.74      7052286.64
      2396917.61      7052614.83
#Sta/Elev= 30
  4293.3  580.37  4308.7  582.81  4330.5  582.33  4374.1  576.71  4390.2  576.68
  4558.8   543.3  4580.6  540.51  4609.4  540.49    4662  539.19  4683.8  535.56
  4689.5  532.71  4756.6  527.16  4765.3  527.51  4779.5     535    5205     535
  5218.2  526.98    5219  526.48  5223.7  526.98  5264.4  534.91  5288.7  542.41
  5316.9  552.68  5329.5  554.41  5361.5  554.69  5410.7  551.57  5426.6   556.9
  5486.1  563.97  5529.5  566.56  5551.2  564.81  5614.3  573.44  5673.5  578.82
#Mann= 6 ,-1 , 0
  4293.3     .12       0  4609.4     .05       0  5218.2    .033       0
  5223.7     .05       0  5288.7     .12       0  5614.3     .05       0
Bank Sta=5218.2,5223.7
XS Rating Curve= 0 ,0
Exp/Cntr=0.3,0.1