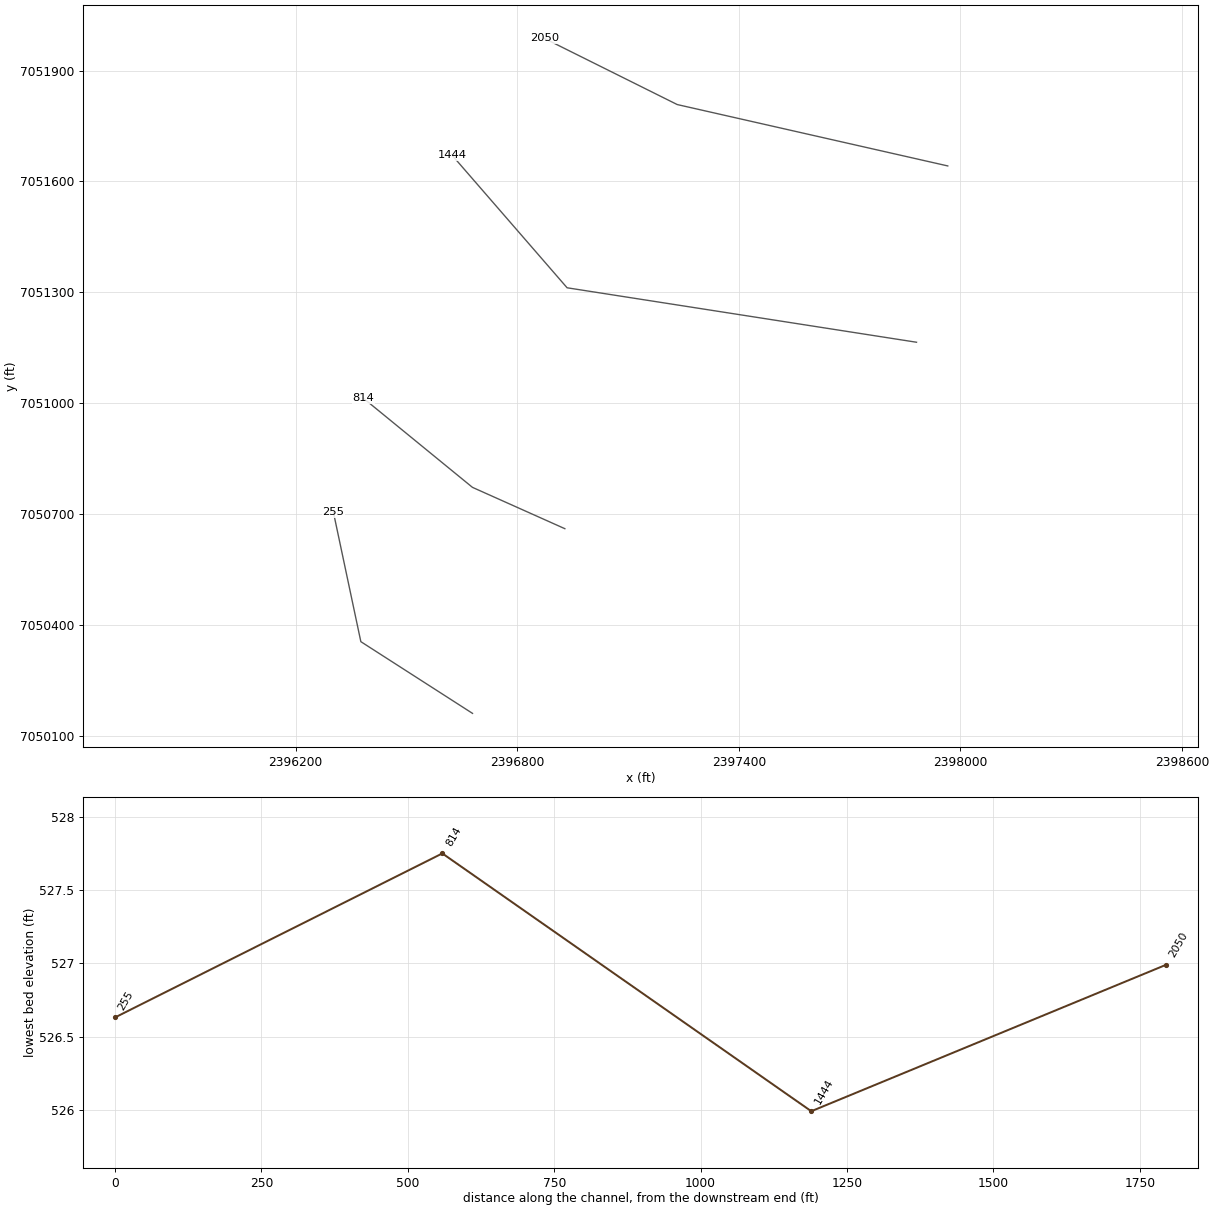
HEC-RAS study Wichita Chase Tr.prj: Wichita Chase Tr Base Level Engineering

--- Wichita Chase Tr.g01 (geometry) --- (continued)

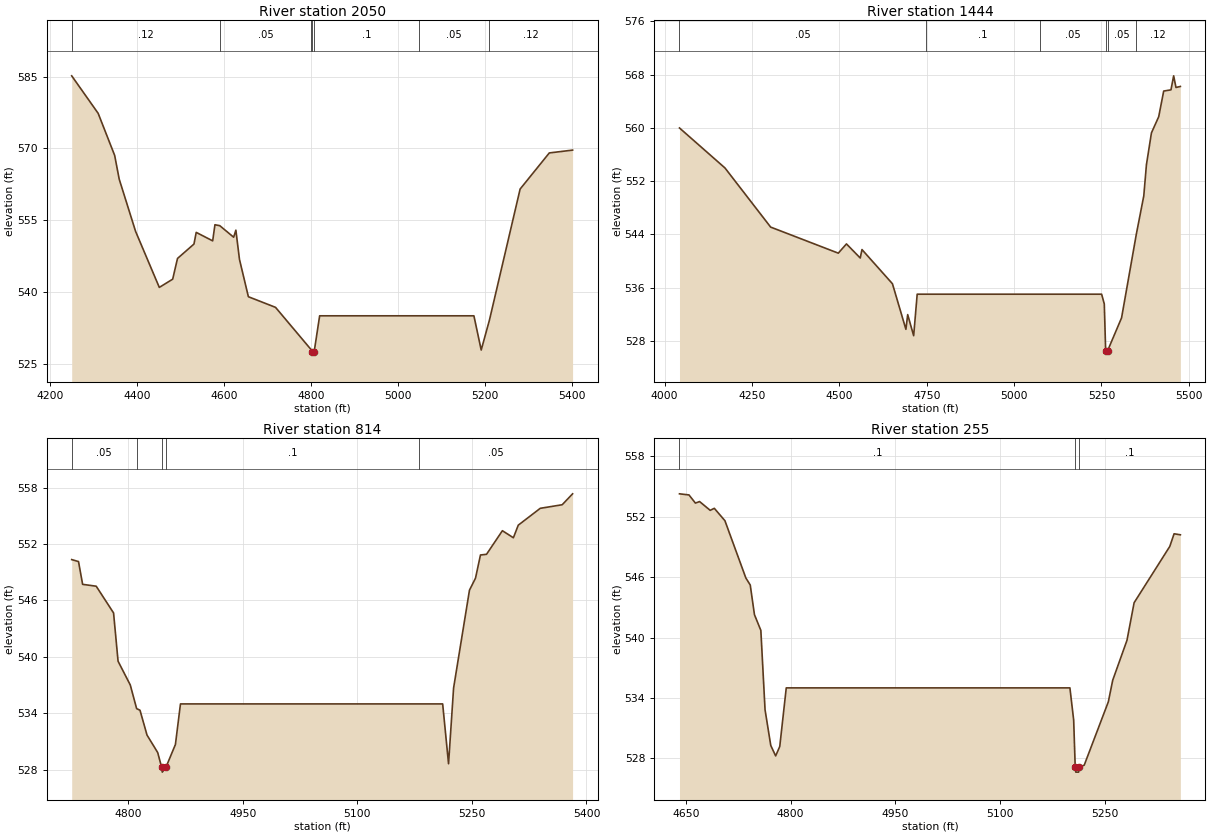
Type RM Length L Ch R = 1 ,2050    ,606,606,606
BEGIN DESCRIPTION:
Wichita Chase Tr 5.0
END DESCRIPTION:
XS GIS Cut Line= 3
       2397965.7      7051642.06      2397233.22      7051808.25
      2396873.18      7051987.51
#Sta/Elev= 30
  4248.9  585.17  4309.8  577.33  4347.8  568.54  4358.3  563.56    4396  552.65
  4450.6  540.94  4481.4  542.66  4492.5  546.99  4530.4     550  4535.6  552.44
  4573.5  550.67  4578.7  554.04  4589.9  553.84  4621.8  551.43  4626.9  552.91
  4635.2  546.79  4655.7  538.99  4718.2  536.77  4800.3  527.91  4801.7  527.49
  4802.5  526.99  4807.2  527.49  4819.8     535  5048.2     535    5175     535
  5191.8  527.85  5210.7  534.08  5281.4   561.5  5348.6  569.05  5402.2  569.64
#Mann= 7 ,-1 , 0
  4248.9     .12       0  4589.9     .05       0  4800.3      .1       0
  4801.7     .07       0  4807.2      .1       0  5048.2     .05       0
  5210.7     .12       0
Bank Sta=4801.7,4807.2
XS Rating Curve= 0 ,0
Exp/Cntr=0.3,0.1

Type RM Length L Ch R = 1 ,1444    ,630,630,630
BEGIN DESCRIPTION:
Wichita Chase Tr 3.0
END DESCRIPTION:
XS GIS Cut Line= 3
      2397881.09      7051164.74      2396935.11      7051312.18
      2396623.22      7051671.63
#Sta/Elev= 30
  4042.6  559.99  4172.7  553.98  4303.4  545.09    4497  541.17  4520.4  542.56
  4559.8  540.44  4564.8  541.71    4652  536.57  4690.5  529.72  4695.6  531.93
  4712.7  528.76  4722.8     535  4747.3     535  5074.6     535  5250.6     535
  5258.2  533.53  5262.1  526.49  5262.9  525.99  5267.6  526.49  5307.6  531.44
  5349.7  543.97  5371.2  549.78  5378.8  554.47  5393.1  559.25  5413.9  561.68
  5428.2  565.54    5449  565.72  5456.7  567.83  5463.3  566.08  5475.9  566.23
#Mann= 6 ,-1 , 0
  4042.6     .05       0  4747.3      .1       0  5074.6     .05       0
  5262.1     .07       0  5267.6     .05       0  5349.7     .12       0
Bank Sta=5262.1,5267.6
XS Rating Curve= 0 ,0
Exp/Cntr=0.3,0.1

Type RM Length L Ch R = 1 ,814     ,559,559,559
BEGIN DESCRIPTION:
Wichita Chase Tr 2.0
END DESCRIPTION:
XS GIS Cut Line= 3
      2396929.01        7050660.      2396678.89      7050771.87
      2396383.24      7051013.45
#Sta/Elev= 30
    4726  550.34  4734.9  550.13  4740.3  547.71  4758.1  547.51  4780.8  544.67
  4786.7  539.54  4802.7  537.01    4811   534.5  4815.4  534.33  4824.6  531.69
  4838.6  529.83  4843.8  528.25  4844.6  527.75  4849.3  528.25  4861.8  530.69
  4868.4     535    5181     535  5211.7     535  5219.4  528.64    5226  536.69
  5246.8  547.09  5254.7  548.37  5261.2  550.83  5269.1   550.9  5289.9  553.41
  5304.3  552.66  5310.7     554  5339.5  555.79  5368.2  556.17  5381.8  557.33
#Mann= 5 ,-1 , 0
    4726     .05       0    4811      .1       0  4843.8     .07       0
  4849.3      .1       0    5181     .05       0
Bank Sta=4843.8,4849.3
XS Rating Curve= 0 ,0
Exp/Cntr=0.3,0.1

Type RM Length L Ch R = 1 ,255     ,0,0,0
BEGIN DESCRIPTION:
Wichita Chase Tr 1.0
END DESCRIPTION:
XS GIS Cut Line= 3
      2396679.03      7050159.98      2396376.71      7050354.14
      2396302.35      7050704.85
#Sta/Elev= 30
  4640.7  554.28  4654.3  554.17  4663.5  553.36  4669.5  553.51  4684.7  552.64
  4690.6  552.84  4705.8  551.61  4735.8  545.92  4742.1  545.22  4748.1  542.28
  4757.3  540.71  4763.3  532.83  4771.5  529.28  4778.5  528.24  4784.4  529.18
  4793.7     535  5200.2     535  5205.6   531.8  5207.8  527.13  5208.7  526.63
  5212.7  526.63  5213.6  527.13  5220.7  527.32  5255.3  533.62  5261.5  535.75
    5282  539.73  5292.2  543.46  5343.3  549.05  5349.5  550.31  5358.5  550.21
#Mann= 3 ,-1 , 0
  4640.7      .1       0  5207.8     .07       0  5213.6      .1       0
Bank Sta=5207.8,5213.6
XS Rating Curve= 0 ,0
Exp/Cntr=0.3,0.1

Chan Stop Cuts=-1
Use User Specified Reach Order=0
Composite Channel Slope=5