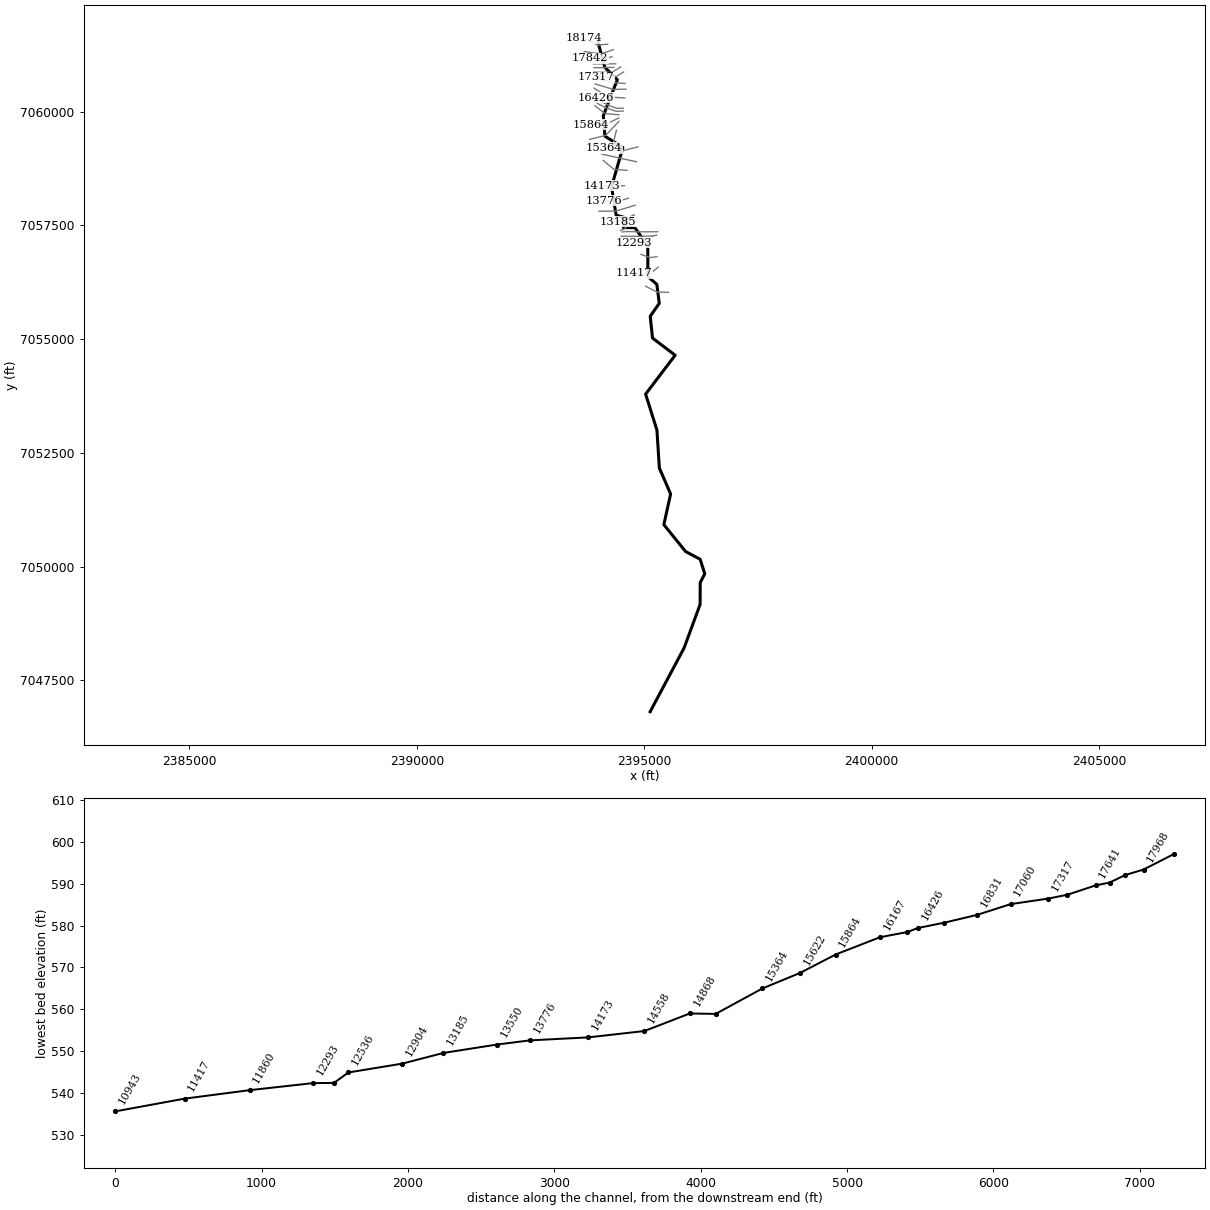
--- Wichita Creek.prj (project) ---

Proj Title=Wichita Creek Base Level Engineering
Current Plan=p01
Default Exp/Contr=0.3,0.1
English Units
Geom File=g01
Flow File=f01
Plan File=p01
Y Axis Title=Elevation
X Axis Title(PF)=Main Channel Distance
X Axis Title(XS)=Station
BEGIN DESCRIPTION:
Wichita Creek
END DESCRIPTION:
DSS Export Rating Curves= 0
DSS Export Rating Curve Sorted= 0
DSS Export Volume Flow Curves= 0
DXF OffsetX= 0
DXF OffsetY= 0
DXF ScaleX= 1
DXF ScaleY= 10

--- Wichita Creek.p01 (plan) ---

Plan Title=Multiple Run
Short Identifier=Multiple
Geom File=g01
Flow File=f01
Subcritical Flow
K Sum by GR= 0
Std Step Tol= 0.01
Critical Tol= 0.01
Num of Std Step Trials= 20
Max Error Tol= 0.3
Flow Tol Ratio= 0.001
Split Flow NTrial= 30
Split Flow Tol= 0.02
Split Flow Ratio= 0.02
Log Output Level= 0
Friction Slope Method= 1
Unsteady Friction Slope Method= 2
Unsteady Bridges Friction Slope Method= 1
Parabolic Critical Depth
Global Vel Dist=  1 , 1 , 1
Global Log Level= 0
CheckData=True
Encroach Param= -1, 0, 0, 0
BEGIN DESCRIPTION:
Multiple Run
END DESCRIPTION:

--- Wichita Creek.f01 (steady flow) ---

Flow Title=Multiple
Program Version=4.10
Number of Profiles= 7
Profile Names=10-year,25-year,50-year,1pct_min,100-year,1pct_plu,500-year
River Rch & RM=Wichita Creek,Reach-1         ,18174
     267     348     412     243     486     969     674
River Rch & RM=Wichita Creek,Reach-1         ,15864
     485     660     804     487     971    1938    1420
River Rch & RM=Wichita Creek,Reach-1         ,15045
     649     893    1095     667    1330    2654    1967
River Rch & RM=Wichita Creek,Reach-1         ,14173
     731    1012    1245     761    1518    3029    2260
River Rch & RM=Wichita Creek,Reach-1         ,12536
     913    1280    1588     977    1949    3889    2946
River Rch & RM=Wichita Creek,Reach-1         ,10943
     947    1326    1645    1011    2016    4023    3041
River Rch & RM=Wichita Creek,Reach-1         ,7316
    1073    1509    1877    1156    2307    4603    3497
River Rch & RM=Wichita Creek,Reach-1         ,5502
    1076    1511    1877    1154    2303    4595    3480
River Rch & RM=Wichita Creek,Reach-1         ,3628
    1966    2821    3552    2207    4404    8788    6780
Boundary for River Rch & Prof#=Wichita Creek,Reach-1         , 1
Up Type= 0
Dn Type= 3
Dn Slope=0.00025
Boundary for River Rch & Prof#=Wichita Creek,Reach-1         , 2
Up Type= 0
Dn Type= 3
Dn Slope=0.00025
Boundary for River Rch & Prof#=Wichita Creek,Reach-1         , 3
Up Type= 0
Dn Type= 3
Dn Slope=0.00025
Boundary for River Rch & Prof#=Wichita Creek,Reach-1         , 4
Up Type= 0
Dn Type= 3
Dn Slope=0.00025
Boundary for River Rch & Prof#=Wichita Creek,Reach-1         , 5
Up Type= 0
Dn Type= 3
Dn Slope=0.00025
Boundary for River Rch & Prof#=Wichita Creek,Reach-1         , 6
Up Type= 0
Dn Type= 3
Dn Slope=0.00025
Boundary for River Rch & Prof#=Wichita Creek,Reach-1         , 7
Up Type= 0
Dn Type= 3
Dn Slope=0.00025
DSS Import GetInterval= 0
DSS Import GetPeak= 0
DSS Import FillOption= 0

--- Wichita Creek.g01 (geometry) ---

Geom Title=Existing Conditions

River Reach=Wichita Creek,Reach-1
Reach XY= 30
      2393979.08      7061539.88      2394130.23      7060973.53
      2394407.51      7060698.92      2394099.66      7059909.49
      2394134.46      7059457.55      2394529.00      7059210.00
      2394279.49      7058344.78      2394380.62      7057721.81
      2394624.44      7057654.81      2394539.02      7057449.94
      2394792.39      7057446.65      2395075.93      7057051.70
      2395079.94      7056370.48      2395275.93      7056201.70
      2395329.40      7055785.00      2395130.19      7055499.52
      2395180.62      7055021.83      2395678.78      7054644.00
      2395028.94      7053790.01      2395277.78      7052999.50
      2395331.24      7052165.93      2395578.49      7051594.79
      2395430.20      7050920.50      2395908.91      7050329.78
      2396229.00      7050160.00      2396329.29      7049839.82
      2396230.20      7049649.50      2396226.74      7049165.94
      2395875.38      7048211.50      2395129.00      7046810.00

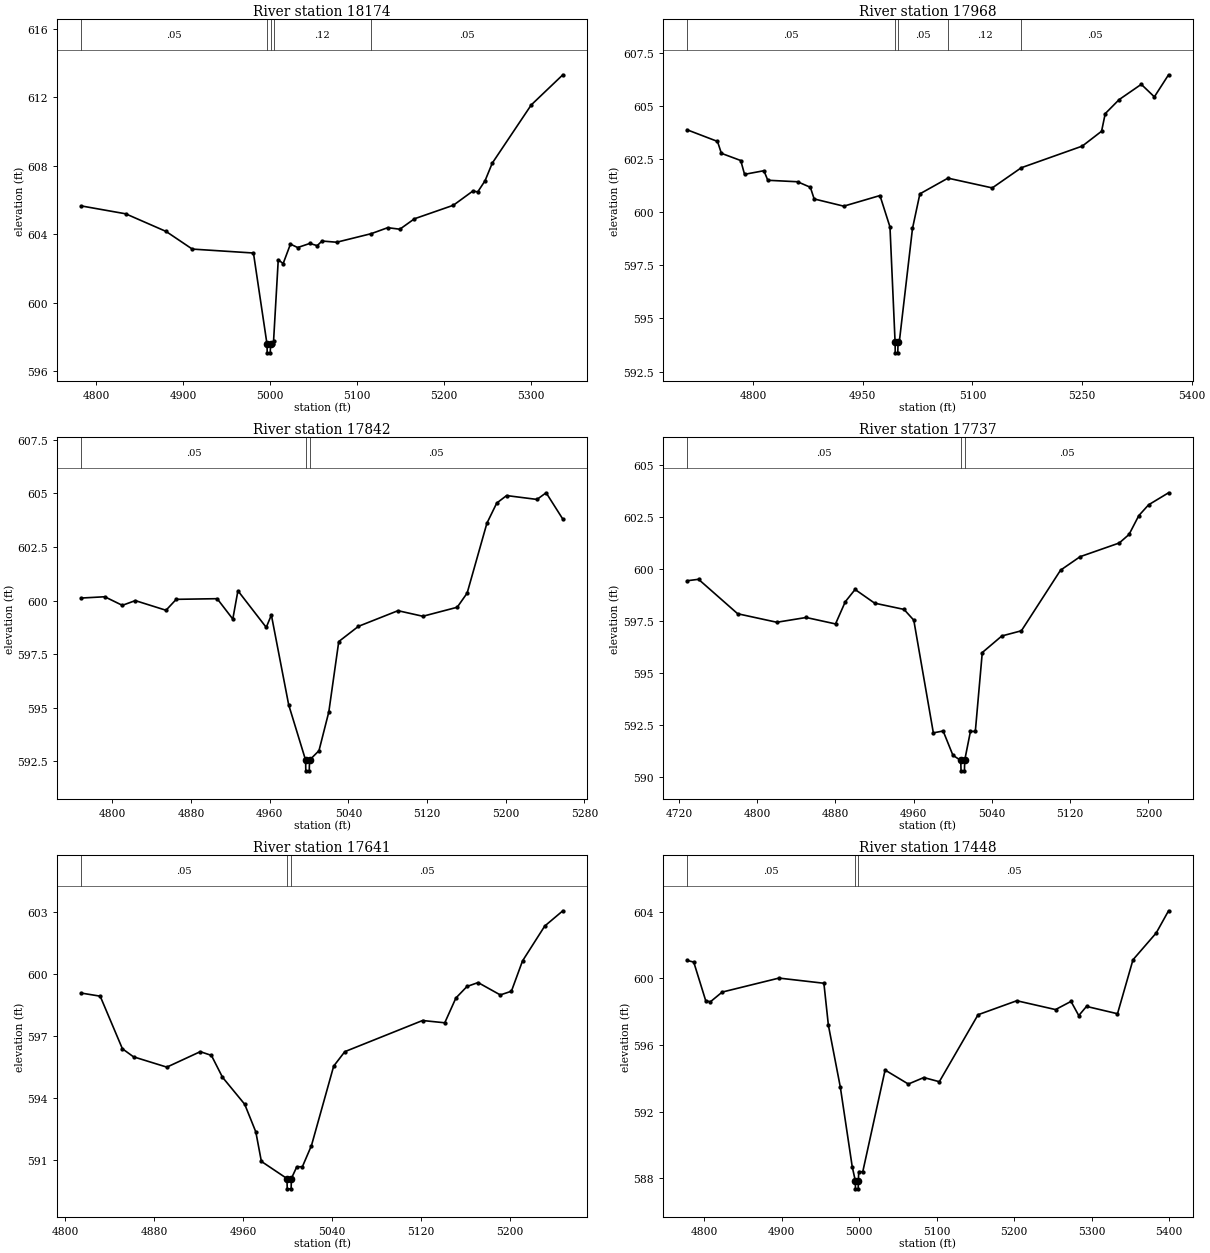
Type RM Length L Ch R = 1,18174,206,206,206
BEGIN DESCRIPTION:
Wichita Creek 41.0
END DESCRIPTION:
XS GIS Cut Line= 3
      2394196.03      7061479.45      2393979.00      7061460.00
      2393679.01      7061610.00
#Sta/Elev= 30
  4783.1  605.64  4834.1  605.18  4880.5  604.15  4910.6  603.12  4980.9  602.89
  4996.5  597.56  4996.7  597.06  5000.2  597.06  5000.5  597.56  5003.8  597.56
  5004.0  597.74  5009.4  602.50  5015.0  602.27  5023.4  603.41  5031.7  603.21
  5045.7  603.45  5054.1  603.32  5059.7  603.59  5076.5  603.52  5116.2  604.02
  5135.2  604.37  5149.1  604.28  5165.9  604.89  5210.6  605.68  5233.0  606.51
  5238.6  606.46  5247.0  607.11  5255.3  608.14  5300.1  611.54  5336.4  613.30
#Mann=5,-1,0
  4783.1    0.05       0  4996.5   0.033       0  5000.5    0.05       0
  5004.0    0.12       0  5116.2    0.05       0
Bank Sta=4996.5,5000.5
Exp/Cntr=0.3,0.1

Type RM Length L Ch R = 1,17968,126,126,126
BEGIN DESCRIPTION:
Wichita Creek 40.0
END DESCRIPTION:
XS GIS Cut Line= 3
      2394322.58      7061358.45      2394046.95      7061267.36
      2393682.04      7061317.25
#Sta/Elev= 30
  4709.7  603.89  4751.4  603.34  4756.7  602.78  4783.2  602.44  4788.4  601.79
  4814.9  601.96  4820.2  601.51  4860.9  601.44  4878.4  601.18  4883.6  600.63
  4924.1  600.29  4973.6  600.79  4987.3  599.31  4994.3  593.88  4994.5  593.38
  4998.0  593.38  4998.3  593.88  5000.0  593.88  5018.1  599.24  5028.2  600.87
  5066.6  601.61  5127.2  601.15  5166.9  602.10  5250.3  603.12  5276.7  603.82
  5281.7  604.65  5300.7  605.31  5331.0  606.03  5348.9  605.44  5368.3  606.48
#Mann=5,-1,0
  4709.7    0.05       0  4994.3   0.033       0  4998.3    0.05       0
  5066.6    0.12       0  5166.9    0.05       0
Bank Sta=4994.3,4998.3
Exp/Cntr=0.3,0.1

Type RM Length L Ch R = 1,17842,105,105,105
BEGIN DESCRIPTION:
Mapping XS 52a94561
END DESCRIPTION:
XS GIS Cut Line= 3
      2394291.87      7061206.96      2394070.56      7061144.47
      2393812.07      7061167.74
#Sta/Elev= 30
  4768.5  600.12  4792.3  600.18  4810.2  599.78  4823.4  600.00  4854.6  599.55
  4865.0  600.06  4906.6  600.09  4922.5  599.14  4927.7  600.46  4956.5  598.75
  4961.7  599.33  4979.3  595.14  4996.5  592.56  4996.7  592.06  5000.2  592.06
  5000.5  592.56  5010.1  593.00  5020.1  594.81  5030.2  598.09  5050.2  598.80
  5090.4  599.53  5115.7  599.27  5150.6  599.69  5160.7  600.35  5180.8  603.61
  5190.8  604.55  5200.8  604.90  5231.7  604.72  5241.0  605.03  5258.0  603.80
#Mann=3,-1,0
  4768.5    0.05       0  4996.5   0.033       0  5000.5    0.05       0
Bank Sta=4996.5,5000.5
Exp/Cntr=0.3,0.1

Type RM Length L Ch R = 1,17737,96,96,96
BEGIN DESCRIPTION:
Mapping XS e7f1a3a4
END DESCRIPTION:
XS GIS Cut Line= 3
      2394370.80      7061047.81      2394078.30      7061047.81
      2393878.61      7061046.07
#Sta/Elev= 30
  4728.3  599.44  4740.1  599.51  4780.1  597.85  4820.1  597.44  4850.1  597.67
  4880.1  597.36  4890.1  598.43  4900.1  599.02  4920.1  598.36  4950.1  598.06
  4960.1  597.54  4980.1  592.11  4990.1  592.20  5000.1  591.03  5008.1  590.78
  5008.4  590.28  5011.9  590.28  5012.1  590.78  5018.0  592.18  5023.0  592.18
  5030.1  595.98  5050.1  596.78  5070.1  597.03  5110.1  599.95  5130.1  600.60
  5170.1  601.26  5180.1  601.67  5190.1  602.58  5200.1  603.10  5220.5  603.68
#Mann=3,-1,0
  4728.3    0.05       0  5008.1    0.05       0  5012.1    0.05       0
Bank Sta=5008.1,5012.1
Exp/Cntr=0.3,0.1

Type RM Length L Ch R = 1,17641,193,193,193
BEGIN DESCRIPTION:
Wichita Creek 39.0
END DESCRIPTION:
XS GIS Cut Line= 3
      2394325.96      7060972.11      2394130.25      7060963.51
      2393892.65      7060963.43
#Sta/Elev= 30
  4814.4  599.09  4831.4  598.94  4851.4  596.39  4861.4  596.00  4891.4  595.50
  4921.5  596.25  4931.5  596.07  4941.5  595.01  4961.5  593.70  4971.5  592.36
  4976.5  590.93  4999.5  590.10  4999.8  589.60  5003.3  589.60  5003.5  590.10
  5008.4  590.67  5013.4  590.67  5021.6  591.70  5041.6  595.55  5051.6  596.25
  5121.6  597.76  5141.6  597.65  5151.6  598.85  5161.6  599.41  5171.6  599.60
  5191.6  599.00  5201.6  599.18  5211.6  600.65  5231.6  602.34  5247.9  603.08
#Mann=3,-1,0
  4814.4    0.05       0  4999.5    0.05       0  5003.5    0.05       0
Bank Sta=4999.5,5003.5
Exp/Cntr=0.3,0.1

Type RM Length L Ch R = 1,17448,131,131,131
BEGIN DESCRIPTION:
Mapping XS 87a5d836
END DESCRIPTION:
XS GIS Cut Line= 3
      2394481.48      7060979.55      2394291.58      7060862.35
      2393893.15      7060865.60
#Sta/Elev= 30
  4777.8  601.08  4786.5  600.98  4801.9  598.67  4807.8  598.59  4823.2  599.18
  4896.5  600.02  4954.5  599.71  4960.3  597.19  4975.7  593.48  4991.1  588.69
  4995.0  587.87  4995.3  587.37  4998.8  587.37  4999.0  587.87  4999.5  588.40
  5004.7  588.40  5033.5  594.50  5063.5  593.66  5083.5  594.05  5103.5  593.80
  5153.5  597.82  5203.5  598.66  5253.5  598.13  5273.5  598.62  5283.5  597.77
  5293.5  598.32  5333.5  597.88  5353.5  601.12  5383.5  602.73  5399.4  604.06
#Mann=3,-1,0
  4777.8    0.05       0  4995.0   0.033       0  4999.0    0.05       0
Bank Sta=4995,4999
Exp/Cntr=0.3,0.1

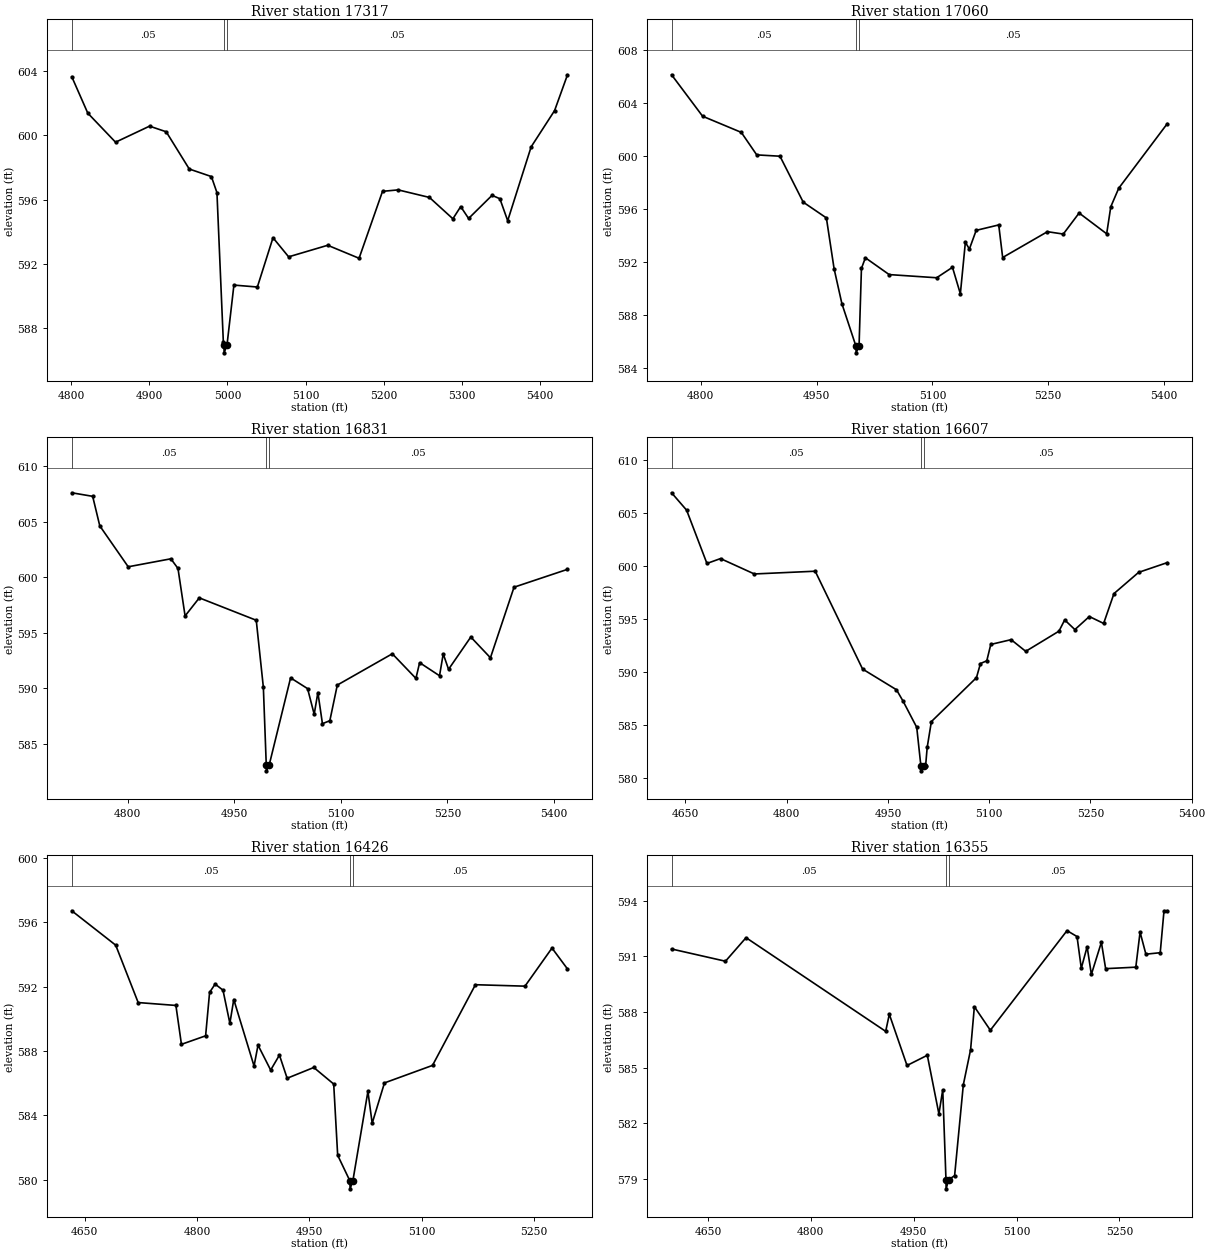
Type RM Length L Ch R = 1,17317,257,257,257
BEGIN DESCRIPTION:
Mapping XS 134eca66
END DESCRIPTION:
XS GIS Cut Line= 3
      2394546.56      7060868.85      2394379.47      7060764.70
      2393942.53      7060749.56
#Sta/Elev= 30
  4800.9  603.65  4821.4  601.38  4856.9  599.57  4900.4  600.57  4921.7  600.22
  4951.2  597.90  4979.5  597.43  4986.6  596.43  4994.8  587.10  4995.5  586.95
  4995.8  586.45  4999.5  586.95  5008.3  590.67  5038.3  590.55  5058.3  593.62
  5078.3  592.43  5128.3  593.15  5168.4  592.34  5198.4  596.51  5218.4  596.60
  5258.4  596.13  5288.4  594.80  5298.4  595.56  5308.5  594.82  5338.5  596.26
  5348.5  596.05  5358.5  594.68  5388.5  599.28  5418.5  601.54  5435.0  603.77
#Mann=3,-1,0
  4800.9    0.05       0  4995.5   0.033       0  4999.5    0.05       0
Bank Sta=4995.5,4999.5
Exp/Cntr=0.3,0.1

Type RM Length L Ch R = 1,17060,229,229,229
BEGIN DESCRIPTION:
Mapping XS b63a11f3
END DESCRIPTION:
XS GIS Cut Line= 3
      2394579.09      7060617.13      2394345.84      7060632.32
      2393947.64      7060722.37
#Sta/Elev= 30
  4762.1  606.13  4802.3  603.00  4852.4  601.78  4872.4  600.08  4902.5  599.98
  4932.6  596.51  4962.6  595.32  4972.6  591.48  4982.7  588.84  5000.9  585.63
  5001.1  585.13  5004.9  585.63  5008.0  591.50  5013.1  592.31  5043.9  591.04
  5105.4  590.80  5125.9  591.59  5136.1  589.59  5142.6  593.48  5147.8  592.97
  5156.6  594.38  5185.8  594.79  5190.9  592.33  5248.9  594.28  5269.4  594.10
  5289.9  595.69  5325.6  594.12  5330.9  596.16  5341.2  597.56  5404.1  602.44
#Mann=3,-1,0
  4762.1    0.05       0  5000.9   0.033       0  5004.9    0.05       0
Bank Sta=5000.9,5004.9
Exp/Cntr=0.3,0.1

Type RM Length L Ch R = 1,16831,224,224,224
BEGIN DESCRIPTION:
Mapping XS 77a60943
END DESCRIPTION:
XS GIS Cut Line= 3
      2394598.40      7060490.97      2394321.68      7060485.55
      2393918.62      7060605.49
#Sta/Elev= 30
  4721.5  607.62  4750.9  607.30  4760.9  604.64  4800.9  600.95  4860.9  601.67
  4870.9  600.80  4880.9  596.52  4900.9  598.15  4981.0  596.13  4991.0  590.09
  4995.1  583.06  4995.4  582.56  4999.1  583.06  5029.3  590.94  5053.2  589.97
  5062.5  587.66  5067.7  589.62  5074.1  586.81  5084.5  587.08  5095.0  590.29
  5172.4  593.11  5205.6  590.89  5210.8  592.31  5238.8  591.13  5244.0  593.10
  5251.5  591.71  5282.8  594.62  5310.4  592.75  5343.6  599.11  5418.8  600.72
#Mann=3,-1,0
  4721.5    0.05       0  4995.1   0.033       0  4999.1    0.05       0
Bank Sta=4995.1,4999.1
Exp/Cntr=0.3,0.1

Type RM Length L Ch R = 1,16607,181,181,181
BEGIN DESCRIPTION:
Mapping XS 443a4b26
END DESCRIPTION:
XS GIS Cut Line= 3
      2394571.28      7060295.65      2394197.98      7060322.78
      2393893.15      7060514.51
#Sta/Elev= 30
  4629.4  606.90  4651.7  605.26  4681.8  600.24  4701.9  600.70  4752.0  599.25
  4842.2  599.51  4912.4  590.29  4962.6  588.34  4972.6  587.24  4992.6  584.80
  4998.7  581.20  4998.9  580.70  5002.7  581.20  5005.8  581.20  5008.1  582.91
  5014.3  585.34  5081.1  589.48  5087.0  590.81  5096.4  591.07  5102.3  592.61
  5132.4  593.06  5154.1  591.96  5203.3  593.86  5211.8  594.92  5226.9  594.01
  5248.3  595.24  5269.5  594.59  5284.8  597.40  5321.3  599.40  5363.8  600.32
#Mann=3,-1,0
  4629.4    0.05       0  4998.7   0.033       0  5002.7    0.05       0
Bank Sta=4998.7,5002.7
Exp/Cntr=0.3,0.1

Type RM Length L Ch R = 1,16426,71,71,71
BEGIN DESCRIPTION:
Wichita Creek 36.0
END DESCRIPTION:
XS GIS Cut Line= 6
      2394537.71      7060072.33      2394406.67      7060069.73
      2394293.82      7060105.32      2394185.49      7060149.24
      2394113.27      7060186.92      2393934.45      7060304.97
#Sta/Elev= 30
  4632.7  596.72  4691.4  594.58  4721.4  591.01  4771.8  590.83  4779.2  588.41
  4811.5  588.94  4816.8  591.64  4824.2  592.16  4834.7  591.78  4843.9  589.72
  4849.1  591.20  4876.2  587.06  4881.5  588.36  4898.4  586.81  4910.1  587.74
  4920.4  586.30  4956.0  586.97  4982.6  585.94  4987.9  581.51  5004.2  579.92
  5004.5  579.42  5008.2  579.92  5028.3  585.48  5034.0  583.50  5050.4  586.01
  5114.6  587.10  5171.9  592.12  5238.1  592.03  5274.2  594.40  5294.9  593.10
#Mann=3,-1,0
  4632.7    0.05       0  5004.2    0.05       0  5008.2    0.05       0
Bank Sta=5004.2,5008.2
Exp/Cntr=0.3,0.1

Type RM Length L Ch R = 1,16355,188,188,188
BEGIN DESCRIPTION:
Mapping XS a8476fcf
END DESCRIPTION:
XS GIS Cut Line= 6
      2394537.54      7060011.05      2394404.93      7060005.49
      2394365.35      7060009.66      2394188.46      7060070.24
      2394001.46      7060158.27      2393875.05      7060250.65
#Sta/Elev= 30
  4596.9  591.40  4675.5  590.74  4705.5  592.01  4909.1  586.96  4914.4  587.88
  4940.2  585.12  4969.8  585.67  4986.7  582.51  4992.3  583.81  4997.0  578.97
  4997.2  578.47  5001.0  578.97  5009.6  579.18  5022.3  584.08  5032.9  585.97
  5038.4  588.29  5061.7  587.02  5173.5  592.39  5188.1  592.07  5194.3  590.36
  5202.8  591.52  5209.0  590.03  5223.6  591.76  5229.8  590.34  5273.8  590.42
  5280.0  592.31  5288.5  591.12  5309.4  591.20  5314.9  593.46  5319.7  593.46
#Mann=3,-1,0
  4596.9    0.05       0  4997.0    0.05       0  5001.0    0.05       0
Bank Sta=4997,5001
Exp/Cntr=0.3,0.1

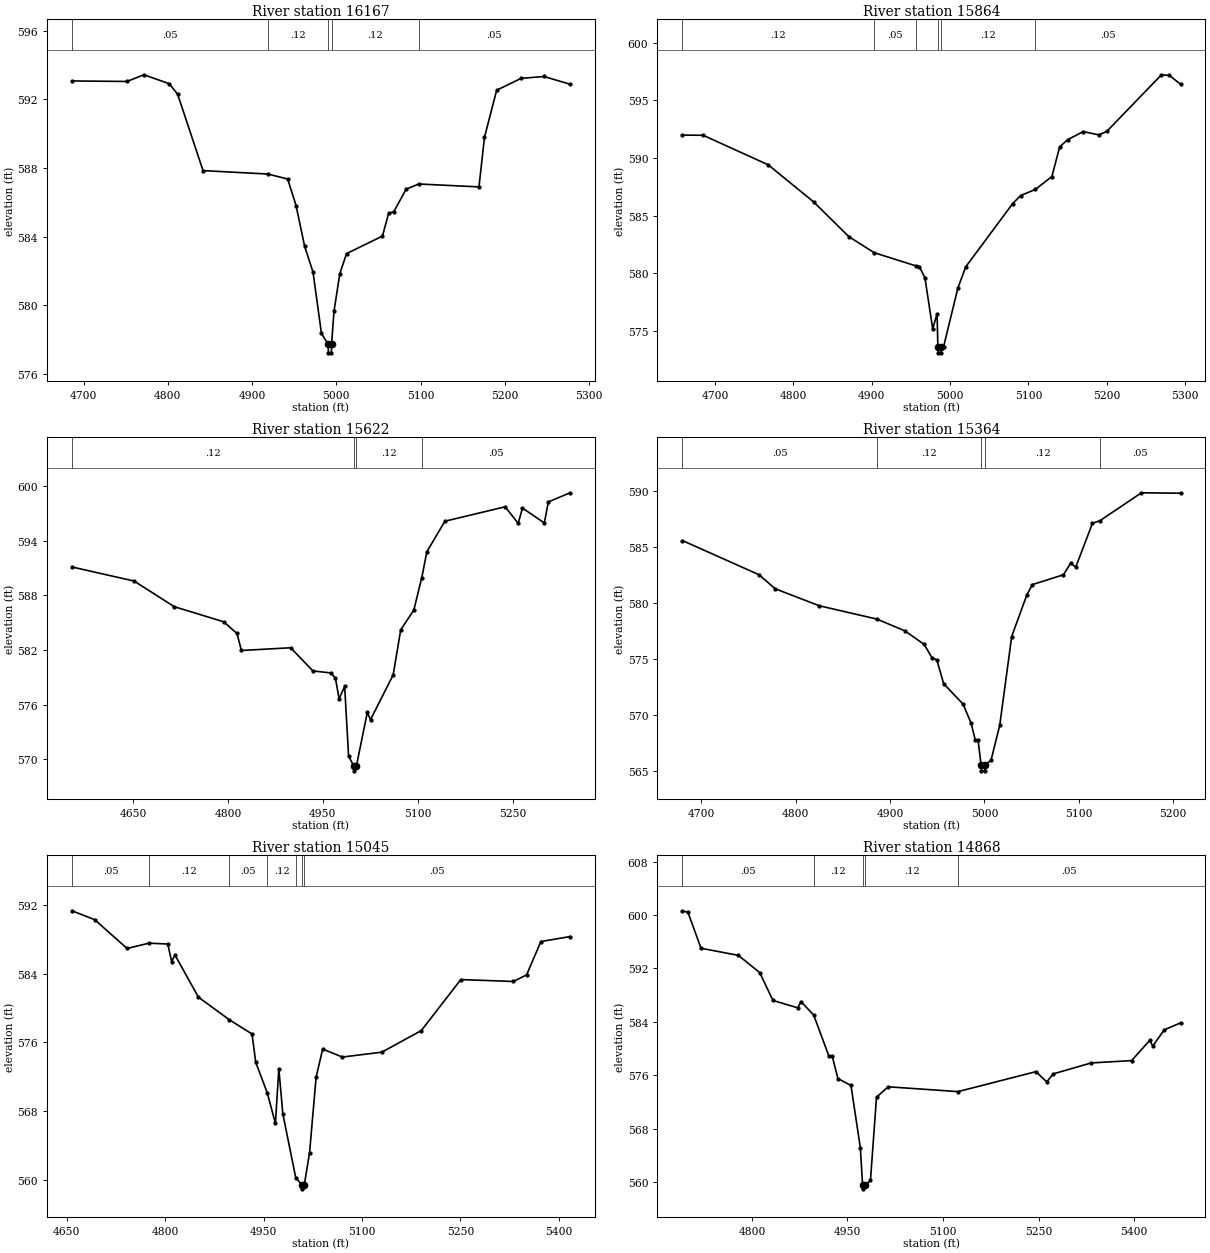
Type RM Length L Ch R = 1,16167,303,303,303
BEGIN DESCRIPTION:
Mapping XS 2700da94
END DESCRIPTION:
XS GIS Cut Line= 3
      2394444.09      7059928.47      2394134.21      7059954.51
      2393914.15      7060127.69
#Sta/Elev= 30
  4686.2  593.08  4751.5  593.05  4771.6  593.44  4801.7  592.92  4811.7  592.30
  4841.8  587.85  4918.7  587.65  4942.2  587.36  4952.2  585.81  4962.3  583.44
  4972.3  581.93  4982.3  578.35  4990.3  577.72  4990.5  577.22  4994.0  577.22
  4994.3  577.72  4997.2  579.65  5004.1  581.84  5012.1  583.01  5054.7  584.03
  5061.9  585.35  5068.2  585.46  5082.7  586.76  5097.7  587.07  5169.2  586.90
  5175.7  589.79  5190.2  592.54  5219.1  593.23  5246.2  593.34  5277.2  592.89
#Mann=5,-1,0
  4686.2    0.05       0  4918.7    0.12       0  4990.3    0.07       0
  4994.3    0.12       0  5097.7    0.05       0
Bank Sta=4990.3,4994.3
Exp/Cntr=0.3,0.1

Type RM Length L Ch R = 1,15864,242,242,242
BEGIN DESCRIPTION:
Mapping XS e75b4bef
END DESCRIPTION:
XS GIS Cut Line= 3
      2394437.58      7059856.85      2394140.72      7059712.32
      2393834.69      7059713.63
#Sta/Elev= 30
  4658.1  591.98  4684.7  591.96  4767.7  589.40  4825.6  586.19  4870.7  583.17
  4903.0  581.78  4956.9  580.62  4960.8  580.57  4967.9  579.59  4977.8  575.17
  4983.4  576.48  4984.4  573.59  4984.7  573.09  4988.2  573.09  4988.4  573.59
  4991.6  573.59  5010.0  578.72  5020.0  580.55  5080.0  586.04  5090.0  586.73
  5108.8  587.26  5130.0  588.38  5140.0  590.96  5150.0  591.57  5170.0  592.28
  5190.0  592.00  5200.0  592.29  5270.0  597.21  5280.0  597.16  5294.3  596.39
#Mann=6,-1,0
  4658.1    0.12       0  4903.0    0.05       0  4956.9    0.12       0
  4984.4    0.07       0  4988.4    0.12       0  5108.8    0.05       0
Bank Sta=4984.4,4988.4
Exp/Cntr=0.3,0.1

Type RM Length L Ch R = 1,15622,258,258,258
BEGIN DESCRIPTION:
Mapping XS c7c3c0c9
END DESCRIPTION:
XS GIS Cut Line= 3
      2394442.80      7059785.24      2394152.44      7059476.65
      2393799.62      7059386.81
#Sta/Elev= 30
  4553.1  591.14  4651.5  589.59  4715.0  586.77  4793.1  585.11  4814.2  583.82
  4821.2  581.95  4899.1  582.25  4934.3  579.70  4962.7  579.48  4969.9  578.91
  4975.7  576.64  4984.5  578.00  4990.7  570.35  4999.0  569.21  4999.3  568.71
  5003.0  569.21  5020.3  575.13  5025.4  574.34  5061.2  579.26  5073.2  584.23
  5093.9  586.40  5106.4  589.94  5114.5  592.81  5143.0  596.17  5238.3  597.76
  5259.0  595.94  5265.7  597.62  5300.3  595.98  5306.6  598.29  5340.9  599.30
#Mann=4,-1,0
  4553.1    0.12       0  4999.0    0.07       0  5003.0    0.12       0
  5106.4    0.05       0
Bank Sta=4999,5003
Exp/Cntr=0.3,0.1

Type RM Length L Ch R = 1,15364,319,319,319
BEGIN DESCRIPTION:
Mapping XS e06bb45c
END DESCRIPTION:
XS GIS Cut Line= 3
      2394387.86      7059588.92      2394313.64      7059286.85
      2394115.70      7059198.30
#Sta/Elev= 30
  4679.9  585.58  4761.2  582.52  4778.2  581.27  4824.9  579.75  4885.9  578.56
  4915.6  577.51  4936.2  576.29  4944.5  575.09  4949.6  574.90  4956.8  572.78
  4977.4  570.95  4986.0  569.23  4990.2  567.76  4993.2  567.76  4996.5  565.49
  4996.7  564.99  5000.2  564.99  5000.5  565.49  5007.0  565.94  5016.2  569.05
  5028.9  577.00  5044.9  580.71  5050.8  581.64  5083.7  582.52  5091.3  583.54
  5096.8  583.21  5114.5  587.12  5122.5  587.36  5166.4  589.85  5207.8  589.81
#Mann=5,-1,0
  4679.9    0.05       0  4885.9    0.12       0  4996.5    0.07       0
  5000.5    0.12       0  5122.5    0.05       0
Bank Sta=4996.5,5000.5
Exp/Cntr=0.3,0.1

Type RM Length L Ch R = 1,15045,177,177,177
BEGIN DESCRIPTION:
Wichita Creek 33.0
END DESCRIPTION:
XS GIS Cut Line= 3
      2394860.59      7059222.80      2394529.03      7059138.16
      2394112.93      7059168.46
#Sta/Elev= 30
  4657.8  591.37  4692.4  590.34  4742.0  586.97  4775.3  587.59  4803.9  587.49
  4809.9  585.45  4815.0  586.20  4850.7  581.29  4897.5  578.67  4932.4  576.99
  4938.1  573.69  4955.8  570.09  4968.1  566.55  4973.3  572.95  4979.4  567.67
  4999.1  560.21  5008.0  559.42  5008.3  558.92  5012.2  559.42  5020.1  563.10
  5030.1  571.93  5040.1  575.23  5070.2  574.30  5130.4  574.87  5190.5  577.39
  5250.7  583.34  5330.9  583.12  5351.0  583.89  5372.8  587.78  5417.2  588.36
#Mann=7,-1,0
  4657.8    0.05       0  4775.3    0.12       0  4897.5    0.05       0
  4955.8    0.12       0  4999.1    0.05       0  5008.0   0.033       0
  5012.2    0.05       0
Bank Sta=5008,5012.2
Exp/Cntr=0.3,0.1

Type RM Length L Ch R = 1,14868,310,310,310
BEGIN DESCRIPTION:
Mapping XS b24434da
END DESCRIPTION:
XS GIS Cut Line= 3
      2394827.62      7058895.86      2394525.47      7058961.46
      2394064.05      7059065.03
#Sta/Elev= 30
  4690.8  600.63  4699.6  600.38  4720.1  595.02  4778.7  593.96  4812.2  591.38
  4833.0  587.21  4871.9  586.11  4877.0  587.04  4897.0  585.02  4921.0  578.85
  4926.1  578.87  4935.0  575.52  4955.5  574.49  4970.2  565.17  4973.8  559.52
  4974.1  559.02  4978.0  559.52  4986.1  560.27  4995.6  572.74  5013.9  574.29
  5123.6  573.57  5246.0  576.56  5262.8  575.03  5273.1  576.22  5332.6  577.86
  5396.1  578.21  5424.4  581.22  5429.5  580.41  5447.3  582.81  5472.9  583.85
#Mann=5,-1,0
  4690.8    0.05       0  4897.0    0.12       0  4973.8    0.07       0
  4978.0    0.12       0  5123.6    0.05       0
Bank Sta=4973.8,4978
Exp/Cntr=0.3,0.1

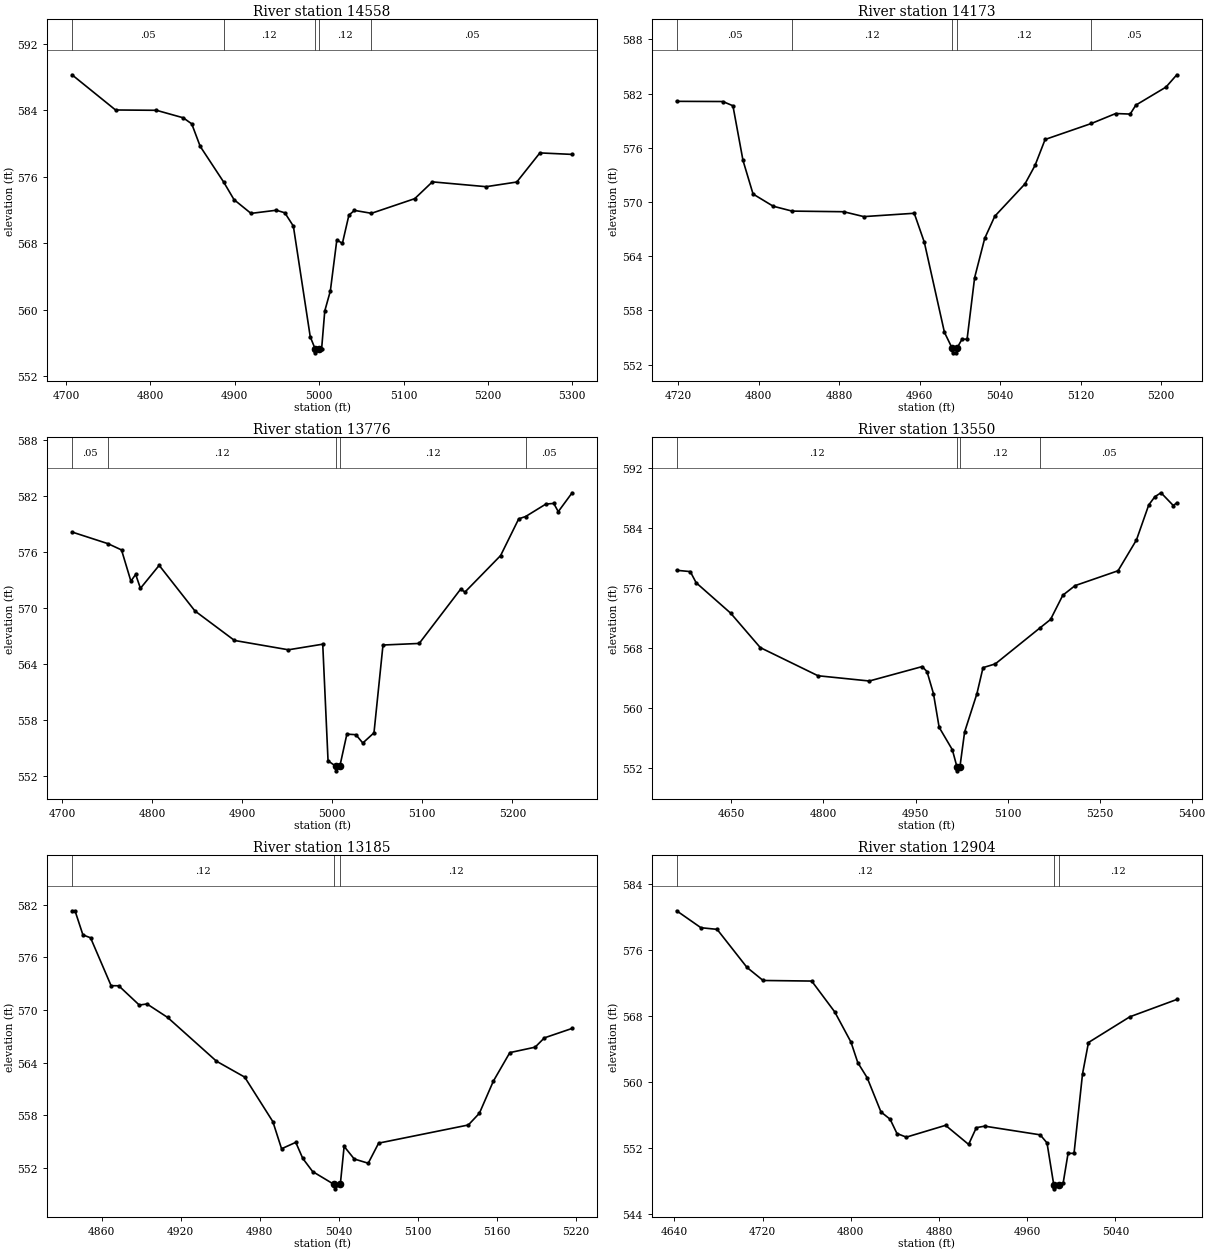
Type RM Length L Ch R = 1,14558,385,385,385
BEGIN DESCRIPTION:
Wichita Creek 32.0
END DESCRIPTION:
XS GIS Cut Line= 3
      2394620.42      7058706.70      2394328.57      7058730.18
      2394099.58      7058923.69
#Sta/Elev= 30
  4707.2  588.25  4758.8  584.02  4807.3  583.98  4839.0  583.08  4849.1  582.35
  4859.1  579.65  4886.9  575.36  4899.2  573.24  4919.3  571.59  4949.4  571.97
  4959.4  571.66  4969.5  570.06  4989.5  556.76  4995.2  555.33  4995.5  554.83
  4999.4  555.33  5003.0  555.33  5006.7  559.86  5013.3  562.26  5021.0  568.40
  5027.6  567.99  5035.3  571.38  5041.9  571.95  5062.0  571.60  5113.3  573.36
  5134.2  575.38  5197.9  574.80  5234.2  575.36  5261.6  578.86  5299.8  578.68
#Mann=5,-1,0
  4707.2    0.05       0  4886.9    0.12       0  4995.2    0.07       0
  4999.4    0.12       0  5062.0    0.05       0
Bank Sta=4995.2,4999.4
Exp/Cntr=0.3,0.1

Type RM Length L Ch R = 1,14173,397,397,397
BEGIN DESCRIPTION:
Wichita Creek 31.0
END DESCRIPTION:
XS GIS Cut Line= 3
      2394564.83      7058369.90      2394279.00      7058360.00
      2394068.30      7058366.43
#Sta/Elev= 30
  4718.6  581.15  4764.5  581.13  4774.5  580.66  4784.5  574.61  4794.5  570.89
  4814.5  569.54  4833.3  569.00  4884.5  568.93  4904.5  568.39  4954.6  568.76
  4964.6  565.56  4984.6  555.58  4992.3  553.81  4992.7  553.31  4996.4  553.31
  4996.9  553.81  5002.1  554.82  5007.1  554.82  5014.6  561.64  5024.6  565.98
  5034.6  568.43  5064.6  572.01  5074.6  574.06  5084.6  576.93  5130.6  578.70
  5154.7  579.80  5169.1  579.74  5174.7  580.73  5204.7  582.73  5215.4  584.09
#Mann=5,-1,0
  4718.6    0.05       0  4833.3    0.12       0  4992.3    0.07       0
  4996.9    0.12       0  5130.6    0.05       0
Bank Sta=4992.3,4996.9
Exp/Cntr=0.3,0.1

Type RM Length L Ch R = 1,13776,226,226,226
BEGIN DESCRIPTION:
Wichita Creek 30.0
END DESCRIPTION:
XS GIS Cut Line= 3
      2394651.60      7058095.59      2394375.09      7058011.57
      2394109.96      7058036.57
#Sta/Elev= 30
  4711.0  578.17  4751.0  576.92  4766.0  576.25  4776.4  572.91  4781.7  573.63
  4787.0  572.14  4807.8  574.60  4847.5  569.72  4891.4  566.56  4951.3  565.56
  4989.4  566.16  4995.3  553.67  5003.8  553.10  5004.3  552.60  5008.4  553.10
  5016.2  556.53  5026.2  556.47  5033.9  555.58  5046.3  556.67  5056.3  566.07
  5096.5  566.24  5142.4  572.04  5147.4  571.75  5186.9  575.65  5207.0  579.58
  5214.7  579.83  5237.1  581.16  5245.9  581.23  5250.9  580.35  5266.3  582.37
#Mann=5,-1,0
  4711.0    0.05       0  4751.0    0.12       0  5003.8    0.07       0
  5008.4    0.12       0  5214.7    0.05       0
Bank Sta=5003.8,5008.4
Exp/Cntr=0.3,0.1

Type RM Length L Ch R = 1,13550,365,365,365
BEGIN DESCRIPTION:
Mapping XS 285bc2a9
END DESCRIPTION:
XS GIS Cut Line= 3
      2394799.41      7057940.16      2394381.02      7057813.43
      2394003.32      7057808.23
#Sta/Elev= 30
  4560.8  578.32  4583.0  578.15  4592.6  576.66  4648.8  572.61  4697.1  568.02
  4791.1  564.27  4874.7  563.57  4960.8  565.49  4968.7  564.83  4979.2  561.90
  4988.5  557.40  5010.0  554.41  5017.6  552.10  5018.1  551.60  5022.3  552.10
  5030.0  556.78  5050.0  561.87  5060.0  565.35  5080.0  565.85  5153.0  570.66
  5170.0  571.77  5190.0  575.00  5210.0  576.28  5280.0  578.26  5310.0  582.37
  5330.0  587.03  5340.0  588.13  5350.0  588.65  5370.0  586.95  5375.7  587.32
#Mann=4,-1,0
  4560.8    0.12       0  5017.6    0.07       0  5022.3    0.12       0
  5153.0    0.05       0
Bank Sta=5017.6,5022.3
Exp/Cntr=0.3,0.1

Type RM Length L Ch R = 1,13185,281,281,281
BEGIN DESCRIPTION:
Wichita Creek 29.0
END DESCRIPTION:
XS GIS Cut Line= 3
      2394767.99      7057731.04      2394628.01      7057648.31
      2394422.35      7057578.78
#Sta/Elev= 30
  4837.4  581.30  4839.7  581.30  4845.7  578.55  4851.5  578.22  4867.1  572.76
  4872.9  572.75  4888.5  570.55  4894.3  570.68  4910.0  569.14  4947.1  564.15
  4968.5  562.34  4989.9  557.26  4996.5  554.17  5007.3  554.90  5012.6  553.07
  5020.1  551.57  5036.4  550.10  5036.9  549.60  5041.1  550.10  5044.0  554.44
  5051.7  553.00  5062.3  552.52  5070.2  554.81  5138.3  556.88  5146.7  558.22
  5157.3  561.88  5169.8  565.13  5189.0  565.75  5196.0  566.81  5217.1  567.89
#Mann=3,-1,0
  4837.4    0.12       0  5036.4    0.07       0  5041.1    0.12       0
Bank Sta=5036.4,5041.1
Exp/Cntr=0.3,0.1

Type RM Length L Ch R = 1,12904,368,368,368
BEGIN DESCRIPTION:
Wichita Creek 28.0
END DESCRIPTION:
XS GIS Cut Line= 3
      2394778.99      7057709.99      2394568.76      7057420.34
      2394479.00      7057387.16
#Sta/Elev= 30
  4642.1  580.72  4664.1  578.67  4678.8  578.47  4705.9  573.86  4720.5  572.28
  4764.6  572.21  4785.5  568.47  4800.2  564.82  4806.4  562.33  4814.9  560.50
  4827.4  556.36  4835.7  555.48  4841.9  553.75  4850.4  553.31  4886.0  554.74
  4906.9  552.43  4913.9  554.46  4921.5  554.64  4971.8  553.59  4978.0  552.61
  4984.1  547.55  4984.6  547.05  4988.8  547.55  4992.7  547.80  4997.1  551.35
  5002.5  551.35  5010.2  560.97  5015.6  564.77  5053.1  567.88  5095.7  569.98
#Mann=3,-1,0
  4642.1    0.12       0  4984.1    0.07       0  4988.8    0.12       0
Bank Sta=4984.1,4988.8
Exp/Cntr=0.3,0.1

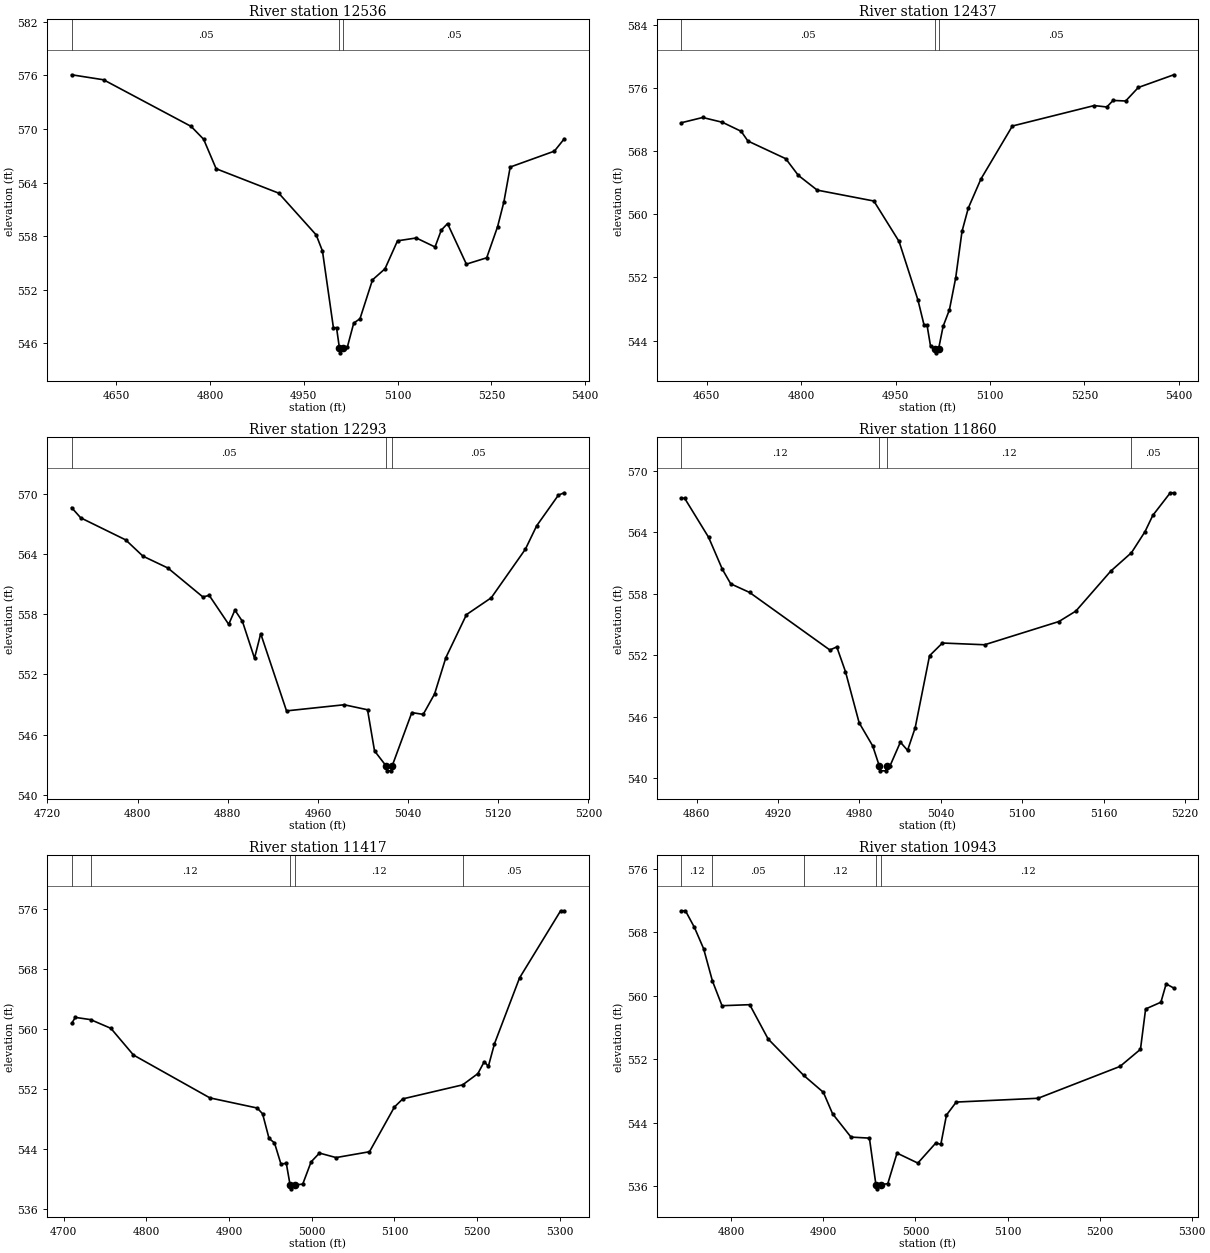
Type RM Length L Ch R = 1,12536,99,99,99
BEGIN DESCRIPTION:
Mapping XS 9755d4a4
END DESCRIPTION:
XS GIS Cut Line= 4
      2395300.08      7057357.75      2394878.98      7057356.08
      2394636.47      7057362.75      2394512.92      7057353.49
#Sta/Elev= 30
  4578.9  576.07  4630.0  575.51  4770.0  570.29  4790.0  568.85  4810.0  565.55
  4910.0  562.82  4970.0  558.14  4980.0  556.34  4997.5  547.76  5002.5  547.76
  5007.2  545.44  5008.0  544.94  5012.7  545.44  5020.0  545.64  5030.0  548.27
  5040.0  548.76  5060.0  553.11  5080.0  554.35  5100.0  557.48  5130.0  557.80
  5160.0  556.79  5170.0  558.68  5180.0  559.41  5210.1  554.87  5242.6  555.58
  5260.1  559.08  5270.1  561.84  5280.2  565.74  5350.8  567.52  5366.5  568.89
#Mann=3,-1,0
  4578.9    0.05       0  5007.2    0.05       0  5012.7    0.05       0
Bank Sta=5007.2,5012.7
Exp/Cntr=0.3,0.1

Type RM Length L Ch R = 1,12437,144,144,144
BEGIN DESCRIPTION:
Mapping XS c83bfa44
END DESCRIPTION:
XS GIS Cut Line= 4
      2395273.61      7057281.20      2395174.83      7057264.92
      2394884.63      7057257.62      2394492.63      7057257.32
#Sta/Elev= 30
  4609.6  571.59  4643.7  572.26  4675.1  571.65  4704.8  570.51  4715.5  569.28
  4775.6  567.04  4795.6  564.93  4825.6  563.06  4915.6  561.68  4955.6  556.56
  4985.6  549.14  4995.3  545.98  5000.0  545.98  5005.6  543.31  5012.9  542.95
  5013.7  542.45  5018.4  542.95  5025.6  545.81  5035.6  547.90  5045.6  551.96
  5055.6  557.84  5065.6  560.79  5085.6  564.46  5135.6  571.18  5265.6  573.77
  5285.6  573.59  5295.6  574.42  5315.6  574.35  5335.6  576.06  5392.0  577.67
#Mann=3,-1,0
  4609.6    0.05       0  5012.9    0.05       0  5018.4    0.05       0
Bank Sta=5012.9,5018.4
Exp/Cntr=0.3,0.1

Type RM Length L Ch R = 1,12293,433,433,433
BEGIN DESCRIPTION:
Wichita Creek 27.0
END DESCRIPTION:
XS GIS Cut Line= 3
      2395186.36      7057245.77      2394951.99      7057136.48
      2394774.80      7057114.89
#Sta/Elev= 30
  4741.4  568.64  4749.5  567.62  4789.4  565.42  4804.7  563.80  4826.8  562.62
  4857.9  559.73  4863.5  559.89  4880.8  557.00  4886.3  558.42  4893.0  557.29
  4903.7  553.62  4909.2  556.07  4932.1  548.37  4983.3  548.98  5004.0  548.48
  5010.2  544.38  5020.4  542.89  5021.2  542.39  5025.1  542.39  5025.9  542.89
  5043.3  548.20  5053.4  548.02  5063.5  550.06  5073.5  553.68  5091.8  557.97
  5113.8  559.65  5144.1  564.50  5154.1  566.83  5173.4  569.89  5178.5  570.12
#Mann=3,-1,0
  4741.4    0.05       0  5020.4   0.033       0  5025.9    0.05       0
Bank Sta=5020.4,5025.9
Exp/Cntr=0.3,0.1

Type RM Length L Ch R = 1,11860,443,443,443
BEGIN DESCRIPTION:
Wichita Creek 26.0
END DESCRIPTION:
XS GIS Cut Line= 3
      2395279.00      7056810.00      2395128.93      7056789.97
      2394929.04      7056859.99
#Sta/Elev= 30
  4848.6  567.33  4851.1  567.33  4868.8  563.51  4878.9  560.40  4885.1  558.97
  4899.0  558.13  4958.2  552.51  4963.3  552.81  4969.7  550.40  4979.8  545.40
  4989.8  543.14  4994.6  541.21  4995.5  540.71  4999.4  540.71  5000.2  541.21
  5002.6  541.21  5010.2  543.51  5015.5  542.71  5021.1  544.91  5031.7  551.95
  5041.2  553.19  5072.3  553.02  5127.1  555.29  5139.6  556.31  5165.3  560.21
  5180.6  562.01  5190.6  564.07  5196.3  565.65  5209.2  567.86  5211.8  567.86
#Mann=4,-1,0
  4848.6    0.12       0  4994.6    0.07       0  5000.2    0.12       0
  5180.6    0.05       0
Bank Sta=4994.6,5000.2
Exp/Cntr=0.3,0.1

Type RM Length L Ch R = 1,11417,474,474,474
BEGIN DESCRIPTION:
Wichita Creek 25.0
END DESCRIPTION:
XS GIS Cut Line= 3
      2395305.51      7056579.55      2395096.56      7056405.45
      2394775.43      7056447.11
#Sta/Elev= 30
  4709.5  560.75  4714.0  561.56  4732.5  561.26  4757.0  560.10  4784.3  556.54
  4876.8  550.82  4934.0  549.47  4940.5  548.70  4948.3  545.41  4954.9  544.82
  4962.7  542.00  4969.2  542.09  4973.8  539.19  4974.7  538.69  4979.5  539.19
  4989.1  539.33  4999.2  542.29  5009.3  543.46  5029.4  542.86  5069.8  543.64
  5100.0  549.61  5110.1  550.69  5182.5  552.56  5200.9  554.06  5208.6  555.65
  5213.6  555.03  5221.0  558.05  5251.3  566.82  5301.0  575.78  5305.3  575.78
#Mann=5,-1,0
  4709.5    0.05       0  4732.5    0.12       0  4973.8    0.07       0
  4979.5    0.12       0  5182.5    0.05       0
Bank Sta=4973.8,4979.5
Exp/Cntr=0.3,0.1

Type RM Length L Ch R = 1,10943,440,440,440
BEGIN DESCRIPTION:
Wichita Creek 24.0
END DESCRIPTION:
XS GIS Cut Line= 3
      2395533.33      7056026.15      2395279.01      7056032.66
      2395028.97      7056160.01
#Sta/Elev= 30
  4745.6  570.74  4750.2  570.74  4759.9  568.65  4769.9  565.96  4779.5  561.88
  4789.9  558.76  4820.0  558.89  4840.0  554.56  4878.6  549.97  4900.0  547.83
  4910.0  545.12  4930.0  542.18  4950.0  542.05  4957.1  536.15  4958.0  535.65
  4962.8  536.15  4970.0  536.32  4980.0  540.16  5002.6  538.90  5022.0  541.42
  5027.6  541.28  5033.7  544.96  5044.3  546.60  5133.2  547.08  5222.2  551.10
  5244.4  553.26  5250.0  558.35  5266.6  559.20  5272.3  561.51  5280.6  560.99
#Mann=5,-1,0
  4745.6    0.12       0  4779.5    0.05       0  4878.6    0.12       0
  4957.1    0.07       0  4962.8    0.12       0
Bank Sta=4957.1,4962.8
Exp/Cntr=0.3,0.1