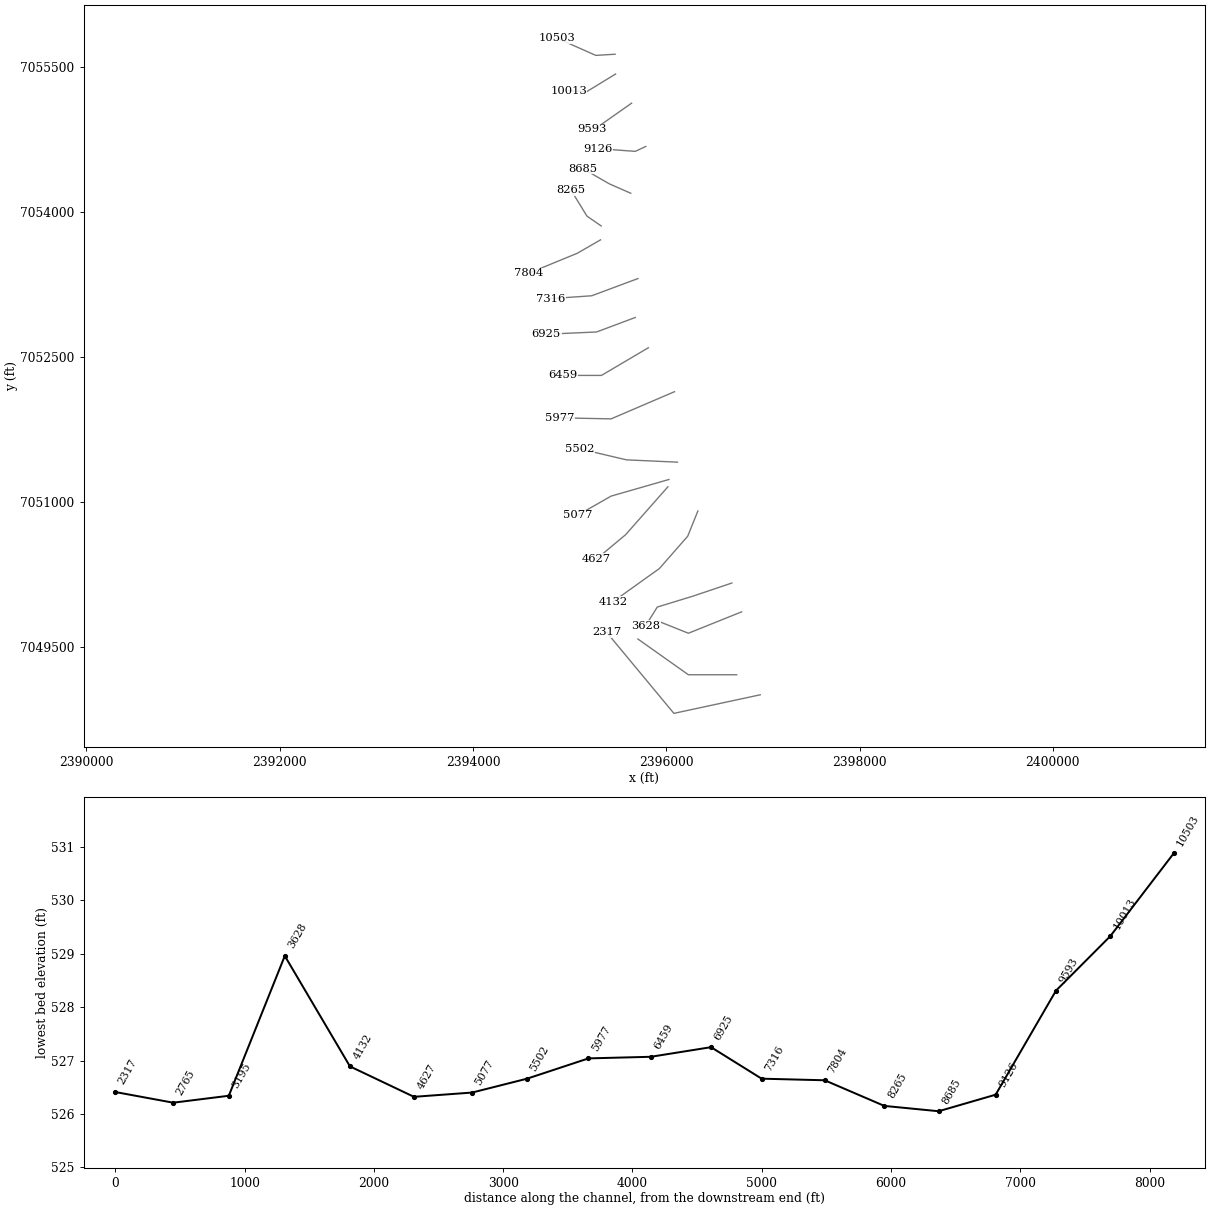
HEC-RAS study Wichita Creek.prj: Wichita Creek Base Level Engineering

--- Wichita Creek.g01 (geometry) --- (continued)

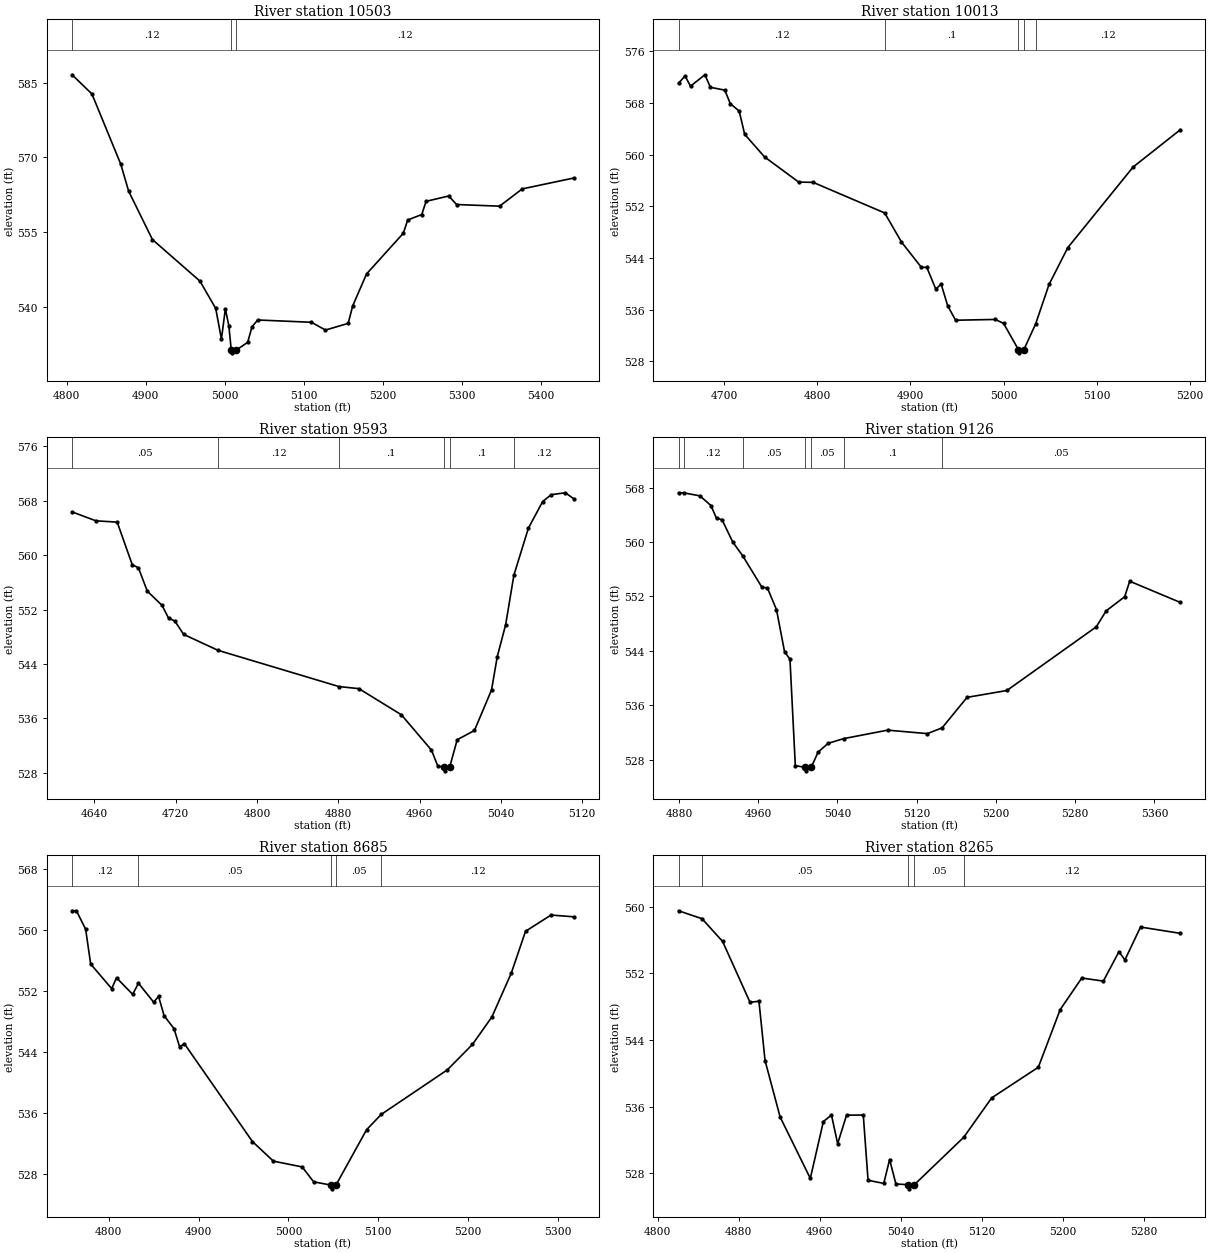
Type RM Length L Ch R = 1,10503,490,490,490
BEGIN DESCRIPTION:
Wichita Creek 23.0
END DESCRIPTION:
XS GIS Cut Line= 3
      2395470.52      7055636.40      2395270.89      7055624.47
      2394873.32      7055801.05
#Sta/Elev= 30
  4806.9  586.56  4832.0  582.73  4868.5  568.67  4878.5  563.25  4908.6  553.56
  4968.7  545.25  4988.7  539.76  4995.9  533.63  5000.9  539.69  5005.3  536.28
  5008.4  531.38  5009.4  530.88  5014.2  531.38  5029.1  532.98  5034.6  536.09
  5041.8  537.46  5109.8  537.00  5127.6  535.44  5156.3  536.78  5162.1  540.31
  5179.6  546.69  5226.1  554.83  5231.6  557.48  5249.4  558.57  5254.9  561.22
  5283.6  562.29  5293.4  560.58  5347.9  560.25  5376.6  563.71  5441.9  565.89
#Mann=3,-1,0
  4806.9    0.12       0  5008.4    0.07       0  5014.2    0.12       0
Bank Sta=5008.4,5014.2
Exp/Cntr=0.3,0.1

Type RM Length L Ch R = 1,10013,420,420,420
BEGIN DESCRIPTION:
Wichita Creek 22.0
END DESCRIPTION:
XS GIS Cut Line= 3
      2395475.50      7055431.42      2395177.78      7055249.50
      2394988.31      7055258.90
#Sta/Elev= 30
  4651.1  571.09  4658.1  572.19  4664.0  570.63  4679.4  572.39  4685.3  570.45
  4700.8  570.01  4706.6  567.93  4716.2  566.77  4722.1  563.17  4743.4  559.67
  4780.1  555.77  4795.6  555.73  4872.4  550.99  4890.4  546.49  4911.7  542.58
  4917.6  542.56  4927.2  539.21  4933.0  539.96  4940.0  536.61  4948.5  534.38
  4991.1  534.50  5000.0  533.89  5015.9  529.83  5016.8  529.33  5021.8  529.83
  5034.4  533.81  5048.8  539.92  5068.9  545.62  5139.0  558.10  5189.7  563.88
#Mann=5,-1,0
  4651.1    0.12       0  4872.4     0.1       0  5015.9    0.07       0
  5021.8     0.1       0  5034.4    0.12       0
Bank Sta=5015.9,5021.8
Exp/Cntr=0.3,0.1

Type RM Length L Ch R = 1,9593,467,467,467
BEGIN DESCRIPTION:
Wichita Creek 21.0
END DESCRIPTION:
XS GIS Cut Line= 3
      2395641.49      7055129.75      2395329.00      7054910.00
      2395229.02      7054860.01
#Sta/Elev= 30
  4618.0  566.34  4641.5  565.03  4662.4  564.84  4677.2  558.59  4683.3  558.13
  4692.0  554.71  4706.6  552.60  4713.0  550.72  4719.1  550.32  4727.8  548.35
  4761.6  546.01  4880.6  540.69  4900.3  540.38  4942.1  536.54  4971.7  531.35
  4977.8  529.05  4983.6  528.81  4984.5  528.31  4989.5  528.81  4997.0  532.88
  5014.0  534.24  5030.8  540.20  5036.4  545.07  5044.7  549.79  5052.8  557.06
  5067.1  563.97  5081.1  567.86  5089.5  568.87  5103.4  569.15  5111.8  568.26
#Mann=6,-1,0
  4618.0    0.05       0  4761.6    0.12       0  4880.6     0.1       0
  4983.6    0.07       0  4989.5     0.1       0  5052.8    0.12       0
Bank Sta=4983.6,4989.5
Exp/Cntr=0.3,0.1

Type RM Length L Ch R = 1,9126,441,441,441
BEGIN DESCRIPTION:
Wichita Creek 20.0
END DESCRIPTION:
XS GIS Cut Line= 3
      2395788.61      7054681.34      2395679.48      7054630.47
      2395294.33      7054658.86
#Sta/Elev= 30
  4879.6  567.23  4884.7  567.22  4901.2  566.78  4912.3  565.35  4918.0  563.46
  4923.5  563.28  4934.3  560.00  4944.5  557.94  4963.8  553.34  4969.3  553.25
  4978.5  550.05  4986.6  543.89  4992.1  542.76  4997.5  527.13  5007.6  526.86
  5008.5  526.36  5013.5  526.86  5020.5  529.11  5030.6  530.40  5046.2  531.09
  5090.7  532.34  5130.8  531.83  5145.7  532.68  5170.9  537.16  5211.1  538.17
  5301.3  547.52  5311.3  549.87  5330.0  551.95  5335.1  554.23  5386.2  551.11
#Mann=7,-1,0
  4879.6    0.05       0  4884.7    0.12       0  4944.5    0.05       0
  5007.6   0.033       0  5013.5    0.05       0  5046.2     0.1       0
  5145.7    0.05       0
Bank Sta=5007.6,5013.5
Exp/Cntr=0.3,0.1

Type RM Length L Ch R = 1,8685,420,420,420
BEGIN DESCRIPTION:
Wichita Creek 19.0
END DESCRIPTION:
XS GIS Cut Line= 3
      2395632.82      7054196.63      2395412.30      7054293.35
      2395136.95      7054451.62
#Sta/Elev= 30
  4759.2  562.49  4764.0  562.49  4774.3  560.08  4779.9  555.51  4803.3  552.29
  4808.7  553.71  4826.6  551.54  4833.1  552.99  4850.0  550.51  4855.5  551.27
  4861.6  548.74  4872.6  547.05  4878.8  544.70  4884.3  545.05  4959.9  532.25
  4983.2  529.68  5015.3  528.92  5028.0  526.97  5046.9  526.55  5047.9  526.05
  5052.9  526.55  5086.9  533.79  5103.2  535.80  5176.8  541.64  5204.8  544.98
  5226.4  548.58  5248.0  554.33  5263.8  559.80  5292.2  561.93  5317.6  561.70
#Mann=5,-1,0
  4759.2    0.12       0  4833.1    0.05       0  5046.9   0.033       0
  5052.9    0.05       0  5103.2    0.12       0
Bank Sta=5046.9,5052.9
Exp/Cntr=0.3,0.1

Type RM Length L Ch R = 1,8265,461,461,461
BEGIN DESCRIPTION:
Wichita Creek 18.0
END DESCRIPTION:
XS GIS Cut Line= 3
      2395326.65      7053858.07      2395179.00      7053960.00
      2395014.16      7054229.57
#Sta/Elev= 30
  4820.6  559.52  4843.8  558.57  4864.1  555.84  4891.2  548.53  4900.0  548.67
  4906.0  541.55  4920.9  534.77  4950.7  527.40  4963.6  534.23  4971.6  535.00
  4977.7  531.57  4986.5  535.00  5003.0  535.00  5007.7  527.18  5023.2  526.80
  5029.0  529.67  5035.2  526.73  5047.3  526.65  5048.3  526.15  5053.4  526.65
  5102.2  532.34  5129.7  537.06  5175.8  540.74  5197.4  547.66  5218.7  551.45
  5240.0  551.08  5255.4  554.61  5261.3  553.62  5276.7  557.57  5316.0  556.81
#Mann=5,-1,0
  4820.6    0.12       0  4843.8    0.05       0  5047.3   0.033       0
  5053.4    0.05       0  5102.2    0.12       0
Bank Sta=5047.3,5053.4
Exp/Cntr=0.3,0.1

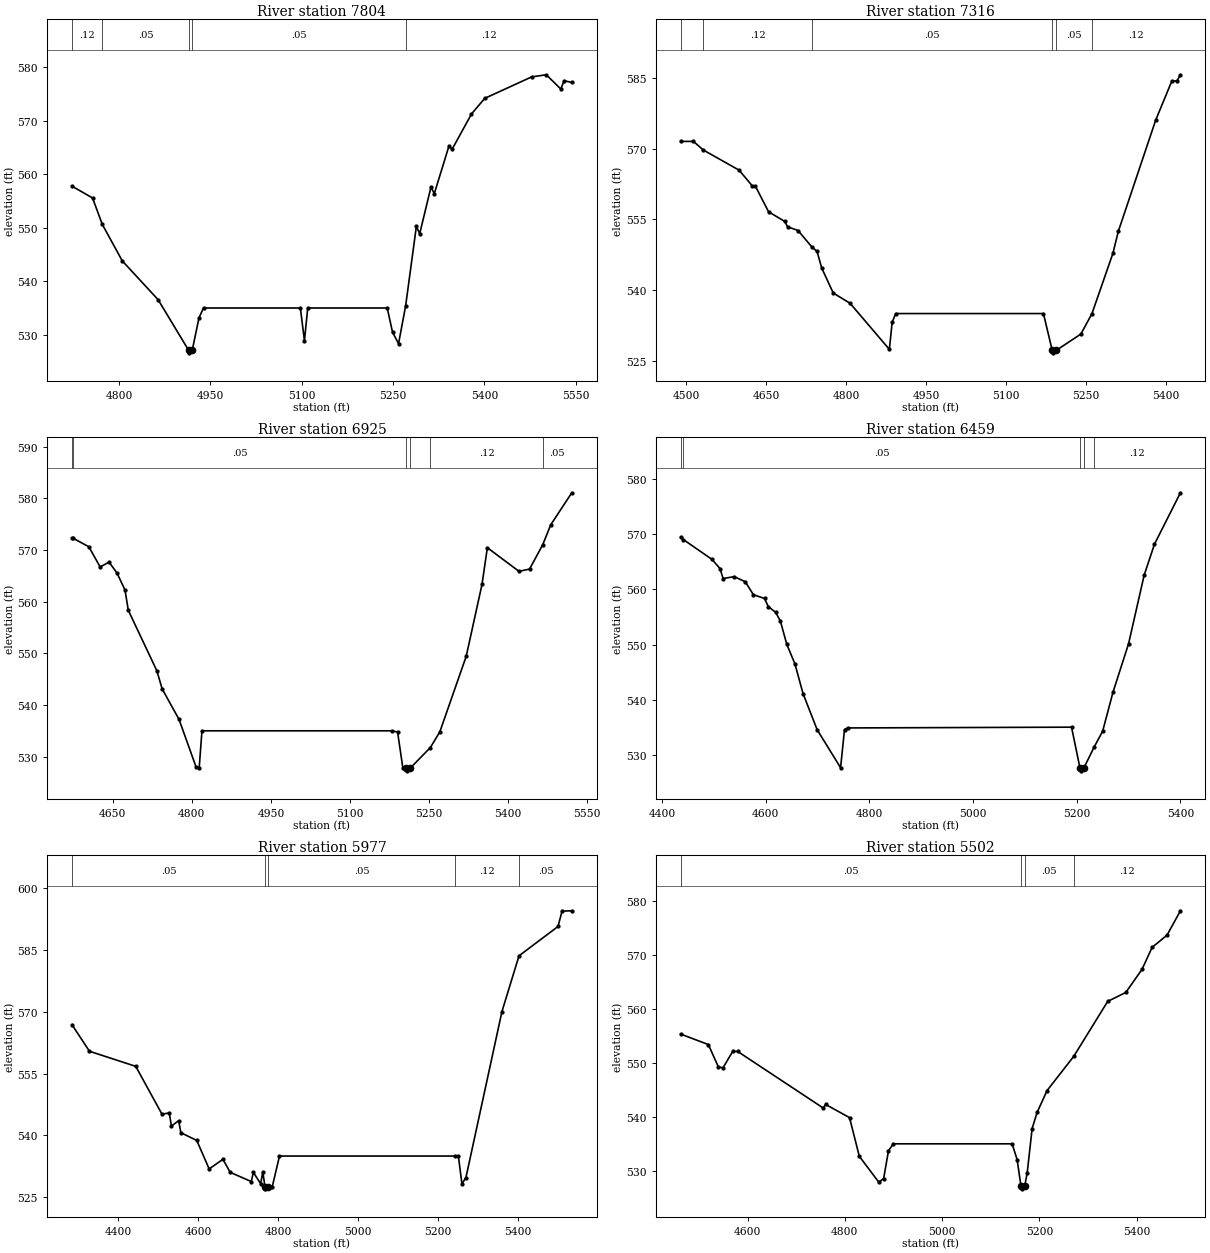
Type RM Length L Ch R = 1,7804,488,488,488
BEGIN DESCRIPTION:
Wichita Creek 17.0
END DESCRIPTION:
XS GIS Cut Line= 3
      2395319.68      7053713.97      2395079.39      7053575.16
      2394576.61      7053368.48
#Sta/Elev= 30
  4722.5  557.75  4756.3  555.55  4772.3  550.62  4805.2  543.79  4864.0  536.56
  4914.0  527.13  4915.0  526.63  4920.1  527.13  4931.2  533.18  4938.6  535.00
  5097.7  535.00  5104.4  528.91  5109.8  535.00  5240.4  535.00  5249.1  530.49
  5259.0  528.35  5270.6  535.37  5288.3  550.26  5293.7  548.86  5312.3  557.60
  5317.7  556.35  5341.7  565.20  5347.1  564.66  5378.8  571.23  5400.5  574.14
  5477.7  578.16  5501.7  578.55  5525.6  575.89  5531.0  577.45  5543.6  577.11
#Mann=5,-1,0
  4722.5    0.12       0  4772.3    0.05       0  4914.0   0.033       0
  4920.1    0.05       0  5270.6    0.12       0
Bank Sta=4914,4920.1
Exp/Cntr=0.3,0.1

Type RM Length L Ch R = 1,7316,391,391,391
BEGIN DESCRIPTION:
Wichita Creek 16.0
END DESCRIPTION:
XS GIS Cut Line= 3
      2395706.94      7053313.25      2395229.00      7053135.00
      2394802.75      7053105.14
#Sta/Elev= 30
  4489.9  571.54  4513.9  571.55  4532.6  569.71  4599.6  565.44  4624.5  562.09
  4629.9  562.10  4654.9  556.60  4685.2  554.56  4690.5  553.42  4710.2  552.63
  4735.9  549.16  4745.8  548.19  4754.5  544.68  4776.1  539.37  4807.9  537.16
  4881.4  527.40  4886.7  533.15  4893.3  535.00  5170.4  535.00  5186.9  527.16
  5188.0  526.66  5194.1  527.16  5240.6  530.65  5261.3  534.96  5300.7  547.79
  5310.8  552.44  5380.9  576.06  5411.0  584.31  5421.0  584.41  5427.3  585.69
#Mann=6,-1,0
  4489.9    0.05       0  4532.6    0.12       0  4735.9    0.05       0
  5186.9   0.033       0  5194.1    0.05       0  5261.3    0.12       0
Bank Sta=5186.9,5194.1
Exp/Cntr=0.3,0.1

Type RM Length L Ch R = 1,6925,466,466,466
BEGIN DESCRIPTION:
Wichita Creek 15.0
END DESCRIPTION:
XS GIS Cut Line= 3
      2395679.00      7052910.00      2395279.00      7052760.00
      2394759.01      7052736.87
#Sta/Elev= 30
  4572.8  572.26  4575.3  572.26  4604.8  570.63  4626.2  566.72  4643.1  567.65
  4658.2  565.54  4673.4  562.24  4679.6  558.33  4733.9  546.59  4743.7  543.13
  4775.7  537.23  4807.8  528.08  4814.0  527.80  4819.3  535.00  5180.2  535.00
  5190.2  534.75  5200.2  527.81  5206.6  527.75  5207.7  527.25  5213.9  527.75
  5252.2  531.74  5270.3  534.80  5320.3  549.42  5350.3  563.36  5360.4  570.45
  5420.4  565.87  5440.4  566.31  5465.4  571.02  5480.5  574.87  5520.5  581.08
#Mann=6,-1,0
  4572.8    0.12       0  4575.3    0.05       0  5206.6   0.033       0
  5213.9    0.05       0  5252.2    0.12       0  5465.4    0.05       0
Bank Sta=5206.6,5213.9
Exp/Cntr=0.3,0.1

Type RM Length L Ch R = 1,6459,482,482,482
BEGIN DESCRIPTION:
Wichita Creek 14.0
END DESCRIPTION:
XS GIS Cut Line= 3
      2395814.69      7052596.49      2395329.00      7052310.00
      2394928.99      7052310.00
#Sta/Elev= 30
  4436.1  569.48  4441.6  569.05  4496.5  565.47  4512.2  563.79  4518.0  561.99
  4539.4  562.33  4560.9  561.40  4576.5  559.05  4598.0  558.37  4605.2  556.89
  4619.4  555.85  4628.5  554.28  4640.9  550.03  4656.5  546.52  4672.2  541.10
  4699.4  534.54  4744.6  527.64  4752.2  534.56  4758.0  534.86  5190.0  535.00
  5206.3  527.57  5207.4  527.07  5213.7  527.57  5233.5  531.37  5250.0  534.26
  5270.0  541.36  5300.0  550.15  5330.0  562.58  5350.0  568.24  5400.0  577.56
#Mann=5,-1,0
  4436.1    0.12       0  4441.6    0.05       0  5206.3   0.033       0
  5213.7    0.05       0  5233.5    0.12       0
Bank Sta=5206.3,5213.7
Exp/Cntr=0.3,0.1

Type RM Length L Ch R = 1,5977,475,475,475
BEGIN DESCRIPTION:
Wichita Creek 13.0
END DESCRIPTION:
XS GIS Cut Line= 3
      2396085.52      7052141.63      2395429.00      7051860.00
      2394894.58      7051870.81
#Sta/Elev= 30
  4285.2  566.88  4328.9  560.43  4444.6  556.76  4510.1  545.16  4528.3  545.46
  4533.7  542.27  4551.8  543.59  4557.3  540.66  4597.0  538.79  4628.0  531.87
  4662.4  534.21  4680.5  531.05  4733.1  528.81  4738.5  531.01  4756.7  528.29
  4762.1  531.15  4767.4  527.54  4768.5  527.04  4774.8  527.54  4785.7  527.57
  4803.7  535.00  5243.0  535.00  5250.7  535.00  5259.6  528.23  5269.6  529.78
  5359.6  570.07  5402.2  583.59  5499.7  590.71  5509.7  594.43  5534.1  594.52
#Mann=5,-1,0
  4285.2    0.05       0  4767.4   0.033       0  4774.8    0.05       0
  5243.0    0.12       0  5402.2    0.05       0
Bank Sta=4767.4,4774.8
Exp/Cntr=0.3,0.1

Type RM Length L Ch R = 1,5502,425,425,425
BEGIN DESCRIPTION:
Wichita Creek 12.0
END DESCRIPTION:
XS GIS Cut Line= 3
      2396115.99      7051411.70      2395588.69      7051435.57
      2395102.25      7051550.15
#Sta/Elev= 30
  4462.4  555.33  4519.5  553.38  4540.0  549.25  4549.5  549.06  4569.5  552.11
  4579.5  552.12  4755.6  541.63  4760.6  542.29  4809.7  539.85  4829.8  532.69
  4869.8  527.90  4879.8  528.55  4889.8  533.71  4899.8  535.00  5144.0  535.00
  5154.3  532.06  5162.2  527.16  5163.4  526.66  5169.7  527.16  5174.9  529.54
  5185.1  537.82  5195.4  540.83  5215.9  544.87  5270.7  551.20  5340.5  561.38
  5377.7  563.03  5411.1  567.32  5431.7  571.37  5462.5  573.65  5490.0  578.16
#Mann=4,-1,0
  4462.4    0.05       0  5162.2   0.033       0  5169.7    0.05       0
  5270.7    0.12       0
Bank Sta=5162.2,5169.7
Exp/Cntr=0.3,0.1

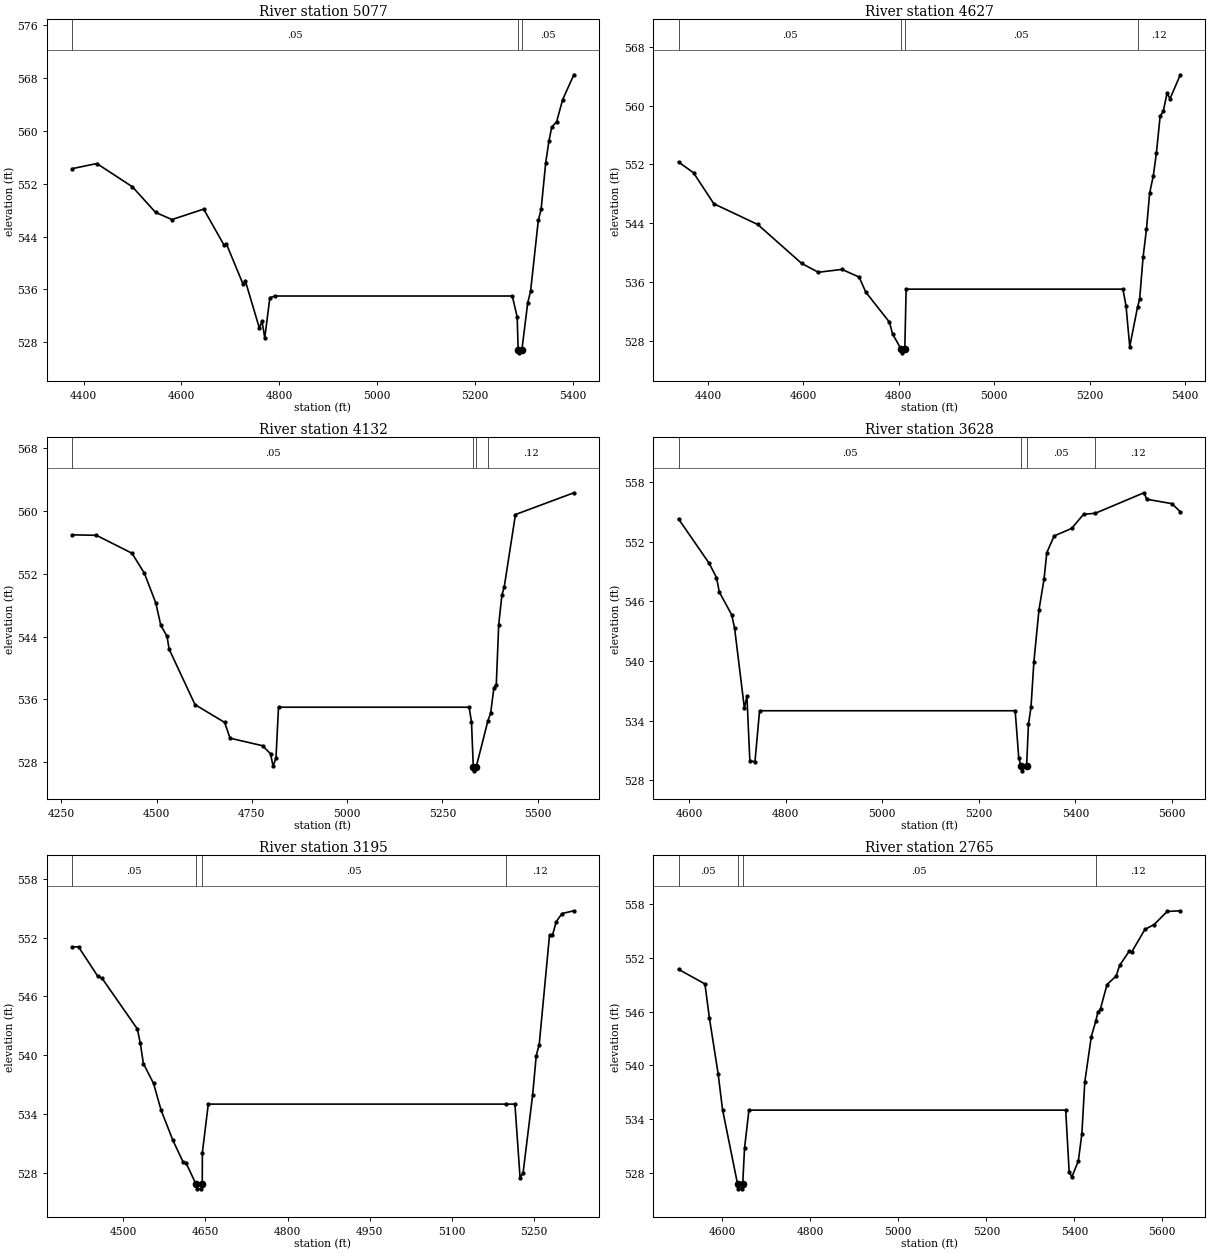
Type RM Length L Ch R = 1,5077,450,450,450
BEGIN DESCRIPTION:
Wichita Creek 11.0
END DESCRIPTION:
XS GIS Cut Line= 3
      2396027.64      7051232.23      2395429.00      7051060.00
      2395079.03      7050860.02
#Sta/Elev= 30
  4376.6  554.27  4427.2  555.05  4500.1  551.52  4547.2  547.66  4580.8  546.57
  4645.7  548.15  4687.1  542.73  4692.3  542.86  4726.0  536.83  4731.2  537.21
  4759.7  530.11  4764.9  531.22  4770.6  528.66  4781.0  534.74  4791.4  535.00
  5276.7  535.00  5286.7  531.83  5288.7  526.90  5289.9  526.40  5296.4  526.90
  5308.3  533.99  5314.1  535.72  5329.9  546.45  5335.7  548.15  5345.1  555.20
  5351.5  558.39  5357.3  560.56  5367.4  561.37  5379.6  564.71  5402.6  568.48
#Mann=3,-1,0
  4376.6    0.05       0  5288.7   0.033       0  5296.4    0.05       0
Bank Sta=5288.7,5296.4
Exp/Cntr=0.3,0.1

Type RM Length L Ch R = 1,4627,495,495,495
BEGIN DESCRIPTION:
Wichita Creek 10.0
END DESCRIPTION:
XS GIS Cut Line= 3
      2396016.77      7051156.29      2395579.00      7050660.00
      2395278.99      7050409.99
#Sta/Elev= 30
  4338.0  552.32  4369.4  550.86  4412.1  546.63  4504.1  543.81  4596.1  538.51
  4631.2  537.30  4680.6  537.69  4716.6  536.65  4730.8  534.58  4780.2  530.51
  4786.8  528.90  4804.8  526.82  4806.0  526.32  4812.5  526.82  4815.3  535.00
  5269.9  535.00  5276.4  532.73  5284.2  527.17  5300.6  532.56  5305.0  533.65
  5312.2  539.37  5319.3  543.16  5325.9  548.07  5333.7  550.47  5340.2  553.60
  5348.0  558.58  5354.5  559.22  5362.3  561.66  5368.8  560.97  5390.3  564.21
#Mann=4,-1,0
  4338.0    0.05       0  4804.8   0.033       0  4812.5    0.05       0
  5300.6    0.12       0
Bank Sta=4804.8,4812.5
Exp/Cntr=0.3,0.1

Type RM Length L Ch R = 1,4132,504,504,504
BEGIN DESCRIPTION:
Wichita Creek 9.0
END DESCRIPTION:
XS GIS Cut Line= 5
      2396327.18      7050906.04      2396222.18      7050645.07
      2395929.00      7050310.00      2395700.23      7050146.59
      2395448.71      7049966.17
#Sta/Elev= 30
  4278.1  556.97  4342.0  556.91  4435.5  554.62  4467.8  552.08  4497.9  548.29
  4511.0  545.44  4527.4  544.03  4532.8  542.41  4600.8  535.33  4678.6  533.06
  4692.8  531.05  4778.3  530.09  4799.1  529.06  4805.8  527.47  4813.4  528.54
  4820.0  535.00  5320.4  535.00  5326.6  533.11  5331.3  527.39  5332.5  526.89
  5339.0  527.39  5369.5  533.24  5376.9  534.27  5385.5  537.50  5391.7  537.88
  5398.0  545.49  5406.4  549.28  5412.5  550.32  5442.0  559.56  5595.3  562.33
#Mann=4,-1,0
  4278.1    0.05       0  5331.3   0.033       0  5339.0    0.05       0
  5369.5    0.12       0
Bank Sta=5331.3,5339
Exp/Cntr=0.3,0.1

Type RM Length L Ch R = 1,3628,433,433,433
BEGIN DESCRIPTION:
Wichita Creek 8.0
END DESCRIPTION:
XS GIS Cut Line= 4
      2396678.97      7050159.99      2396279.40      7050025.17
      2395906.94      7049910.85      2395786.18      7049717.70
#Sta/Elev= 30
  4578.3  554.28  4641.6  549.83  4656.9  548.39  4662.7  546.94  4688.4  544.64
  4694.4  543.30  4714.6  535.28  4719.9  536.45  4726.0  529.95  4736.6  529.89
  4746.1  535.00  5275.4  535.00  5282.9  530.22  5287.6  529.46  5289.2  528.96
  5299.1  529.46  5302.9  533.64  5308.2  535.37  5314.2  539.95  5324.7  545.14
  5335.2  548.24  5340.9  550.89  5356.1  552.57  5392.4  553.33  5417.1  554.75
  5441.3  554.85  5542.0  556.91  5547.9  556.26  5599.8  555.82  5617.4  555.00
#Mann=4,-1,0
  4578.3    0.05       0  5287.6   0.033       0  5299.1    0.05       0
  5441.3    0.12       0
Bank Sta=5287.6,5299.1
Exp/Cntr=0.3,0.1

Type RM Length L Ch R = 1,3195,430,430,430
BEGIN DESCRIPTION:
Wichita Creek 7.0
END DESCRIPTION:
XS GIS Cut Line= 3
      2396779.92      7049861.41      2396229.06      7049639.97
      2395928.98      7049760.01
#Sta/Elev= 30
  4406.3  551.07  4418.1  551.07  4453.0  548.09  4461.2  547.85  4525.6  542.68
  4531.0  541.21  4536.6  539.15  4555.2  537.11  4569.0  534.38  4590.5  531.30
  4608.9  529.12  4614.3  529.00  4632.7  526.84  4634.3  526.34  4642.6  526.34
  4644.2  526.84  4644.4  530.04  4655.2  535.00  5198.5  535.00  5215.5  535.00
  5224.9  527.48  5230.3  527.92  5247.8  535.90  5254.5  539.96  5259.9  541.09
  5278.7  552.26  5284.1  552.24  5290.9  553.64  5301.6  554.48  5323.2  554.76
#Mann=4,-1,0
  4406.3    0.05       0  4632.7   0.033       0  4644.2    0.05       0
  5198.5    0.12       0
Bank Sta=4632.7,4644.2
Exp/Cntr=0.3,0.1

Type RM Length L Ch R = 1,2765,448,448,448
BEGIN DESCRIPTION:
Wichita Creek 6.0
END DESCRIPTION:
XS GIS Cut Line= 3
      2396729.00      7049210.00      2396229.00      7049210.00
      2395706.39      7049580.12
#Sta/Elev= 30
  4500.4  550.72  4560.4  549.09  4570.4  545.34  4590.4  539.05  4600.4  535.06
  4634.7  526.71  4636.3  526.21  4644.6  526.21  4646.2  526.71  4650.4  530.75
  4660.4  535.00  5380.3  535.00  5388.1  528.14  5394.2  527.52  5409.0  529.32
  5417.0  532.34  5423.7  538.14  5438.5  543.22  5448.6  544.92  5453.3  545.92
  5459.4  546.33  5474.2  549.02  5495.1  549.98  5502.8  551.16  5524.7  552.75
  5530.8  552.70  5560.3  555.18  5581.2  555.72  5610.8  557.18  5640.8  557.26
#Mann=4,-1,0
  4500.4    0.05       0  4634.7   0.033       0  4646.2    0.05       0
  5448.6    0.12       0
Bank Sta=4634.7,4646.2
Exp/Cntr=0.3,0.1

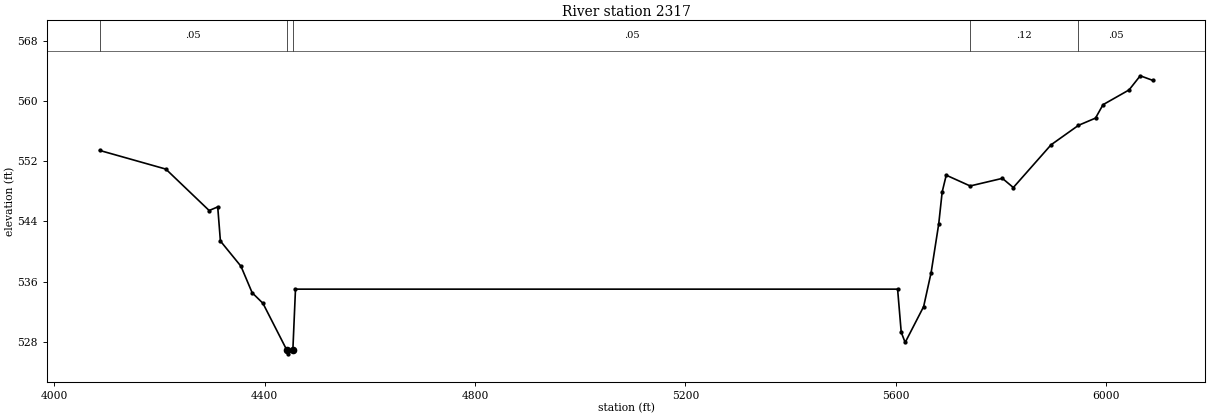
Type RM Length L Ch R = 1,2317,0,0,0
BEGIN DESCRIPTION:
Wichita Creek 5.0
END DESCRIPTION:
XS GIS Cut Line= 3
      2396972.60      7049002.50      2396079.00      7048810.00
      2395384.07      7049648.32
#Sta/Elev= 30
  4085.9  553.42  4211.8  550.94  4294.2  545.44  4310.5  545.92  4315.6  541.39
  4354.7  538.04  4376.0  534.52  4396.5  533.12  4441.9  526.91  4443.5  526.41
  4453.4  526.91  4458.4  535.00  5603.6  535.00  5610.5  529.27  5618.0  527.92
  5653.1  532.68  5667.4  537.21  5681.8  543.65  5688.4  547.91  5696.1  550.13
  5741.6  548.70  5802.9  549.71  5823.7  548.49  5895.4  554.16  5947.6  556.75
  5980.0  557.71  5994.3  559.49  6043.8  561.45  6065.1  563.33  6088.9  562.72
#Mann=5,-1,0
  4085.9    0.05       0  4441.9   0.033       0  4453.4    0.05       0
  5741.6    0.12       0  5947.6    0.05       0
Bank Sta=4441.9,4453.4
Exp/Cntr=0.3,0.1

Chan Stop Cuts=-1